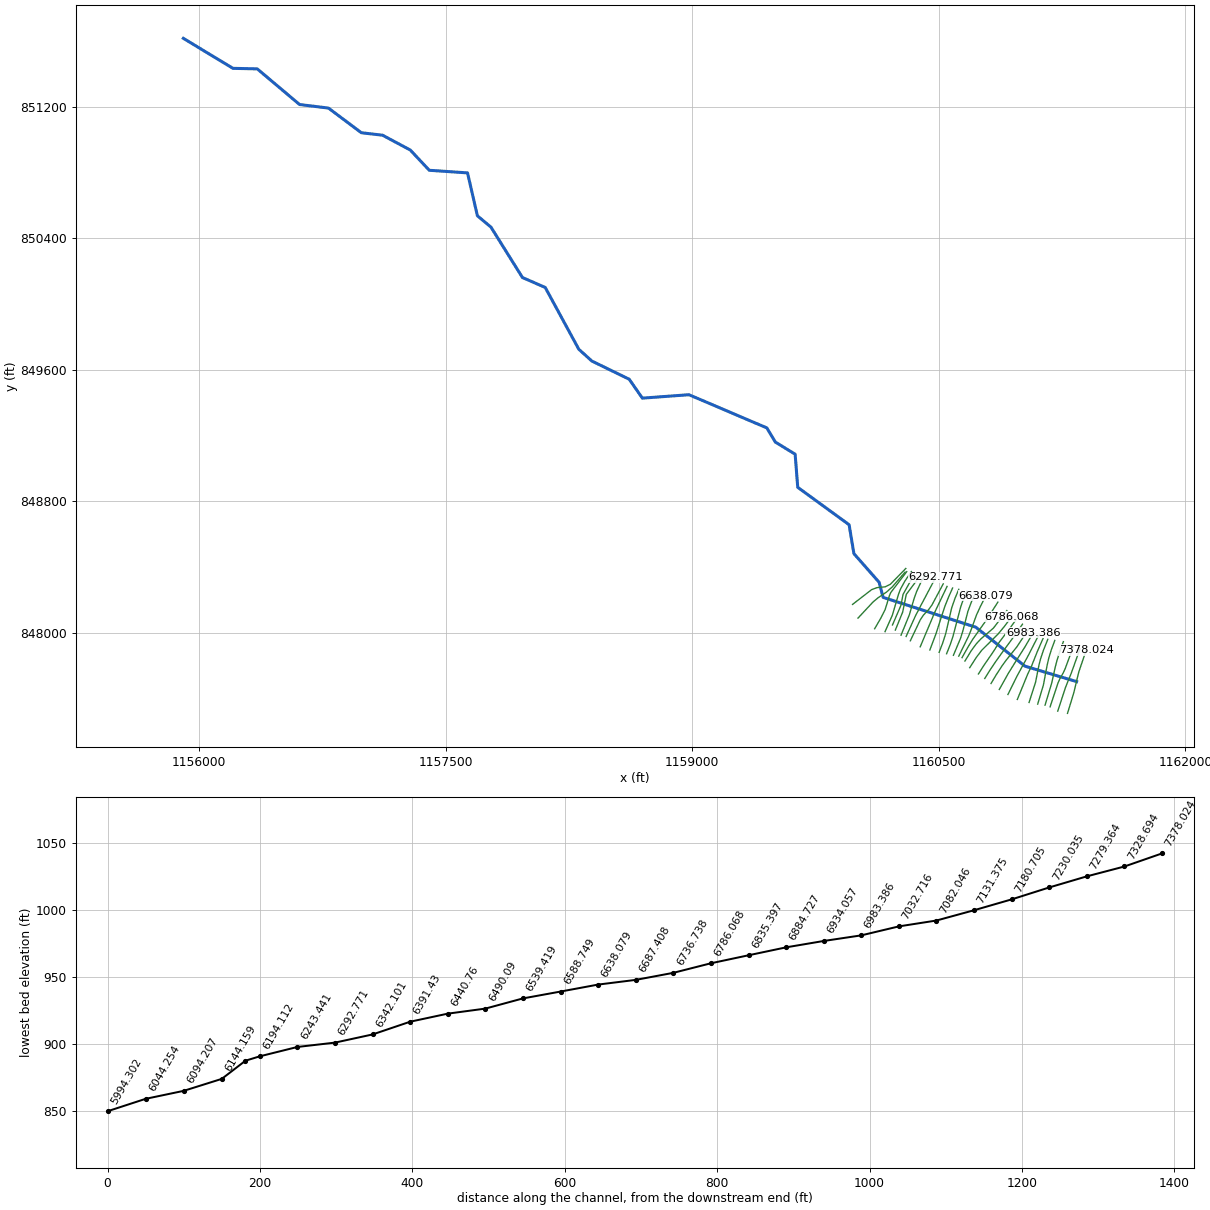
--- 177_ras.prj (project) ---

Proj Title=177
Current Plan=p01
Default Exp/Contr=0.3,0.1
English Units
Geom File=g01
Flow File=f01
Plan File=p01
Y Axis Title=Elevation
X Axis Title(PF)=Main Channel Distance
X Axis Title(XS)=Station
BEGIN DESCRIPTION:
RFD model 177 exported to HEC-RAS
END DESCRIPTION:

--- 177_ras.p01 (plan) ---

Plan Title=Plan 01
Program Version=4.10
Short Identifier=Plan 01
Geom File=g01
Flow File=f01
Subcritical Flow
Calc Critical at every XS
Secant Critical Depth

--- 177_ras.f01 (steady flow) ---

Flow Title=Flow 01
Program Version=5.01
Number of Profiles= 5
Profile Names=10yr,25yr,50yr,100yr,500yr
River Rch & RM=177,138,7378.024
   93.66  165.56  234.14  315.41  549.94
River Rch & RM=177,138,7082.046
  119.28  211.98  301.32  408.14  722.15
River Rch & RM=177,138,7032.716
  124.88  222.16  316.09  428.59  760.46
River Rch & RM=177,138,6934.057
  130.48  232.34  330.88  449.08  798.94
River Rch & RM=177,138,6786.068
  134.83  240.25  342.38  465.04  828.98
River Rch & RM=177,138,6736.738
  138.55  247.03  352.25  478.74   854.8
River Rch & RM=177,138,6588.749
  141.03  251.55  358.82  487.87  872.06
River Rch & RM=177,138, 6490.09
  142.89  254.94  363.76  494.73  885.02
River Rch & RM=177,138, 6391.43
  144.75  258.33  368.69  501.59  897.99
River Rch & RM=177,138,6292.771
   146.6  261.72  373.63  508.45  910.98
River Rch & RM=177,138,6194.112
  160.21  286.56  409.86  558.87 1006.73
River Rch & RM=177,138,6094.207
  192.84  346.34  497.29  680.94 1240.52
River Rch & RM=177,138,5994.302
   195.3  350.85   503.9  690.19 1258.33
River Rch & RM=177,138,5844.444
  200.82  360.99  518.77  711.01 1298.48
River Rch & RM=177,138,5744.539
   204.5  367.75  528.68  724.89 1325.31
River Rch & RM=177,138,5594.681
  304.41  552.22  800.54 1107.58 2074.49
River Rch & RM=177,138,5444.824
  309.86  562.33   815.5 1128.73 2116.38
River Rch & RM=177,138,5344.919
  316.52  574.68  833.78  1154.6 2167.68
River Rch & RM=177,138,5245.014
  319.55  580.29   842.1 1166.36 2191.03
River Rch & RM=177,138,5145.109
   326.2  592.64  860.39 1192.25 2242.48
River Rch & RM=177,138,4945.299
  355.79  647.63  941.94 1307.83 2472.87
River Rch & RM=177,138,4795.441
  361.82  658.85  958.59 1331.46 2520.12
River Rch & RM=177,138,4695.536
  376.88  686.89 1000.25  1390.6 2638.58
River Rch & RM=177,138,4595.631
  379.89   692.5 1008.58 1402.43 2662.33
River Rch & RM=177,138,4495.726
   383.5  699.23 1018.58 1416.64 2690.85
River Rch & RM=177,138,4395.821
  387.71  707.08 1030.25 1433.23 2724.16
River Rch & RM=177,138,4295.916
  394.33  719.41 1048.59  1459.3 2776.57
River Rch & RM=177,138,4196.011
  417.16     762 1111.98  1549.5 2958.27
River Rch & RM=177,138,4096.106
  421.96  770.96 1125.33 1568.51 2996.65
River Rch & RM=177,138,3996.201
  426.16   778.8 1137.02 1585.15 3030.26
River Rch & RM=177,138,3846.344
  537.34     987    1448 2029.33 3934.41
River Rch & RM=177,138,3746.439
  550.45  1011.6 1484.85  2082.1 4042.63
River Rch & RM=177,138,3646.534
  562.35 1033.96 1518.35 2130.11 4141.23
River Rch & RM=177,138,3546.628
  569.49 1047.37 1538.46 2158.94 4200.49
River Rch & RM=177,138,3446.724
  573.65  1055.2 1550.19 2175.76 4235.09
River Rch & RM=177,138,3346.818
  588.51 1083.14 1592.09 2235.87 4358.86
River Rch & RM=177,138,3196.961
  605.14 1114.43 1639.04 2303.26 4497.85
River Rch & RM=177,138,3047.103
  617.61 1137.89 1674.27 2353.85 4602.33
River Rch & RM=177,138,2947.198
  624.73  1151.3  1694.4 2382.77 4662.12
River Rch & RM=177,138,2847.293
  633.03 1166.94 1717.89 2416.53 4731.97
River Rch & RM=177,138,2747.388
  644.29 1188.16 1749.78 2462.37  4826.9
River Rch & RM=177,138,2597.531
  751.89  1391.3  2055.6 2902.86 5744.02
River Rch & RM=177,138,2447.673
  781.96 1448.18  2141.4 3026.72 6003.39
River Rch & RM=177,138,2347.768
  804.93 1491.67 2207.05 3121.55 6202.38
River Rch & RM=177,138,2247.863
  811.41 1503.93 2225.57 3148.32 6258.61
River Rch & RM=177,138,2098.006
  846.11  1569.7 2324.94 3292.01 6560.92
River Rch & RM=177,138,1898.196
  847.88 1573.04 2329.99 3299.32 6576.32
River Rch & RM=177,138,1798.291
  859.04 1594.22    2362 3345.64 6673.95
River Rch & RM=177,138,1698.386
  868.44 1612.05 2388.96 3384.66 6756.26
River Rch & RM=177,138, 1598.48
  880.19 1634.33 2422.67 3433.47 6859.27
River Rch & RM=177,138,1498.575
  890.76 1654.38 2453.02 3477.41  6952.1
River Rch & RM=177,138, 1398.67
  903.08 1677.78 2488.42  3528.7 7060.53
River Rch & RM=177,138,1298.765
  915.98 1702.28 2525.52 3582.46 7174.27
River Rch & RM=177,138, 1198.86
  934.75 1737.92 2579.49  3660.7    7340
River Rch & RM=177,138,1049.003
   945.3 1757.97 2609.86 3704.74 7433.36
River Rch & RM=177,138,999.0503
  951.74 1770.22 2628.42 3731.66 7490.46
River Rch & RM=177,138,799.2402
  954.67 1775.79 2636.86 3743.89 7516.43
River Rch & RM=177,138,599.4302
 1008.52 1878.21 2792.15 3969.32 7995.62
River Rch & RM=177,138,349.7532
 1101.96 2056.23  3062.5 4362.39 8834.82
River Rch & RM=177,138,211.5283
 1104.88 2061.79 3070.95 4374.69 8861.16
River Rch & RM=177,138,  99.905
 1107.21 2066.24 3077.71 4384.53 8882.23
River Rch & RM=177,138,       0
 1107.79 2067.35  3079.4 4386.99  8887.5
Boundary for River Rch & Prof#=177,138,1
Up Type= 0
Dn Type= 2
Boundary for River Rch & Prof#=177,138,2
Up Type= 0
Dn Type= 2
Boundary for River Rch & Prof#=177,138,2
Up Type= 0
Dn Type= 2
Boundary for River Rch & Prof#=177,138,2
Up Type= 0
Dn Type= 2
Boundary for River Rch & Prof#=177,138,2
Up Type= 0
Dn Type= 2

--- 177_ras.g01 (geometry) ---

Geom Title=177
Program Version=4.10

River Reach=177,138
Reach XY= 30
1161338.16601115847703.840091258 1161023.7682099847797.863549948
  1160725.434971848034.5301553161160161.26847512848216.196784526
 1160137.1018182848307.8634248521159983.76853487848482.030044466
1159954.60188186848657.8633266691159642.10198012848885.363268495
1159626.26865727849087.0298760531159506.26869458849160.363191158
1159453.76871246849247.029833749 1158980.4355239849448.696454465
1158697.10227314849427.8631354421158617.10229996849542.863103762
1158389.60236993849653.6964109091158310.43572855849725.363058701
1158106.26913264850101.1962868721157967.93584165850161.196273118
1157776.26924005850467.8628547341157693.76926628850537.029503345
1157633.76929137850797.8627613931157401.26936007850813.696096689
1157285.43606427850937.0293969661157117.10278296851027.029375225
1156987.93615463 851042.029374511156787.93621767851192.029335946
 1156612.1029366851213.6960012611156354.93231821851430.454040155
1156207.10306177851433.695947945 1155905.4364889 851616.19590272

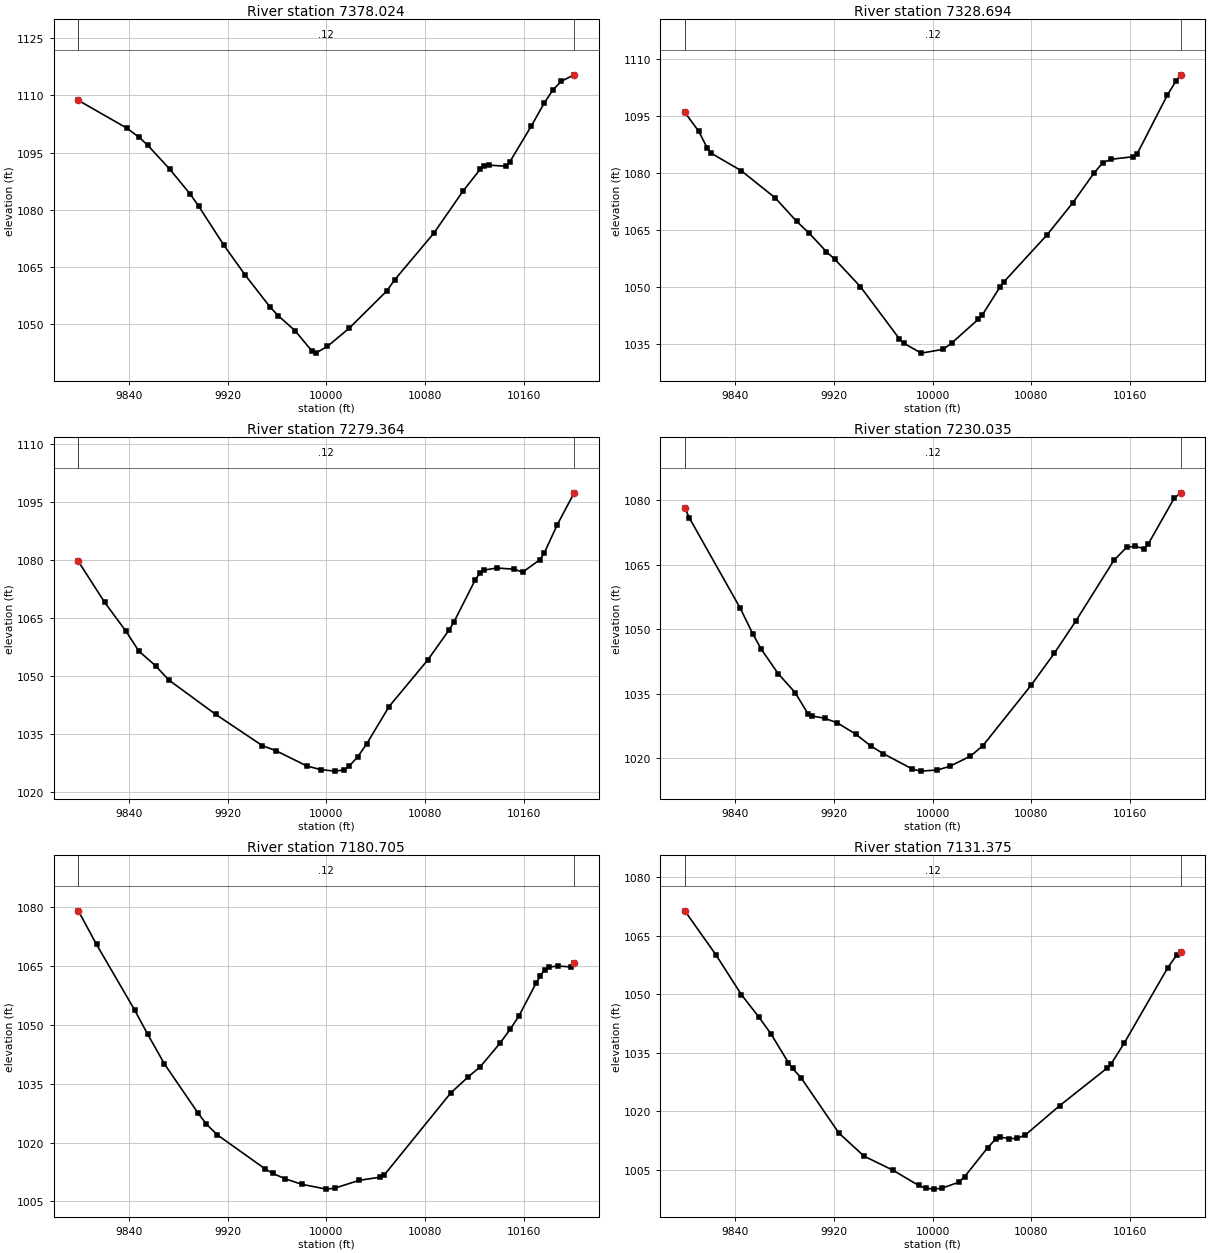
Type RM Length L Ch R = 1 ,7378.024,49.329700,49.329700,49.329700
XS GIS Cut Line= 6
1161282.76445233847510.6649131191161322.05509205 847639.52967072
1161336.99508144847703.0470442211161337.37296412847705.011020973
1161351.56840595847762.5969146321161396.62676203847895.829654112
#Sta/Elev= 30
9799.0281108.6719838.1521101.4269848.4421098.9589855.3021096.9039873.1941090.617
9889.601 1084.149896.4611080.9969917.0411070.6829934.1831062.9289954.4051054.521
9961.1461052.1979974.6271048.3239988.1091043.0879991.4791042.418   100011044.196
10018.47 1048.9110048.881058.64810055.64  1061.710087.161073.83710110.941084.918
10124.791090.60510128.251091.47810131.72 1091.6910145.571091.411 10148.61092.448
10166.351102.00610176.741107.99210183.671111.37510190.591113.68210200.961115.363
#Mann= 3 , 0 , 0
9799.028    0.12       09799.028    0.12       010200.96    0.12       0
#XS Ineff= 2 , 0
       0                               0
Bank Sta=9799.028,10200.96
Exp/Cntr=0.3,0.1

Type RM Length L Ch R = 1 ,7328.694,49.329700,49.329700,49.329700
XS GIS Cut Line= 6
1161223.42269076847524.2901375171161270.68559677  847668.5264154
1161288.54017076847713.2774301971161289.53641973847715.011641254
1161304.67685229847752.5809003311161358.51051255847902.693048866
#Sta/Elev= 30
9799.0361096.068 9810.271091.1189817.1751086.7279820.6271085.2689844.7941080.706
9872.4141073.5219889.677 1067.379900.0341064.1939913.8441059.3619920.7491057.341
9941.4641050.1379973.0381036.4049976.5711035.255  9990.71032.659 10008.51033.657
10015.581035.372 10036.81041.52310040.341042.777 10054.31049.94710057.781051.452
10092.641063.78410113.551072.24510130.98 1080.1810137.951082.84110144.921083.723
10162.351084.38210165.83 1085.2110190.231100.623 10197.2 1104.3110200.981105.955
#Mann= 3 , 0 , 0
9799.036    0.12       09799.036    0.12       010200.98    0.12       0
#XS Ineff= 2 , 0
       0                               0
Bank Sta=9799.036,10200.98
Exp/Cntr=0.3,0.1

Type RM Length L Ch R = 1 ,7279.364,49.329600,49.329600,49.329600
XS GIS Cut Line= 6
1161177.09548531847550.7314043751161224.47967319847694.046077636
1161236.52927563847721.6507524111161256.38826676847756.139435125
1161269.03423172847783.477596158 1161321.0424109847925.187356262
#Sta/Elev= 30
9799.0371079.6219820.4421068.9799837.7191061.4979848.0861056.3939861.9081052.501
9872.2741048.9299910.2851040.0249948.2951031.8869958.9741030.6459984.2451026.647
9995.564  1025.710006.961025.30910014.541025.61910018.331026.52510025.63 1029.06
10032.861032.40210050.91 1042.0210082.361054.11810099.831061.97110103.331063.811
 10120.81074.834 10124.31076.47910127.791077.35910138.281077.89710152.261077.592
10159.251076.83310173.231080.05510176.721081.751 10187.21089.05510200.971097.363
#Mann= 3 , 0 , 0
9799.037    0.12       09799.037    0.12       010200.97    0.12       0
#XS Ineff= 2 , 0
       0                               0
Bank Sta=9799.037,10200.97
Exp/Cntr=0.3,0.1

Type RM Length L Ch R = 1 ,7230.035,49.329700,49.329700,49.329700
XS GIS Cut Line= 6
1161146.30623748847560.873173234 1161186.8691421847695.547725715
1161208.02559063847791.3969474431161218.69648296847832.150990818
1161237.01657288847890.2595297631161257.46199407847946.762488499
#Sta/Elev= 30
9799.0291078.1549802.8091075.7829843.9261054.8929854.2061048.8839861.0581045.328
9874.7641039.652 9888.471035.2849898.7491030.4059902.1751029.8369912.4551029.308
9922.7341028.2289937.6531025.6179949.9591022.8459960.0551021.0759983.6121017.503
9990.3431017.03610003.781017.29210013.84 1018.16 10030.61020.51610040.691022.951
10079.971037.051 10098.61044.416 10115.81051.78910146.851065.96810157.321069.035
10164.29 1069.2210171.271068.67110174.761069.78510195.691080.35610200.981081.652
#Mann= 3 , 0 , 0
9799.029    0.12       09799.029    0.12       010200.98    0.12       0
#XS Ineff= 2 , 0
       0                               0
Bank Sta=9799.029,10200.98
Exp/Cntr=0.3,0.1

Type RM Length L Ch R = 1 ,7180.705,49.329700,49.329700,49.329700
XS GIS Cut Line= 6
1161101.49966839847566.8329989611161136.06767509847682.791350295
1161159.40603323847806.1169421861161169.04168152847847.289921239
1161184.58542783847897.9877618151161205.44647854847954.335869638
#Sta/Elev= 30
9799.0151079.0029813.7811070.4299844.7841053.6759855.1181047.6389868.7951040.034
9896.0221027.5139902.8291024.6929911.4791022.0059950.0591013.3769956.7721012.122
9966.8051010.7599980.1251009.36410000.111008.13610006.771008.37210026.76 1010.38
10043.421011.16210046.771011.63210100.911032.61210114.641036.60410124.931039.321
10140.89 1045.3110149.111048.84810156.111052.184 10170.11060.576 10173.61062.464
 10177.11064.034 10180.61064.662 10187.61064.95710198.091064.71810200.981065.697
#Mann= 3 , 0 , 0
9799.015    0.12       09799.015    0.12       010200.98    0.12       0
#XS Ineff= 2 , 0
       0                               0
Bank Sta=9799.015,10200.98
Exp/Cntr=0.3,0.1

Type RM Length L Ch R = 1 ,7131.375,49.329600,49.329600,49.329600
XS GIS Cut Line= 6
1161048.87064078847576.8288378481161088.47874042847699.860432192
1161109.09147802847803.9955968851161118.57536484847841.096600777
1161135.98944602847893.6721907521161162.95713019 847961.29539268
#Sta/Elev= 30
9799.0181071.3789824.1251060.1579844.932 1049.889858.8031044.2579868.7391039.907
9882.9671032.4869886.3861030.9769893.2231028.6069923.9921014.3869944.261 1008.51
9967.8321004.8729988.6591000.9719994.479 1000.2610001.141000.03810007.811000.316
10021.151001.80410025.831003.21810044.651010.69710051.421013.012 10054.81013.372
10061.581013.00910068.351013.02110075.171013.94410102.821021.41510141.121031.002
10144.651032.14710155.241037.47110190.561056.79910197.631059.97610200.971060.943
#Mann= 3 , 0 , 0
9799.018    0.12       09799.018    0.12       010200.97    0.12       0
#XS Ineff= 2 , 0
       0                               0
Bank Sta=9799.018,10200.97
Exp/Cntr=0.3,0.1

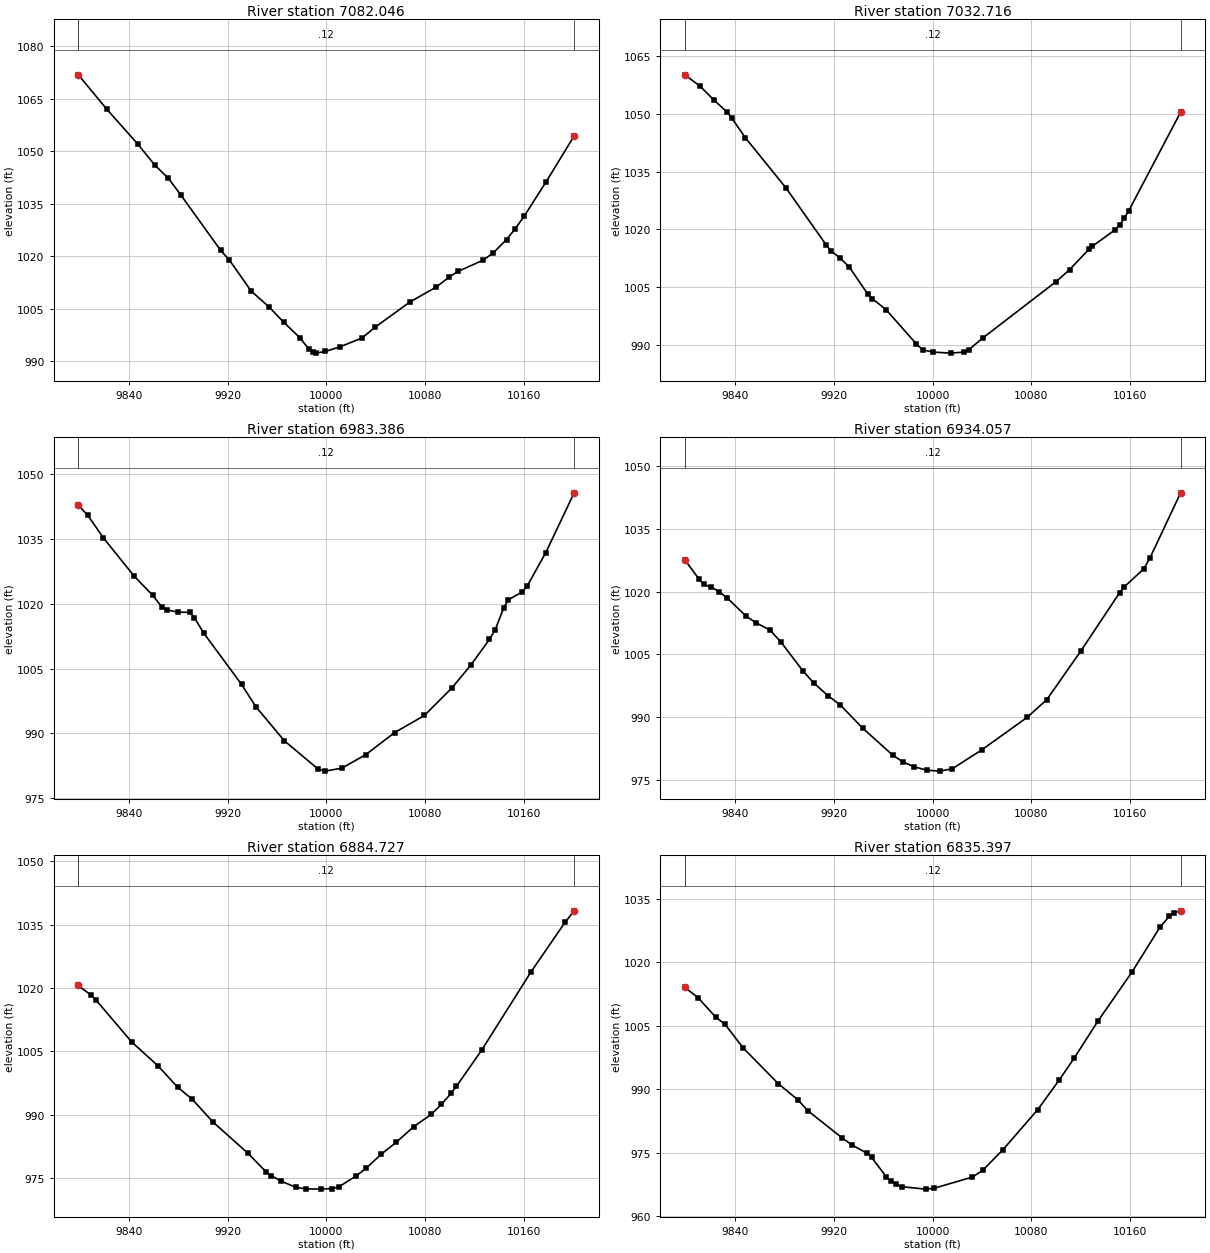
Type RM Length L Ch R = 1 ,7082.046,49.329700,49.329700,49.329700
XS GIS Cut Line= 6
1160977.73941882 847595.495637071161040.76821301 847749.65274877
1161054.98587855847779.9182792871161064.19813339847798.675539232
1161100.02221308 847888.513618321161133.89455987847965.783708834
#Sta/Elev= 30
9799.0171071.7779822.2341061.9089847.0451052.0859861.2231045.9369871.8561042.316
9881.9351037.587 9914.391021.6939921.4791018.9349939.201 1010.069953.379 1005.63
9965.5611001.1779978.477996.81099985.726993.61419989.351992.58229991.438992.3737
9999.138992.851610011.22994.174310029.16 996.72110039.49999.740210068.011007.012
 10089.21011.241 10099.81014.10510106.861015.69810127.181018.89710135.38 1020.97
10146.131024.77710153.291027.90210160.461031.44410178.371041.31610200.981054.372
#Mann= 3 , 0 , 0
9799.017    0.12       09799.017    0.12       010200.98    0.12       0
#XS Ineff= 2 , 0
       0                               0
Bank Sta=9799.017,10200.98
Exp/Cntr=0.3,0.1

Type RM Length L Ch R = 1 ,7032.716,49.329600,49.329600,49.329600
XS GIS Cut Line= 6
1160920.59064353847625.5474111071160974.70986942847735.383247745
  1161011.666709847803.5548469861161012.65082356847805.295972637
1161044.04628172847862.5142549011161105.37846812847982.475399117
#Sta/Elev= 30
 9799.011060.0339811.4111057.0919822.3831053.5769833.3551050.3819837.0131048.891
9847.9851043.7979880.9031030.813 9913.821015.9299917.4771014.462 9924.861012.628
9932.3241010.2899947.2521003.3289950.9841002.101 9962.18999.24779986.772990.3666
9992.035988.805610000.49988.266110014.48987.993510025.71988.276810029.45988.9066
10040.68991.929910100.031006.49910111.081009.63410126.481014.82110129.511015.671
 10148.11019.96410151.621021.195 10155.31022.89410158.98 1024.88   102011050.364
#Mann= 3 , 0 , 0
 9799.01    0.12       0 9799.01    0.12       0   10201    0.12       0
#XS Ineff= 2 , 0
       0                               0
Bank Sta=9799.01,10201
Exp/Cntr=0.3,0.1

Type RM Length L Ch R = 1 ,6983.386,49.329700,49.329700,49.329700
XS GIS Cut Line= 6
1160867.97395339847656.1707264731160923.74902637847755.642860298
1160969.13994365847828.6209748381160970.20654555847830.312826014
1161021.51436181847910.9277226821161074.29044008848001.045537364
#Sta/Elev= 30
9799.015 1042.77 9806.751040.3979819.2831035.2449844.3641026.341 9859.411021.918
9866.9321019.1689870.6941018.5799879.6571018.0569889.5011017.9989893.0741016.767
9900.7851013.1659931.361 1001.349942.952 996.1939966.134988.28489993.179 981.833
    9999981.300910012.58981.984710032.03 985.10410055.36990.197910079.58994.1646
 10101.91000.53610117.111005.77610132.321011.74210136.951013.96110143.731018.944
10147.531020.87910158.941022.74910162.921024.08710177.951031.80510200.99 1045.63
#Mann= 3 , 0 , 0
9799.015    0.12       09799.015    0.12       010200.99    0.12       0
#XS Ineff= 2 , 0
       0                               0
Bank Sta=9799.015,10200.99
Exp/Cntr=0.3,0.1

Type RM Length L Ch R = 1 ,6934.057,49.329700,49.329700,49.329700
XS GIS Cut Line= 6
1160817.65837904847692.3064589261160849.45303626847745.653221109
1160885.67734554847801.1507187341160909.94336891847834.397635533
1160975.11809219847915.6960682311161045.40570035848022.882407615
#Sta/Elev= 30
9799.0191027.5849810.6391022.9259814.4581021.6849820.5351021.0269826.9431019.946
9833.5551018.4149848.8321014.0919856.4711012.5829868.104 1010.799877.1271007.877
9895.1351000.9019903.365998.22079915.119995.11769925.147992.8939  9943.1987.4108
9967.471980.95259975.942979.28379985.151978.11669995.429977.3334 10005.6977.1101
10015.78977.656210039.71982.169710076.58989.948210092.49994.174610120.34  1005.9
10151.561019.73710155.481021.14910171.021025.39410176.091027.98210200.991043.565
#Mann= 3 , 0 , 0
9799.019    0.12       09799.019    0.12       010200.99    0.12       0
#XS Ineff= 2 , 0
       0                               0
Bank Sta=9799.019,10200.99
Exp/Cntr=0.3,0.1

Type RM Length L Ch R = 1 ,6884.727,49.329600,49.329600,49.329600
XS GIS Cut Line= 6
1160779.52561117847722.8344152941160812.92166531847776.360231654
1160845.51140793847824.7716476631160892.27690795847890.349225151
1160967.62088687847992.8176134911161008.73147494848052.906302885
#Sta/Elev= 30
9799.0071020.5999809.5921018.2379813.459 1017.119842.2711007.2239863.7681001.518
9879.588996.48769891.453993.63539907.929 988.3259936.663980.82149951.348976.4105
9955.377975.55779963.436974.25559975.524972.76979983.582972.4244 9995.67972.3637
 10004.4972.500510009.94972.849410024.13975.477510032.27977.289210044.49980.6102
 10056.7983.447710070.86987.147310085.21990.087310093.35992.4313 10101.5995.1587
10105.57996.728510125.931005.25610165.741023.71210193.561035.54810200.991038.287
#Mann= 3 , 0 , 0
9799.007    0.12       09799.007    0.12       010200.99    0.12       0
#XS Ineff= 2 , 0
       0                               0
Bank Sta=9799.007,10200.99
Exp/Cntr=0.3,0.1

Type RM Length L Ch R = 1 ,6835.397,49.329700,49.329700,49.329700
XS GIS Cut Line= 6
1160740.87834923847750.2090542751160775.76811294847804.827714365
1160831.75564629847885.9626508881160868.10841678847944.143864345
1160933.47838301848029.9947759821160969.65590381848080.422299418
#Sta/Elev= 30
9799.014 1014.059809.7411011.6389823.9041007.089 9831.691005.3239846.308999.7722
 9874.77991.34599890.714987.51639898.687984.9708 9926.59978.52519934.562976.8662
 9946.52974.94589950.507973.93749962.402 969.3429966.308968.32469970.152967.5463
 9975.37 967.0069994.248966.446710000.99966.639210032.18969.299710040.42970.8479
10056.92975.748710085.06985.179710102.28992.091110114.65997.3436 10133.81006.045
10161.74 1017.7710184.261028.28310191.871030.85510195.911031.66310200.981032.125
#Mann= 3 , 0 , 0
9799.014    0.12       09799.014    0.12       010200.98    0.12       0
#XS Ineff= 2 , 0
       0                               0
Bank Sta=9799.014,10200.98
Exp/Cntr=0.3,0.1

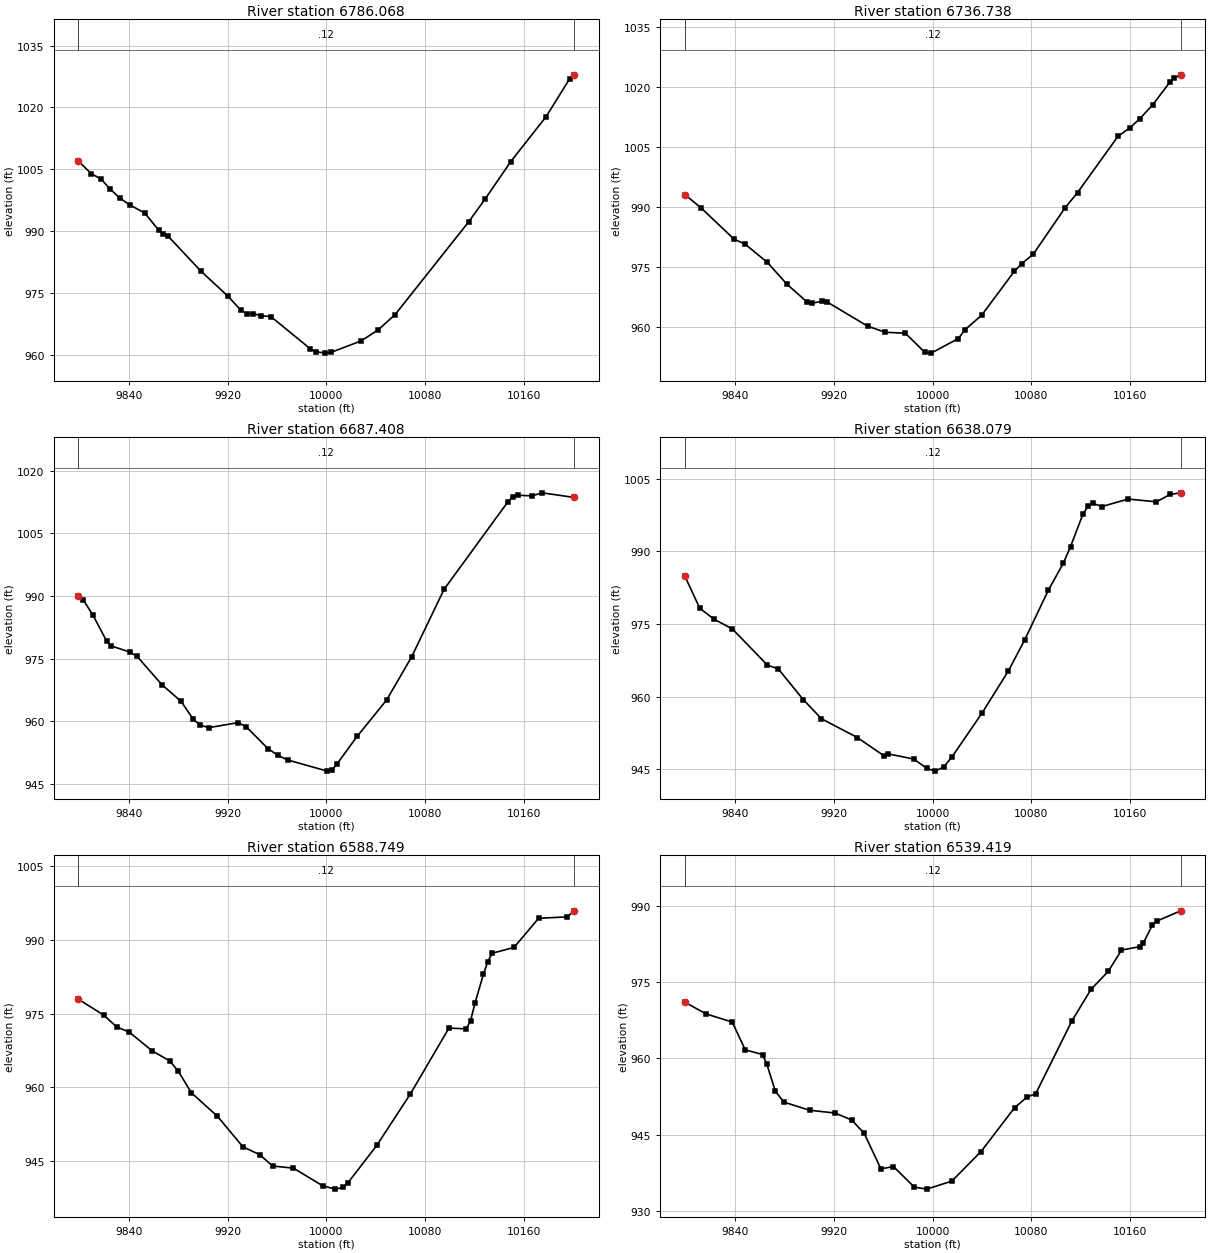
Type RM Length L Ch R = 1 ,6786.068,49.329700,49.329700,49.329700
XS GIS Cut Line= 6
1160688.15567071847788.5960290951160727.36062535847849.934174675
1160760.72793394847894.1294871211160859.17937892847991.940708131
1160897.44728814848037.4235682831160942.35593615848097.949822244
#Sta/Elev= 30
9799.0571007.0129809.5441003.9679817.3311002.6929825.118 1000.159832.906997.9993
9840.693996.39849852.849994.43629864.056990.3213 9867.95989.38739871.854988.7991
9898.427980.34249920.207974.30829930.697970.91639935.578970.05019940.459970.0638
9947.288969.53899955.102969.34489987.045961.53999991.469960.8238    9999960.4828
10004.22960.698910028.55963.478410042.16966.144410055.78 969.795 10115.6 992.345
10129.07997.9298 10149.51006.858 10178.11017.71610197.381026.98210200.971027.906
#Mann= 3 , 0 , 0
9799.057    0.12       09799.057    0.12       010200.97    0.12       0
#XS Ineff= 2 , 0
       0                               0
Bank Sta=9799.057,10200.97
Exp/Cntr=0.3,0.1

Type RM Length L Ch R = 1 ,6736.738,49.329600,49.329600,49.329600
XS GIS Cut Line= 6
 1160658.9420278847828.8845444471160697.06494578 847891.39634613
1160729.62899586847935.6526927991160758.12434551847965.568204446
1160832.06492434848029.1555986671160913.96017058 848135.98697387
#Sta/Elev= 30
9799.095993.02719812.211 989.6969839.111981.83619847.831980.65889866.011976.0349
9881.926970.58319898.219966.12799902.292965.86159910.439966.32989914.512966.1331
9947.187960.12059961.457958.5746 9977.77958.33719993.515953.60299998.763953.3585
10020.81957.005610026.15959.202710039.77962.868710066.08 973.79110072.08975.7204
10081.46978.081510107.11989.622610117.38993.512510150.171007.57610159.841009.715
 10167.9 1011.9910178.391015.489 10192.11021.07810195.321022.06910200.931022.959
#Mann= 3 , 0 , 0
9799.095    0.12       09799.095    0.12       010200.93    0.12       0
#XS Ineff= 2 , 0
       0                               0
Bank Sta=9799.095,10200.93
Exp/Cntr=0.3,0.1

Type RM Length L Ch R = 1 ,6687.408,49.329700,49.329700,49.329700
XS GIS Cut Line= 6
1160641.41750238847849.6023496561160677.56527244 847914.20368236
1160705.94968427847960.340962203 1160748.4258865848020.662653602
1160793.64558163 848084.338385111160859.02155742848187.204499053
#Sta/Elev= 30
9799.026990.12239803.155988.98729810.675985.54869821.953979.23059825.713978.0637
9840.751976.60279846.568975.59279866.724968.80049882.328964.7992  9892.2960.4998
9897.736959.13039904.722958.49679928.608959.71489935.226958.6852  9952.7953.4943
 9960.73951.87729968.761950.764210000.84948.096910004.86948.472510008.88949.8741
10024.98 956.39410048.93965.112510069.24 975.45410095.47991.591610147.321012.586
10151.211013.779 10155.11014.14210166.761013.97810174.991014.71310200.981013.607
#Mann= 3 , 0 , 0
9799.026    0.12       09799.026    0.12       010200.98    0.12       0
#XS Ineff= 2 , 0
       0                               0
Bank Sta=9799.026,10200.98
Exp/Cntr=0.3,0.1

Type RM Length L Ch R = 1 ,6638.079,49.329700,49.329700,49.329700
XS GIS Cut Line= 6
1160621.41017614847858.7174408791160680.74631187 847979.66833324
1160692.91868162 848009.014968131160729.44283741848109.577984137
1160752.46670932 848159.740141961160785.65461575848225.048532932
#Sta/Elev= 30
9799.018 984.9279811.151978.26059822.662976.0131 9837.56973.99089865.966966.5152
9874.805965.71719895.201959.34059909.819955.42919938.904951.53959960.186947.8276
9963.767948.16529984.617947.10129995.021945.200210001.95944.598910008.88945.4586
10015.81947.596710040.24956.709110061.43965.347110074.47971.680810093.68981.9513
10105.93987.601710111.73991.003710121.66997.642910126.17999.465410129.82 999.942
10137.18999.278710158.351000.83510181.341000.26110192.381001.77710200.98 1002.12
#Mann= 3 , 0 , 0
9799.018    0.12       09799.018    0.12       010200.98    0.12       0
#XS Ineff= 2 , 0
       0                               0
Bank Sta=9799.018,10200.98
Exp/Cntr=0.3,0.1

Type RM Length L Ch R = 1 ,6588.749,49.329600,49.329600,49.329600
XS GIS Cut Line= 6
1160588.96718245847864.0250639961160632.58884142847968.366313747
1160646.49214276848012.5654061031160676.70753767848130.037978588
1160697.80227404 848187.048041781160722.23918816848242.248567731
#Sta/Elev= 30
9799.026977.8984 9819.48974.70329830.241972.25649840.114971.26939858.937967.4156
9873.033965.41039880.079963.29759890.649958.93349911.789954.15939932.433947.9688
 9946.19946.36039956.508944.07719973.412943.64139997.025940.075710007.13939.3885
10013.87939.732410017.24940.561410040.92 948.23810068.27958.717510099.48972.0544
10113.47971.881510116.97973.503110120.65977.193710127.47982.996410130.96985.5215
10134.46987.218610152.24988.403210172.13994.3062 10195.3994.598510200.97995.8228
#Mann= 3 , 0 , 0
9799.026    0.12       09799.026    0.12       010200.97    0.12       0
#XS Ineff= 2 , 0
       0                               0
Bank Sta=9799.026,10200.97
Exp/Cntr=0.3,0.1

Type RM Length L Ch R = 1 ,6539.419,49.329700,49.329700,49.329700
XS GIS Cut Line= 6
1160547.40873841847873.2302449011160569.56789961847929.136595277
1160586.37906479847979.3754932231160633.00134781848157.772457942
1160647.67707539848199.6177444961160670.77279608848255.084207939
#Sta/Elev= 30
9799.027971.06539816.308968.76389837.483967.1553 9848.07961.68619862.127960.7683
9865.587958.82759872.506 953.5029879.426951.40029900.183 949.8069920.756949.2645
9934.302947.88449944.463945.25769958.009938.26559968.169 938.7399985.103934.6691
9995.263934.287110015.54935.870410039.19941.685410066.39950.315910076.64952.4326
10083.47 953.04710112.82967.372110128.43973.628710142.33977.127910153.03981.3189
10167.94981.9937 10170.8982.718810177.91986.176110181.46 986.99810200.98989.0419
#Mann= 3 , 0 , 0
9799.027    0.12       09799.027    0.12       010200.98    0.12       0
#XS Ineff= 2 , 0
       0                               0
Bank Sta=9799.027,10200.98
Exp/Cntr=0.3,0.1

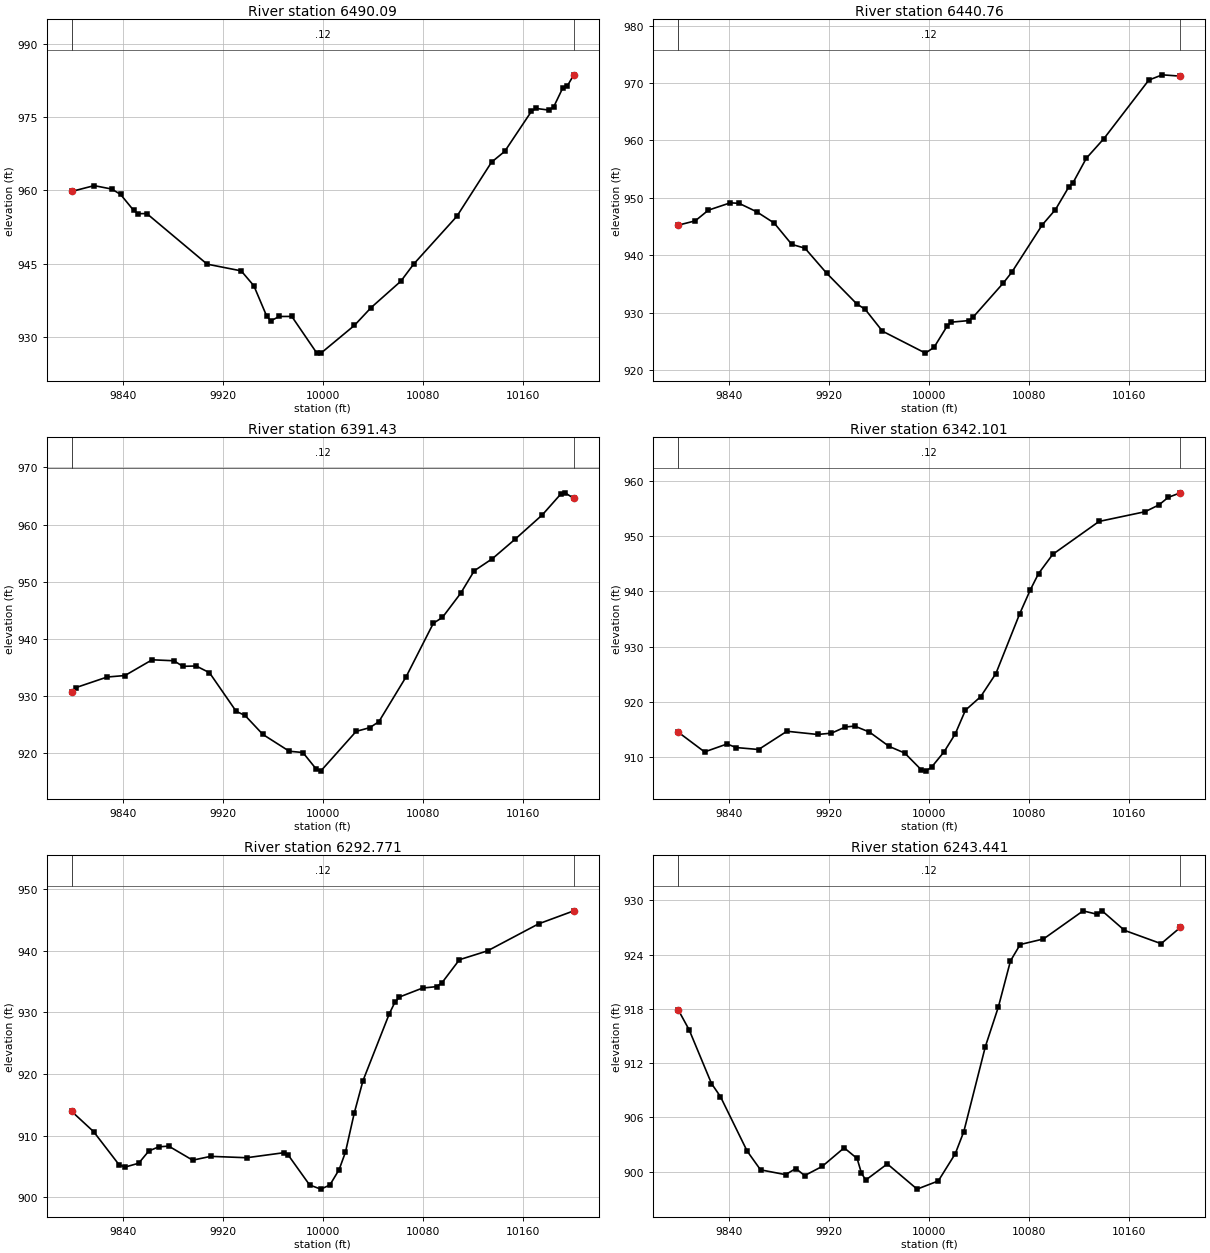
Type RM Length L Ch R = 1 , 6490.09,49.329700,49.329700,49.329700
XS GIS Cut Line= 6
1160502.20751069847882.297731391 1160523.6946378 847938.54614912
1160542.25603178 847996.440914851160578.25813653848152.171625353
 1160598.3195696848209.694629898 1160621.5973971848265.086643755
#Sta/Elev= 30
9799.026959.80049817.053960.99099831.101960.28969838.125959.20219848.662955.9173
9852.174955.24999859.198  955.269907.433944.91169934.722943.53179944.868940.4764
9955.015934.33259958.397933.29679965.162934.18929975.222   934.29995.254926.6867
9998.593926.683410025.33 932.35910038.77936.025310062.55941.427310072.74944.9098
10107.32954.701210135.12 965.80310145.66968.010510167.01976.198710170.57976.8054
10181.24976.4575 10184.8977.098510191.92980.900510195.48981.302610200.97983.6866
#Mann= 3 , 0 , 0
9799.026    0.12       09799.026    0.12       010200.97    0.12       0
#XS Ineff= 2 , 0
       0                               0
Bank Sta=9799.026,10200.97
Exp/Cntr=0.3,0.1

Type RM Length L Ch R = 1 , 6440.76,49.329600,49.329600,49.329600
XS GIS Cut Line= 6
1160445.41849682847896.1808866181160482.82480213847994.233707049
1160512.25890033848086.6951842481160536.97975149848161.689206297
1160559.47899835848218.311324691 1160583.9262837848273.201196399
#Sta/Elev= 30
9799.021  945.22 9812.72945.97679823.254947.84159840.811949.12029847.834949.0284
 9861.88 947.5629875.926945.59199889.972941.87269900.506941.2186 9917.79936.8798
9941.892931.52769948.779930.54499962.551926.75239996.984922.919910003.88923.9341
10014.24927.594110017.69 928.31710031.51928.588110034.97929.149610059.15935.0999
10066.06937.007310090.46945.269210101.05947.939610111.65951.854110115.18952.6493
10125.77956.894810139.89960.322410175.79970.515410186.56971.429910200.98   971.2
#Mann= 3 , 0 , 0
9799.021    0.12       09799.021    0.12       010200.98    0.12       0
#XS Ineff= 2 , 0
       0                               0
Bank Sta=9799.021,10200.98
Exp/Cntr=0.3,0.1

Type RM Length L Ch R = 1 , 6391.43,49.329700,49.329700,49.329700
XS GIS Cut Line= 5
1160386.98187752847915.5940196961160464.68405564848099.866396733
1160465.30322779848101.7681395791160473.08635904848121.044643725
1160550.28958832848282.761180835
#Sta/Elev= 30
9799.015930.69669802.519931.51189827.443 933.3549841.685933.61549863.426936.3641
9880.852936.19599887.973935.22499898.655935.28299909.336934.1091  9930.7927.3617
9937.821926.63489952.063923.32429973.198920.38539984.109920.1607 9994.79917.2669
9998.351916.909210026.74923.854310037.65924.505310044.92 925.54510066.73933.3932
10088.55942.754510095.82943.773710110.36947.976710121.27951.916910135.81954.0381
10154.17957.4749 10175.8961.699310190.34965.279410193.98965.542310200.99964.5718
#Mann= 3 , 0 , 0
9799.015    0.12       09799.015    0.12       010200.99    0.12       0
#XS Ineff= 2 , 0
       0                               0
Bank Sta=9799.015,10200.99
Exp/Cntr=0.3,0.1

Type RM Length L Ch R = 1 ,6342.101,49.329700,49.329700,49.329700
XS GIS Cut Line= 6
1160326.84225833 847952.031266381160387.10616527848079.069157865
1160405.95920377848107.5380613481160437.41781034848141.128856034
1160458.05759039848169.4072288341160526.83125281848298.200334732
#Sta/Elev= 30
9799.068914.49589820.242910.89859838.253912.33959845.458911.69259863.469911.3365
9886.138914.64669910.718914.06259921.811914.30429932.904915.41889940.336915.5822
9952.141914.50589967.881911.90469980.433910.69019993.753907.63139997.451907.4133
10002.12908.203110011.91910.915910020.87 914.177   10029918.467610041.18920.9177
10053.37925.112310072.39935.944210080.99940.329310087.53943.262710098.89946.7422
10135.94952.7081 10172.8954.472710183.86955.709610191.23957.066510200.95 957.898
#Mann= 3 , 0 , 0
9799.068    0.12       09799.068    0.12       010200.95    0.12       0
#XS Ineff= 2 , 0
       09950.066                       0
Bank Sta=9799.068,10200.95
Exp/Cntr=0.3,0.1

Type RM Length L Ch R = 1 ,6292.771,49.329600,49.329600,49.329600
XS GIS Cut Line= 5
1160301.17361897847978.2412563311160359.60108964848107.040510023
1160386.90940898848158.8316711381160387.57504927848160.717651787
1160481.05447813848337.512727653
#Sta/Elev= 30
9799.018913.94079816.632910.64029836.999905.2669 9841.85904.90389852.658905.5191
9860.824907.51499868.766908.18419876.707908.3009 9895.89 906.015  9910.3906.6384
9939.121906.41449968.754 907.2279972.463906.82319989.504901.98999998.425901.3175
10005.71901.981410013.14904.498210018.18 907.319 10025.2913.638610032.21918.9214
10053.27929.781510057.67931.619110061.38932.503810079.94933.962710091.07934.1905
10095.38 934.80210109.42938.5634 10131.9939.996910172.72944.379310200.99946.4972
#Mann= 3 , 0 , 0
9799.018    0.12       09799.018    0.12       010200.99    0.12       0
#XS Ineff= 2 , 0
       09949.018                       0
Bank Sta=9799.018,10200.99
Exp/Cntr=0.3,0.1

Type RM Length L Ch R = 1 ,6243.441,49.329700,49.329700,49.329700
XS GIS Cut Line= 6
1160270.29270513847986.1094699251160321.19693821848110.868751915
1160349.24400215848207.5513771531160364.53164838848250.372879452
1160390.10297512848305.6576495891160419.52581116848358.041575102
#Sta/Elev= 30
9799.016917.91639807.902915.66779825.716909.74949832.872908.30599854.276902.2764
9864.977900.20749885.008899.67659893.252900.35289900.279899.57129914.334900.5873
9931.901902.64029942.289901.4611 9945.74899.84129949.192899.07629966.449900.8606
9990.284898.074910007.26898.979610020.86901.992910027.67904.434110044.92913.8313
10055.37918.228410065.03923.304410072.79925.112310091.45925.728710123.13928.8317
10133.97928.471210138.34928.837310156.27926.6798 10185.6925.206810200.95926.9979
#Mann= 3 , 0 , 0
9799.016    0.12       09799.016    0.12       010200.95    0.12       0
#XS Ineff= 2 , 0
       09968.012        10024.82       0
Bank Sta=9799.016,10200.95
Exp/Cntr=0.3,0.1

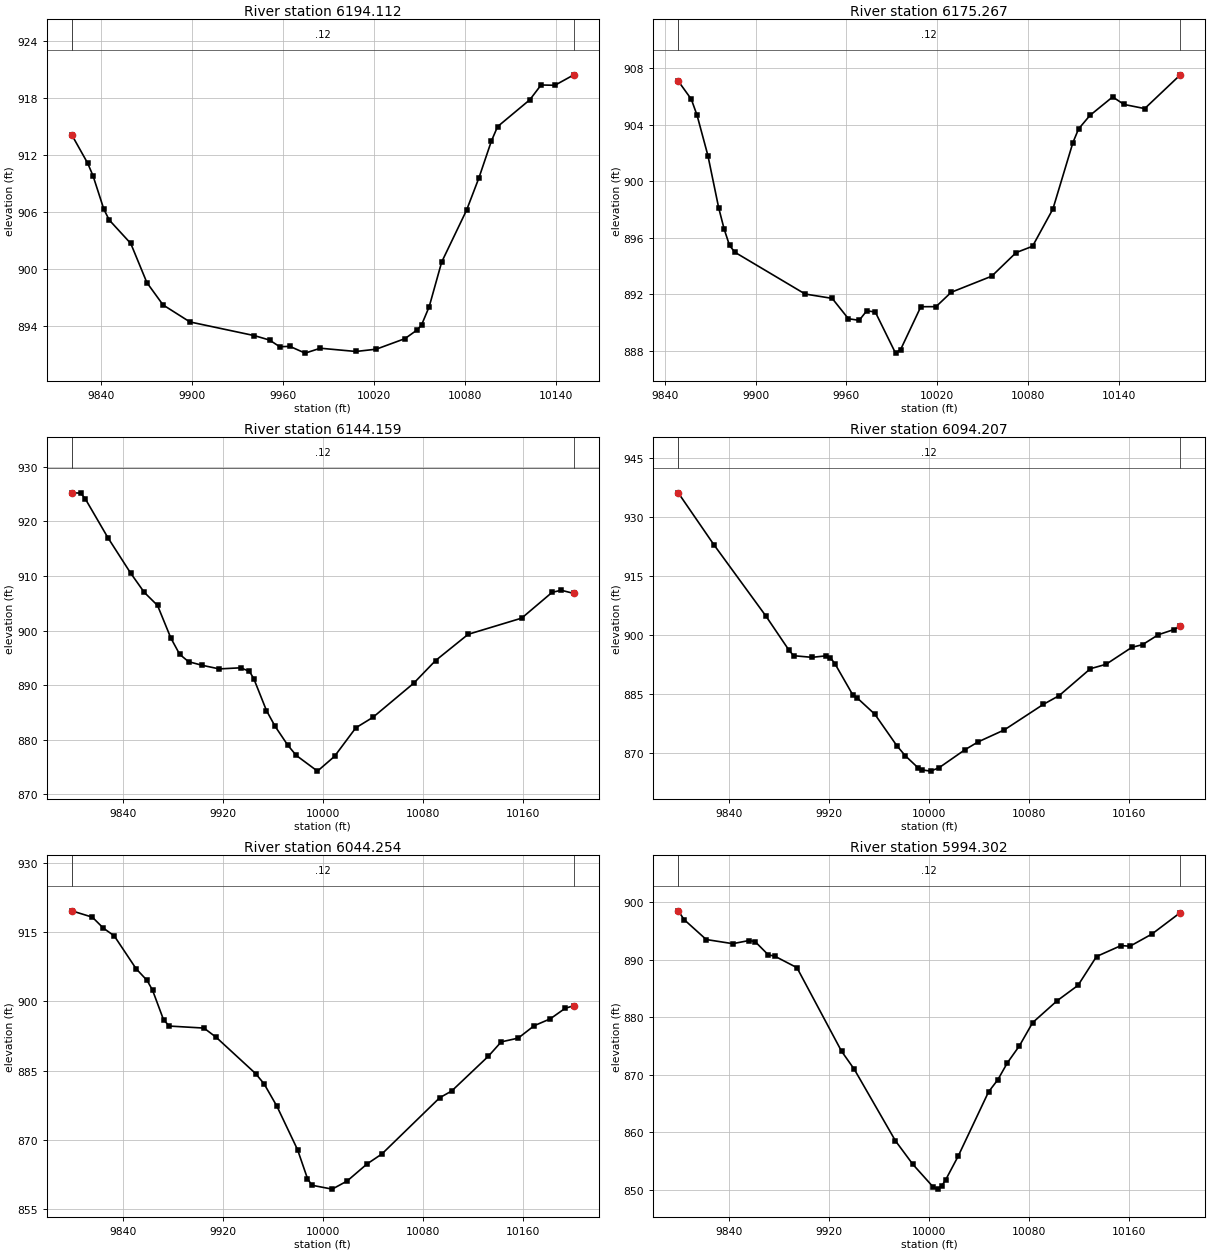
Type RM Length L Ch R = 1 ,6194.112,18.844800,18.844800,18.844800
XS GIS Cut Line= 4
1160235.71384612848017.3516087681160280.41362357 848127.06924431
1160302.08624297848234.0778024641160363.71775427848316.704663813
#Sta/Elev= 30
9821.027914.14119831.542911.13619835.085909.7923 9842.17906.27899845.713905.1487
9859.883902.67459870.511898.54069881.139896.18849898.853894.39059941.319 892.946
9951.304892.47749957.999891.77389964.694891.81119974.736891.09779984.779891.6148
10008.21891.2718 10021.6891.514410040.49892.626910048.68 893.56210051.45894.0743
 10056.5896.014910064.69900.712310081.06906.175910089.24909.601310097.43913.4825
10101.52915.008310122.78917.847410130.17919.404210139.25919.371110151.76920.4763
#Mann= 3 , 0 , 0
9821.027    0.12       09821.027    0.12       010151.76    0.12       0
#XS Ineff= 2 , 0
       0  9962.2        10027.34       0
Bank Sta=9821.027,10151.76
Exp/Cntr=0.3,0.1

Type RM Length L Ch R = 1 ,6175.267,31.107700,31.107700,31.107700
XS GIS Cut Line= 4
1160218.29882398848048.4571092431160269.43959492 848167.04440406
1160282.78066555848234.490927994 1160348.0036777848351.595881626
#Sta/Elev= 30
9848.778907.07579857.416905.78969861.238904.64799868.383901.80689875.529898.1013
9879.102896.61219882.675895.44419886.248894.95889932.696 892.004 9950.56891.6968
9961.279890.25639968.425890.14299973.407890.81979979.066 890.7319992.443887.8227
9995.788 888.07110009.17891.1079 10019.2  891.1110029.23892.126710056.04893.2678
10072.15894.934910083.01895.383310096.49898.022210109.71 902.72110113.46903.6879
10120.97904.643610135.99905.9519 10143.5905.419910157.18905.126710180.72907.5158
#Mann= 3 , 0 , 0
9848.778    0.12       09848.778    0.12       010180.72    0.12       0
#XS Ineff= 2 , 0
       09961.627         10030.6       0
Bank Sta=9848.778,10180.72
Exp/Cntr=0.3,0.1

Type RM Length L Ch R = 1 ,6144.159,49.952500,49.952500,49.952500
XS GIS Cut Line= 6
1160172.95782804848007.6155482481160217.61453276848107.730226512
1160253.84216465848231.6569237141160266.02534719848264.394936365
1160292.38141065848313.0702593081160333.18052063848373.358858768
#Sta/Elev= 30
9799.025 925.2169806.071925.16869809.711924.16979827.909917.01899846.108910.5311
9857.027 907.0019867.688904.59699878.314898.64069885.397895.65379892.481894.3058
9903.106893.65969917.056  892.989934.315893.18439941.219892.52829944.671891.2251
9954.895885.34589961.695882.50549971.896879.03089978.696 877.1489995.696874.2682
10009.34876.9712 10026.4882.198710040.11884.119310072.77 890.36910090.19 894.503
10116.31899.314310159.16902.277610183.52906.998710190.85907.381610200.92906.7948
#Mann= 3 , 0 , 0
9799.025    0.12       09799.025    0.12       010200.92    0.12       0
#XS Ineff= 2 , 0
       0                               0
Bank Sta=9799.025,10200.92
Exp/Cntr=0.3,0.1

Type RM Length L Ch R = 1 ,6094.207,49.952500,49.952500,49.952500
XS GIS Cut Line= 6
1160109.89866174848025.4679978851160148.01167422848091.087047876
1160173.90862845848142.7559168541160200.06928601848227.686437579
 1160208.0814742848245.6871862371160304.75052007 848372.40408382
#Sta/Elev= 30
 9799.06936.11659827.495922.9667 9869.23904.78189887.766896.06689891.436894.6953
9906.115894.28129917.125894.65059920.795894.20669924.465892.66869938.868884.6797
9942.379883.93329956.425879.80979973.982 871.8319980.749869.26629990.885866.2284
9994.264865.6506   10001865.342710007.77866.192210028.45870.761910039.23872.8014
10060.02875.817610091.39882.341310103.91884.534210128.95 891.38410141.46 892.507
10162.12896.820810170.67897.498310183.36900.035410195.71901.337510200.93902.2044
#Mann= 3 , 0 , 0
 9799.06    0.12       0 9799.06    0.12       010200.93    0.12       0
#XS Ineff= 2 , 0
       0                               0
Bank Sta=9799.06,10200.93
Exp/Cntr=0.3,0.1

Type RM Length L Ch R = 1 ,6044.254,49.952600,49.952600,49.952600
XS GIS Cut Line= 6
 1160008.7358923848090.2168448211160100.30230083848188.359544349
1160130.63824742848213.6726731261160181.65762598848248.258428143
1160215.57445719848278.2992427281160295.02249025848369.715229667
#Sta/Elev= 30
9799.045919.58559815.519918.21319824.285915.8533 9833.05914.16379850.581907.0489
9859.347904.52369863.729902.40049872.547895.99049877.167894.65949904.887894.2237
9914.721892.21229946.176884.38779953.012882.15059963.254877.31749979.805867.9012
9987.721861.6763 9991.19860.2322 10007.5859.388910019.42861.1354 10035.4864.8343
10047.28866.991110093.57879.155110103.17880.618910132.53888.138610142.79891.2356
 10156.4892.053610169.21894.739310182.02896.213710194.06898.514510200.94899.0539
#Mann= 3 , 0 , 0
9799.045    0.12       09799.045    0.12       010200.94    0.12       0
#XS Ineff= 2 , 0
       0                               0
Bank Sta=9799.045,10200.94
Exp/Cntr=0.3,0.1

Type RM Length L Ch R = 1 ,5994.302,49.952500,49.952500,49.952500
XS GIS Cut Line= 6
 1159975.4294485848173.3906687941160091.38057043848263.143313754
1160123.14086684848275.1723896481160174.05127091848280.516882861
1160205.18506284848295.7682898161160299.18860015 848391.82889911
#Sta/Elev= 30
9799.088898.51769803.814896.98559821.493893.52889842.701892.80829855.628 893.349
9860.537893.18139871.138890.87029876.308  890.649894.097888.63439929.772874.1163
9940.003870.96549972.892 858.5499986.872854.443110003.33850.462810006.61850.1421
10009.89850.687210013.18851.785210023.17855.888210047.42 867.04310054.87 869.161
10062.52872.1073 10072.1875.039410082.75879.091810102.32882.888610119.04885.5648
10133.83890.576210153.54892.481110160.57  892.3610178.16894.4791 10200.9898.2054
#Mann= 3 , 0 , 0
9799.088    0.12       09799.088    0.12       0 10200.9    0.12       0
#XS Ineff= 2 , 0
       0                               0
Bank Sta=9799.088,10200.9
Exp/Cntr=0.3,0.1