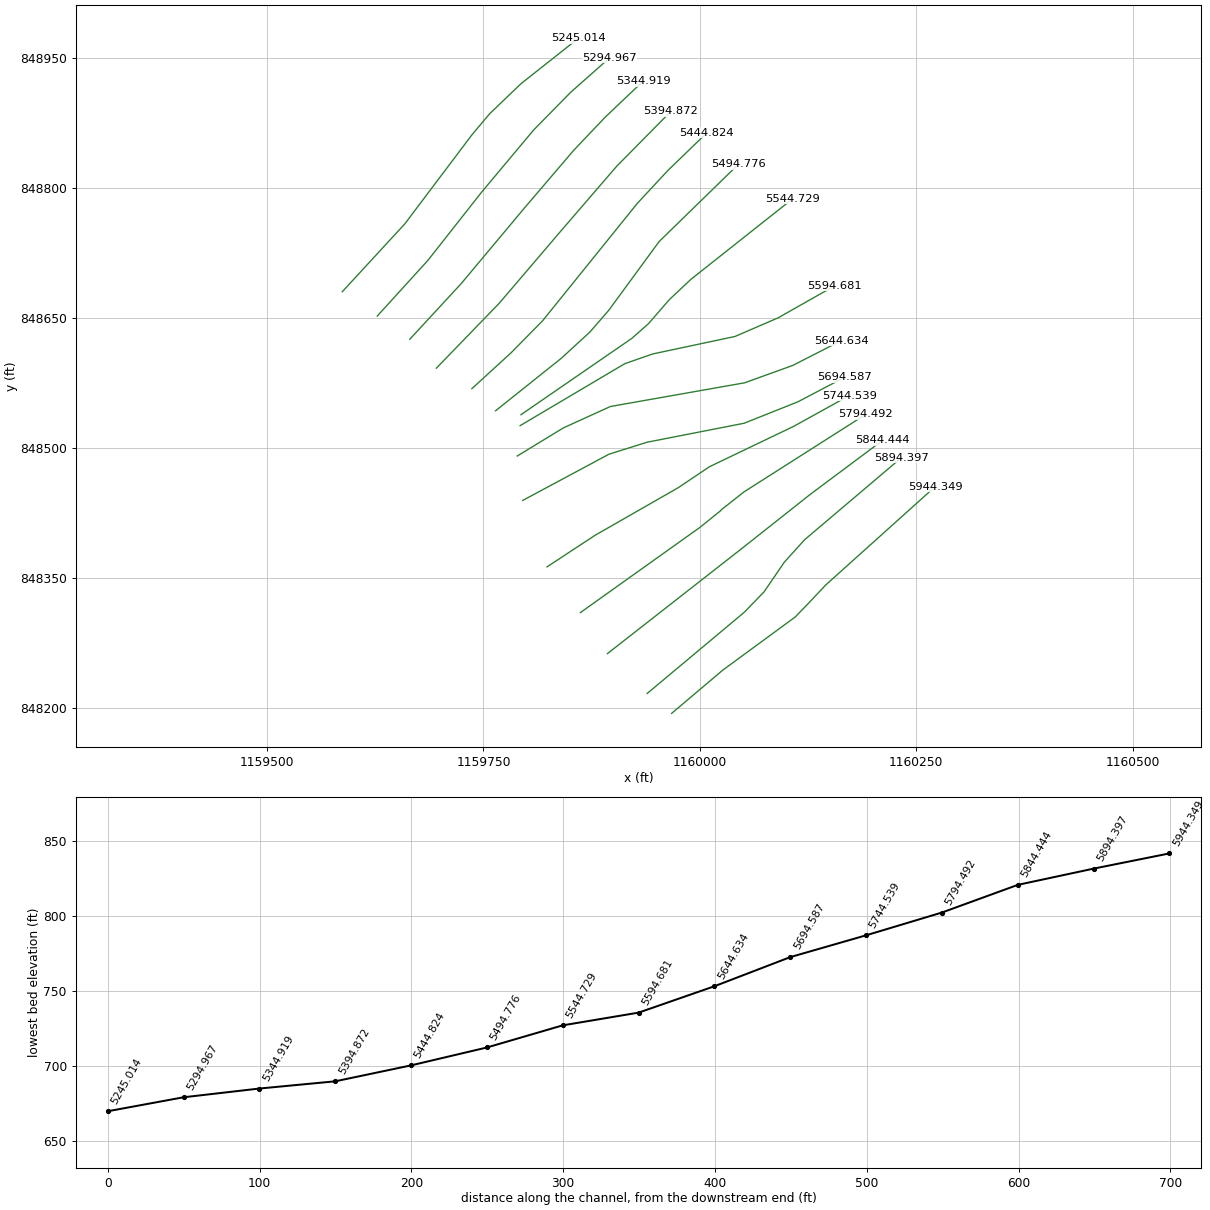
HEC-RAS study 177_ras.prj: 177

--- 177_ras.g01 (geometry) --- (continued)

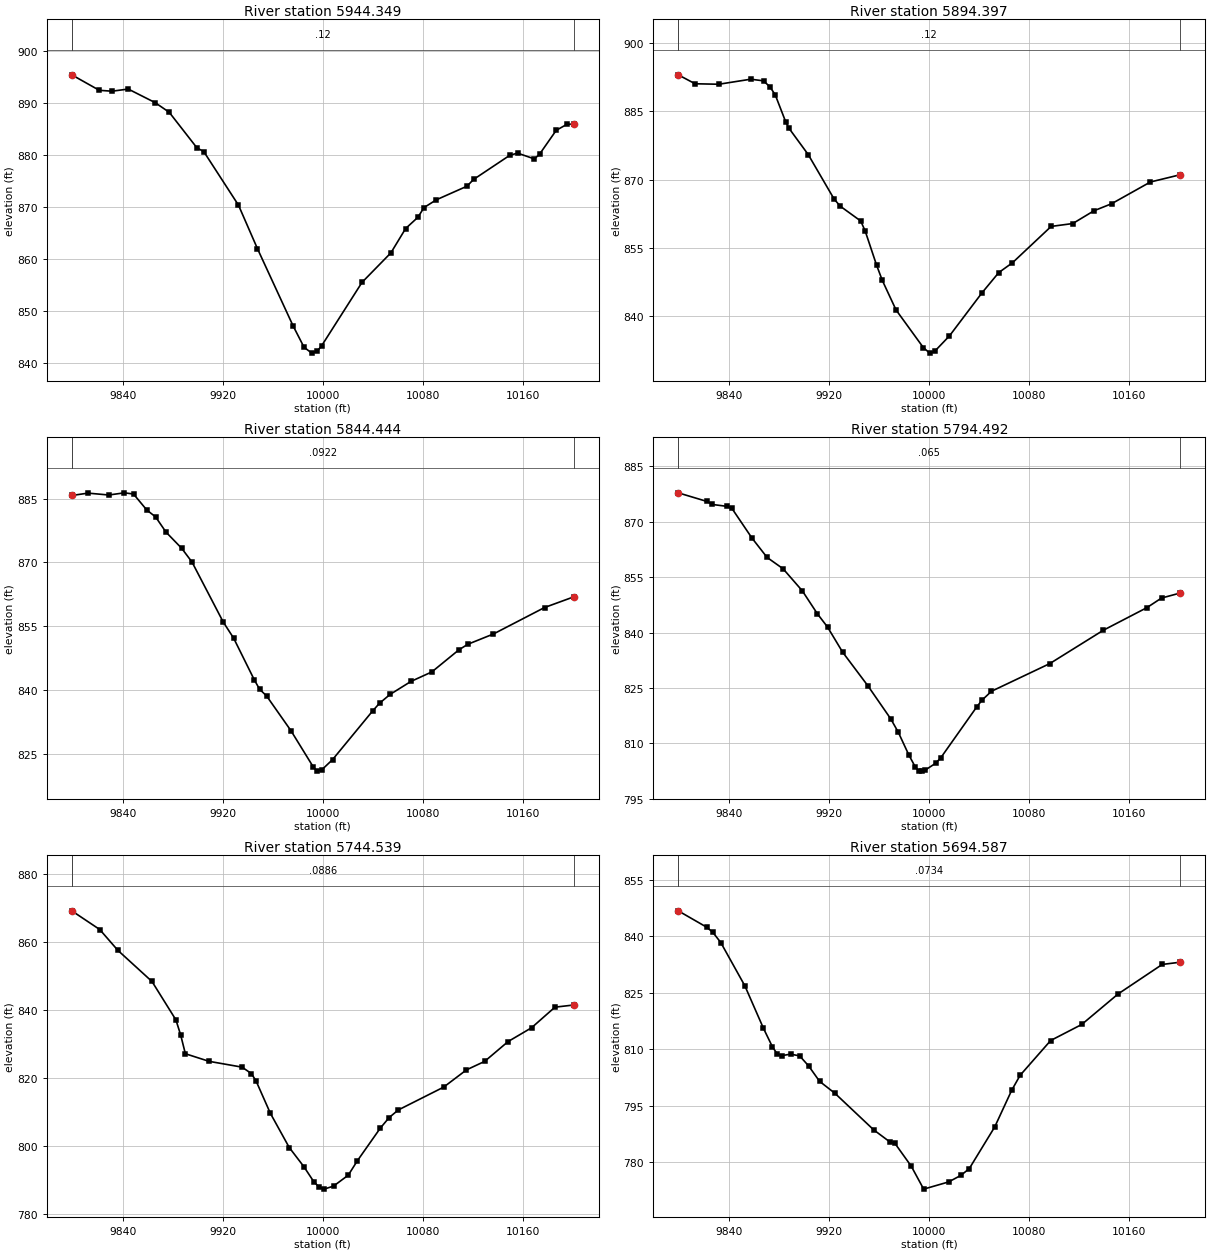
Type RM Length L Ch R = 1 ,5944.349,49.952500,49.952500,49.952500
XS GIS Cut Line= 6
1159967.37987349 848193.307732351160026.57268182848243.347217247
1160110.06918942848304.5780004331160123.20573563848318.141785985
 1160145.4801936848341.6985975621160271.58107689848455.014421445
#Sta/Elev= 30
9799.066895.49859821.105892.51749831.269892.34599844.273892.76139865.754 890.153
9877.046888.29639899.237881.44769904.785880.70229932.525   870.49947.697862.0305
9976.176847.1939 9984.98843.05869991.177841.92199995.745842.35819999.139843.3617
10031.42855.550810054.53 861.23110066.31865.910110076.13868.072910081.04869.9462
10090.85871.4336 10115.4874.055410120.69875.357210149.75880.020110155.98880.4217
10169.39879.309110173.62880.255310186.85884.813810195.68886.006610200.96885.9759
#Mann= 3 , 0 , 0
9799.066    0.12       09799.066    0.12       010200.96    0.12       0
#XS Ineff= 2 , 0
       0                               0
Bank Sta=9799.066,10200.96
Exp/Cntr=0.3,0.1

Type RM Length L Ch R = 1 ,5894.397,49.952500,49.952500,49.952500
XS GIS Cut Line= 6
1159939.06482483848216.2483368951160051.34860664 848310.13915066
1160074.15600625848333.7072477871160097.66525509848368.107360293
1160121.17080954848394.0524409081160232.54778055 848488.46173622
#Sta/Elev= 30
 9799.06893.04519812.546891.07699831.509890.97039857.081892.0805 9867.31891.7211
 9872.42890.41059876.697888.6459 9885.25  882.579887.768881.25579903.112875.4877
 9923.74865.73879928.684864.13759945.124860.86729948.743858.62859957.874851.1025
 9962.44847.7686  9973.4 841.2839995.262832.997210000.36831.7762 10004.3832.1662
10016.17835.574610042.28845.077510055.64849.512410066.61851.674210097.56859.6713
10114.87860.305610131.83863.116410145.92 864.66310176.99869.449510200.95871.0525
#Mann= 3 , 0 , 0
 9799.06    0.12       0 9799.06    0.12       010200.95    0.12       0
#XS Ineff= 2 , 0
       0                               0
Bank Sta=9799.06,10200.95
Exp/Cntr=0.3,0.1

Type RM Length L Ch R = 1 ,5844.444,49.952500,49.952500,49.952500
XS GIS Cut Line= 5
1159893.25497572848262.3807930521160050.78674402848385.596621363
1160052.35296575848386.8403856071160127.28119539848446.142484932
1160210.97676577848508.612529985
#Sta/Elev= 30
9799.004885.71089811.984886.26819828.645885.8269 9841.14886.33869848.439886.0586
 9859.09882.29449866.132880.67429874.462877.10469886.958873.31969895.288870.0646
9920.279855.9742 9928.61852.18999945.271842.31989949.436840.17119954.944838.6235
9974.427830.47619992.221 821.9979995.253820.94339999.421821.321510007.79823.6462
10039.84 835.06810045.45836.908410053.82838.959810070.55842.018610087.29844.2551
10109.02849.459210116.15850.759610136.62853.171410177.55  859.3910200.99861.9004
#Mann= 3 , 0 , 0
9799.004  0.0922       09799.004  0.0922       010200.99  0.0922       0
#XS Ineff= 2 , 0
       0                               0
Bank Sta=9799.004,10200.99
Exp/Cntr=0.3,0.1

Type RM Length L Ch R = 1 ,5794.492,49.952500,49.952500,49.952500
XS GIS Cut Line= 6
1159861.94908492848309.7362768651160000.52023717848408.508916516
1160023.69867363 848427.235672691160025.02740135848428.730491289
1160050.71601322848449.0137084471160191.76612498848538.821143452
#Sta/Elev= 30
9799.031877.86369821.829875.54949826.441874.70969837.944874.20349841.973873.6587
9858.089865.59599870.176860.36449882.965 857.2989898.379851.31629910.466 845.086
9918.524841.52999930.611834.72569950.794825.63229969.202816.62829975.198813.0257
9983.523806.95579988.744803.6468 9992.07802.50539993.964802.50439996.288802.6874
10004.98804.613110009.16806.099810038.09819.945910042.27821.746510049.76824.1254
10096.44831.619510139.22840.633110174.22846.778410185.89849.372310200.94850.7365
#Mann= 3 , 0 , 0
9799.031   0.065       09799.031   0.065       010200.94   0.065       0
#XS Ineff= 2 , 0
       0                               0
Bank Sta=9799.031,10200.94
Exp/Cntr=0.3,0.1

Type RM Length L Ch R = 1 ,5744.539,49.952500,49.952500,49.952500
XS GIS Cut Line= 6
1159823.41452932848362.5637099321159878.87182299848399.006712018
1159975.04276533848454.0704392781160011.32121072848478.392224672
1160108.50028955848524.973223902 1160172.6301155848560.456463223
#Sta/Elev= 30
9799.033 869.068 9821.42863.5784 9835.95857.45489863.239848.31299882.406837.0295
9886.186832.62049889.967 827.0889908.869824.85919935.333823.14729942.894821.2471
9946.675818.99929958.017809.58219973.139799.52939984.849793.90849992.746789.5087
9996.695788.0346   10001787.313610008.59 788.20410020.36791.410810027.64795.6374
10046.02805.233310053.11808.338510060.38810.561310096.77817.285210114.96822.3387
10129.57824.843710148.32830.666310167.06834.705410185.81 840.76710200.95841.4066
#Mann= 3 , 0 , 0
9799.033  0.0886       09799.033  0.0886       010200.95  0.0886       0
#XS Ineff= 2 , 0
       0                               0
Bank Sta=9799.033,10200.95
Exp/Cntr=0.3,0.1

Type RM Length L Ch R = 1 ,5694.587,49.952500,49.952500,49.952500
XS GIS Cut Line= 6
1159795.40574412848439.3674731861159894.95418807848492.722373243
1159939.11863694848506.5960339011160051.12704898848528.490074577
1160113.47685537848553.3534416741160167.49750371848581.729355803
#Sta/Elev= 30
9799.109846.8206 9821.84842.47089826.763841.11539833.139838.39369852.451826.8515
9867.298815.5712 9874.54810.60529878.161808.83949881.776808.27459889.024808.6902
9896.266808.22959903.508805.53829912.205801.46519924.579798.25149955.529  788.55
9968.932785.22619972.259785.07649985.564778.89869995.544 772.77610015.45774.6859
10025.39776.442810032.04778.2362 10052.4789.318210065.97799.063910072.75803.0682
10097.18812.315110122.01816.577110151.17824.707310186.45832.555310200.94833.1519
#Mann= 3 , 0 , 0
9799.109  0.0734       09799.109  0.0734       010200.94  0.0734       0
#XS Ineff= 2 , 0
       0                               0
Bank Sta=9799.109,10200.94
Exp/Cntr=0.3,0.1

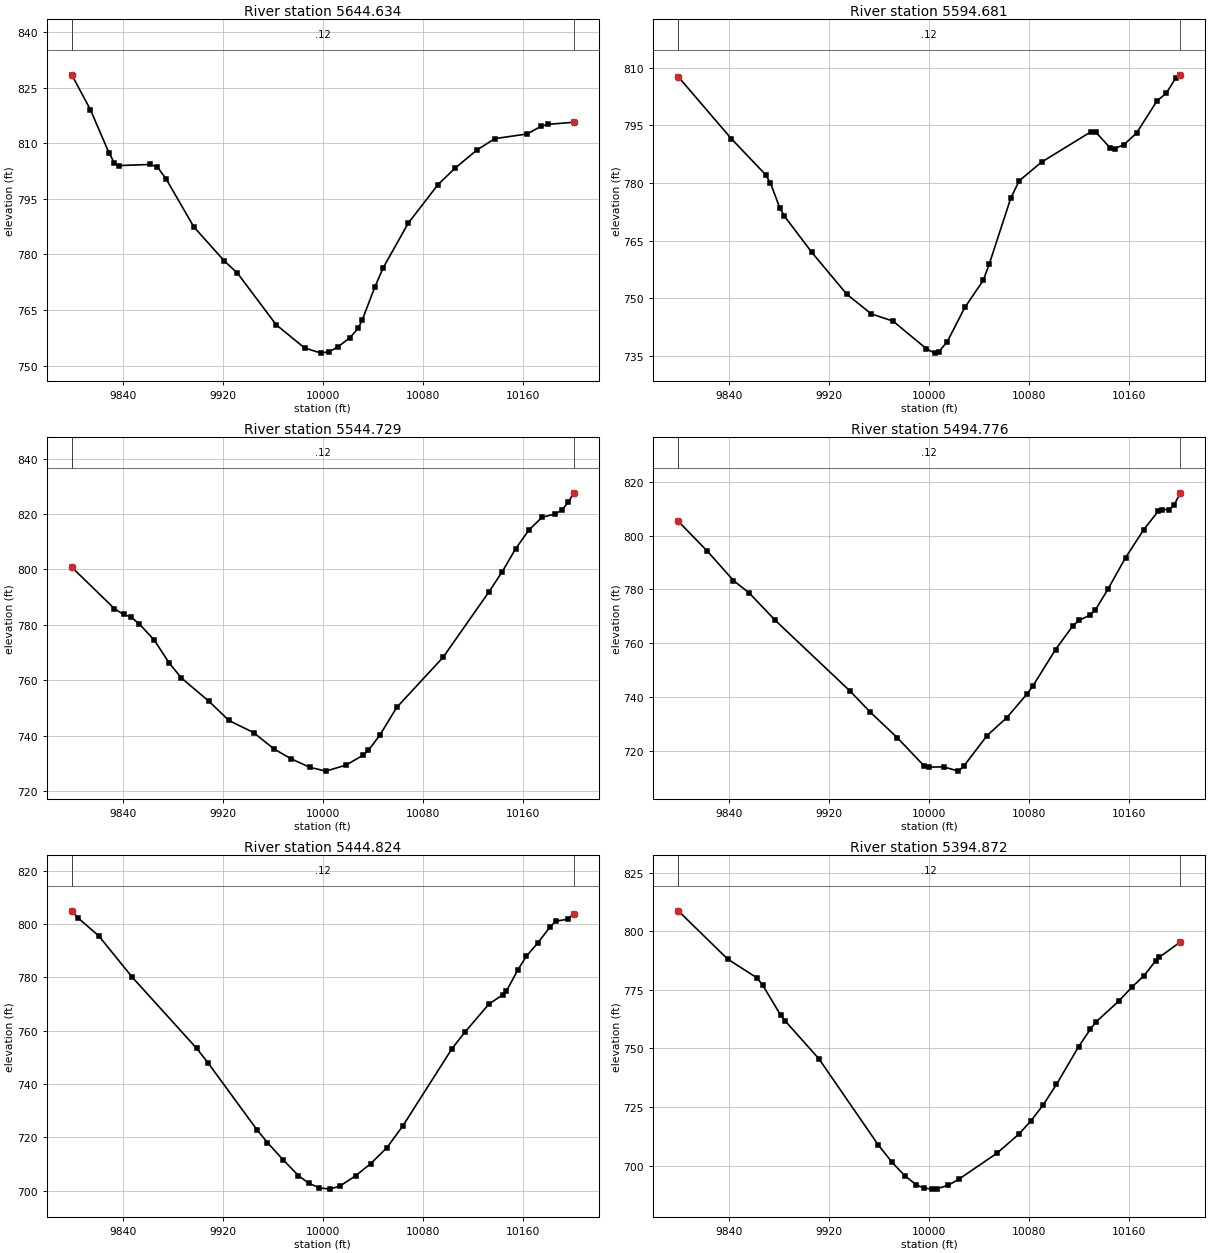
Type RM Length L Ch R = 1 ,5644.634,49.952600,49.952600,49.952600
XS GIS Cut Line= 6
1159789.03178354848490.6328280351159842.14341159848523.045471489
1159896.60621274848547.8412587831160051.74804937 848575.23123001
1160107.32660345848595.3039164931160163.18116587848623.819180246
#Sta/Elev= 30
9799.101828.52269814.028819.10219828.777807.51929833.245804.72479837.089804.0209
9861.322804.30299867.535803.69579874.865 800.2539896.805787.44429921.212778.2425
9931.712774.95469962.701761.01289985.389754.76499998.605753.3539 10005.2753.7685
 10011.8754.9502 10021.7757.5216 10028.3760.0436 10031.6762.318810041.56771.1136
10048.27776.353710068.38788.455510092.17798.856510105.97803.350710123.62808.2837
10137.74811.293810163.51812.543610174.56814.604710180.12815.136310200.93 815.721
#Mann= 3 , 0 , 0
9799.101    0.12       09799.101    0.12       010200.93    0.12       0
#XS Ineff= 2 , 0
       0                               0
Bank Sta=9799.101,10200.93
Exp/Cntr=0.3,0.1

Type RM Length L Ch R = 1 ,5594.681,49.952500,49.952500,49.952500
XS GIS Cut Line= 6
 1159792.3974534848525.7502341461159913.27402937848597.322628648
1159945.49715621848608.5521560731160040.59880003848628.757052792
1160090.38999391848650.2668470641160155.97311999848687.404428635
#Sta/Elev= 30
 9799.12 807.6729841.586 791.5529868.965782.19799872.876780.04729880.363773.5687
9884.077771.40139906.078 761.9459934.081751.0473 9953.68745.95459971.052744.0801
9997.744736.881910004.37735.757510007.69736.148210014.33738.692710028.51747.6805
10043.19754.685410048.08758.991810065.16776.031110072.02780.618210089.89785.4594
10129.41793.346310133.18793.279510144.49789.244710148.26788.9624 10155.8 789.999
10165.84792.996710182.19801.348810189.73803.418410197.27807.346910200.89808.1617
#Mann= 3 , 0 , 0
 9799.12    0.12       0 9799.12    0.12       010200.89    0.12       0
#XS Ineff= 2 , 0
       0                               0
Bank Sta=9799.12,10200.89
Exp/Cntr=0.3,0.1

Type RM Length L Ch R = 1 ,5544.729,49.952500,49.952500,49.952500
XS GIS Cut Line= 6
 1159793.3265762848538.3784928691159921.32114223848626.496009225
1159940.56647908848643.4672270961159964.69104129848671.267513335
1159989.59820583 848694.721753521160107.00932457 848787.67954137
#Sta/Elev= 30
9799.052800.83339833.206785.88329840.472783.78239846.258782.93449853.122780.3333
9865.071774.5557 9877.02766.28299886.758760.91119908.886752.46419924.818745.5502
9944.615741.17169960.898735.2982  9974.4731.7726  9989.6728.657210002.51727.2824
10018.53729.459610032.05732.962210036.55 734.81910045.57740.196910059.15750.2484
10096.19768.284510133.15792.031810143.72799.275810154.29807.430910164.86814.1783
10175.43818.8019   10186820.052310191.29821.417910196.58824.311310200.95 827.652
#Mann= 3 , 0 , 0
9799.052    0.12       09799.052    0.12       010200.95    0.12       0
#XS Ineff= 2 , 0
       0                               0
Bank Sta=9799.052,10200.95
Exp/Cntr=0.3,0.1

Type RM Length L Ch R = 1 ,5494.776,49.952500,49.952500,49.952500
XS GIS Cut Line= 6
1159763.96159382848542.8746452711159839.72411433848603.410539796
1159872.80181705848633.699638682 1159894.7320076848658.982563711
1159952.99764419848738.4961915931160044.55983776848827.703319017
#Sta/Elev= 30
9799.065805.31669822.267794.27099843.265783.31369855.863778.69119876.791 768.484
9936.545742.27739952.661734.46719974.362724.96479995.755714.5031 9999.66714.0127
10011.44714.099410023.34712.519710027.51714.2921 10046.3725.751110062.05732.3829
10078.34741.232910082.88744.114910101.07757.666710114.72 766.37610119.98768.5559
10128.36770.377510132.91772.363710143.09780.1408 10157.1791.793410171.67802.1946
10183.14808.985510186.24809.673510192.04809.676310195.96811.278710200.95815.8831
#Mann= 3 , 0 , 0
9799.065    0.12       09799.065    0.12       010200.95    0.12       0
#XS Ineff= 2 , 0
       0                               0
Bank Sta=9799.065,10200.95
Exp/Cntr=0.3,0.1

Type RM Length L Ch R = 1 ,5444.824,49.952500,49.952500,49.952500
XS GIS Cut Line= 6
1159736.58894372848568.4501950181159781.46159709848609.469900183
 1159818.3157271848646.8870287391159927.68557844848782.455075587
 1159962.8057854848820.2761808741160007.91523425 848863.93624945
#Sta/Elev= 30
9799.031805.0128 9803.86802.4207 9820.67795.5944 9847.34780.15919898.925753.4713
9908.135747.95559947.328722.84429955.712718.04389968.105711.64719980.497705.6656
9988.759702.8319 9997.02701.089610005.48 700.593 10013.8701.754810026.28705.6278
10038.28710.1151 10051.4716.198510064.22724.413110103.44753.315810113.69759.4444
10132.98770.024710144.03773.517710146.95774.878110156.08782.8267 10162.9787.9416
10172.33793.083710181.77798.875510186.49801.134310195.92801.835610200.97803.9208
#Mann= 3 , 0 , 0
9799.031    0.12       09799.031    0.12       010200.97    0.12       0
#XS Ineff= 2 , 0
       0                               0
Bank Sta=9799.031,10200.97
Exp/Cntr=0.3,0.1

Type RM Length L Ch R = 1 ,5394.872,49.952500,49.952500,49.952500
XS GIS Cut Line= 6
 1159695.5811806848592.1425343691159768.21565619848667.155528209
1159830.25690742848739.8269237041159831.49255057848741.399560348
1159903.99564985848825.5096841741159966.47555393848888.782792236
#Sta/Elev= 30
9799.032808.70159838.495788.16969862.077780.08089866.793776.88149880.943764.2616
9884.759761.65199911.677745.55299959.129708.8373 9970.29701.35479980.395695.6722
9989.326691.91829995.554690.4402 10002.2689.958210006.54690.1893 10015.2691.6092
10023.86 694.25310054.18705.277610071.51713.3206 10081.1718.893910091.15  725.85
10101.83734.624910119.61750.796610128.83758.088310133.45761.280410151.89 770.277
10162.67 776.39410172.01781.057710181.35787.467910184.16788.913910200.97795.3762
#Mann= 3 , 0 , 0
9799.032    0.12       09799.032    0.12       010200.97    0.12       0
#XS Ineff= 2 , 0
       0                               0
Bank Sta=9799.032,10200.97
Exp/Cntr=0.3,0.1

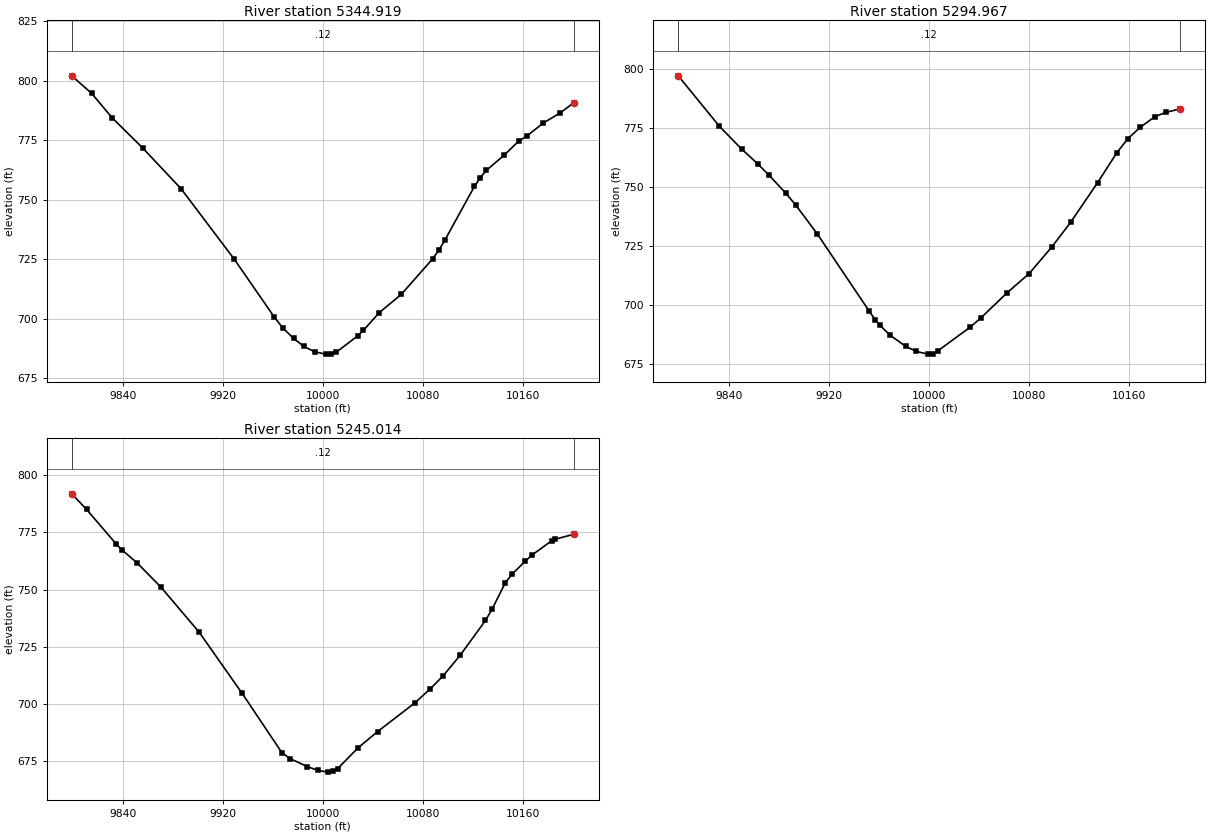
Type RM Length L Ch R = 1 ,5344.919,49.952500,49.952500,49.952500
XS GIS Cut Line= 6
1159664.89885586848625.5753608871159724.17805481 848689.74486176
  1159797.739666848777.6487257691159854.14473594848843.706425303
1159890.66799158 848882.155425021159934.22936181848923.540266958
#Sta/Elev= 30
9799.017802.11049815.013794.69079831.505784.3769 9855.68771.84879886.473754.6841
9929.261724.93569961.258700.63749967.769696.2709 9976.59691.73599984.885688.3743
9993.442686.135810002.16685.1457 10006.3 685.14710010.62685.890910027.87692.8081
10032.47695.114510045.13702.556810062.79710.237810088.04725.253310092.82728.7905
10097.57732.918910121.39 755.63210126.15759.362510130.91762.366410144.99768.6736
10156.97774.725310163.09776.735710176.67782.305410190.24786.603110200.98790.8302
#Mann= 3 , 0 , 0
9799.017    0.12       09799.017    0.12       010200.98    0.12       0
#XS Ineff= 2 , 0
       0                               0
Bank Sta=9799.017,10200.98
Exp/Cntr=0.3,0.1

Type RM Length L Ch R = 1 ,5294.967,49.952600,49.952600,49.952600
XS GIS Cut Line= 6
1159627.29967552848652.3479877621159685.67087336 848716.52335845
1159747.71821647 848795.334888541159807.96297309848867.296651686
1159850.64642548848910.7539998921159895.64304429848950.573808278
#Sta/Elev= 30
9799.035797.24399831.947775.88819849.686766.27119862.991759.78919871.861755.0555
9885.166747.49419893.147742.44619910.256730.32169952.012697.45419956.792693.8417
9960.363691.61249968.714687.30319981.241682.5653 9989.75680.4423    9999679.3158
10002.87679.510710007.13680.808910032.69690.719210041.21694.611110062.51705.4184
10079.95713.444910097.91724.620310113.26 735.239 10134.7 751.95210150.08 764.601
10158.98770.632410168.88775.423210180.75780.003310189.51781.762710200.95783.2655
#Mann= 3 , 0 , 0
9799.035    0.12       09799.035    0.12       010200.95    0.12       0
#XS Ineff= 2 , 0
       0                               0
Bank Sta=9799.035,10200.95
Exp/Cntr=0.3,0.1

Type RM Length L Ch R = 1 ,5245.014,49.952500,49.952500,49.952500
XS GIS Cut Line= 6
1159586.87884157848680.4518202961159659.19117565848758.922328154
1159736.66589544848861.722576762  1159757.107779 848886.03750901
1159793.43825941848920.8683782171159859.61063021848973.193142042
#Sta/Elev= 30
9799.033791.91139810.855 785.0879834.817 769.7869839.228767.34649851.548761.5516
9870.484750.99089901.116731.22349935.488 704.4549967.175678.57889973.598 675.971
9987.731 672.4099995.953670.783410004.16670.004910008.26670.461610011.77671.4771
10028.17680.6282 10043.9687.782510073.59700.291410086.13706.544310096.32712.2069
10109.84721.097910130.21736.4287 10135.5741.380510146.08752.934410151.37  756.62
10161.95762.381510167.24764.992710183.11771.312210185.77772.004110200.95774.1993
#Mann= 3 , 0 , 0
9799.033    0.12       09799.033    0.12       010200.95    0.12       0
#XS Ineff= 2 , 0
       0                               0
Bank Sta=9799.033,10200.95
Exp/Cntr=0.3,0.1