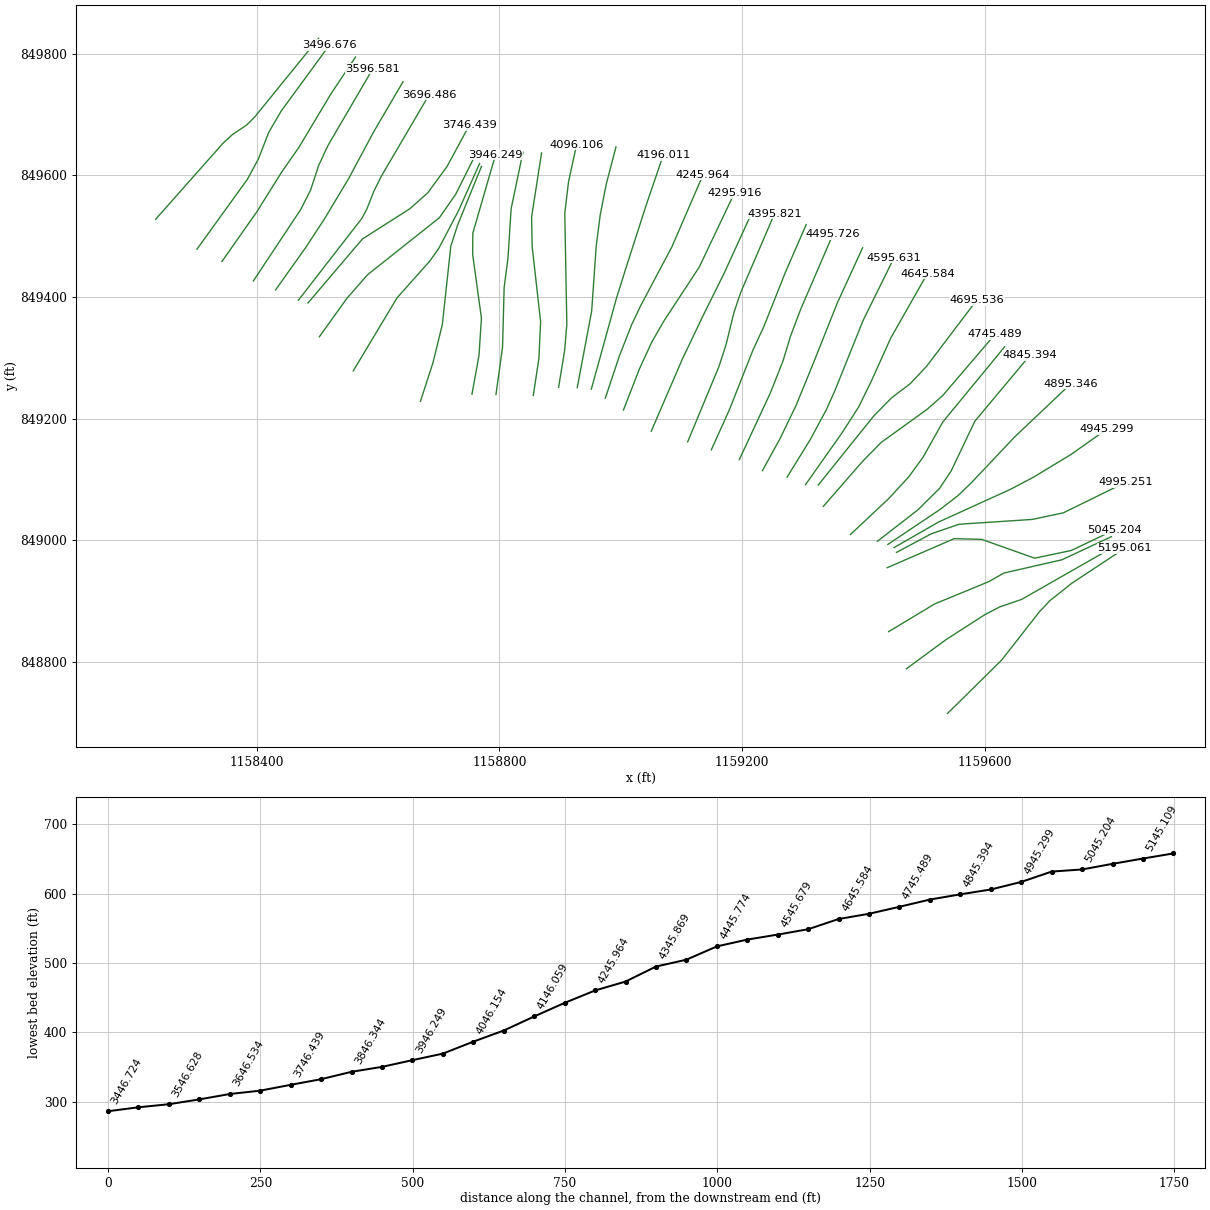
HEC-RAS study 177_ras.prj: 177

--- 177_ras.g01 (geometry) --- (continued)

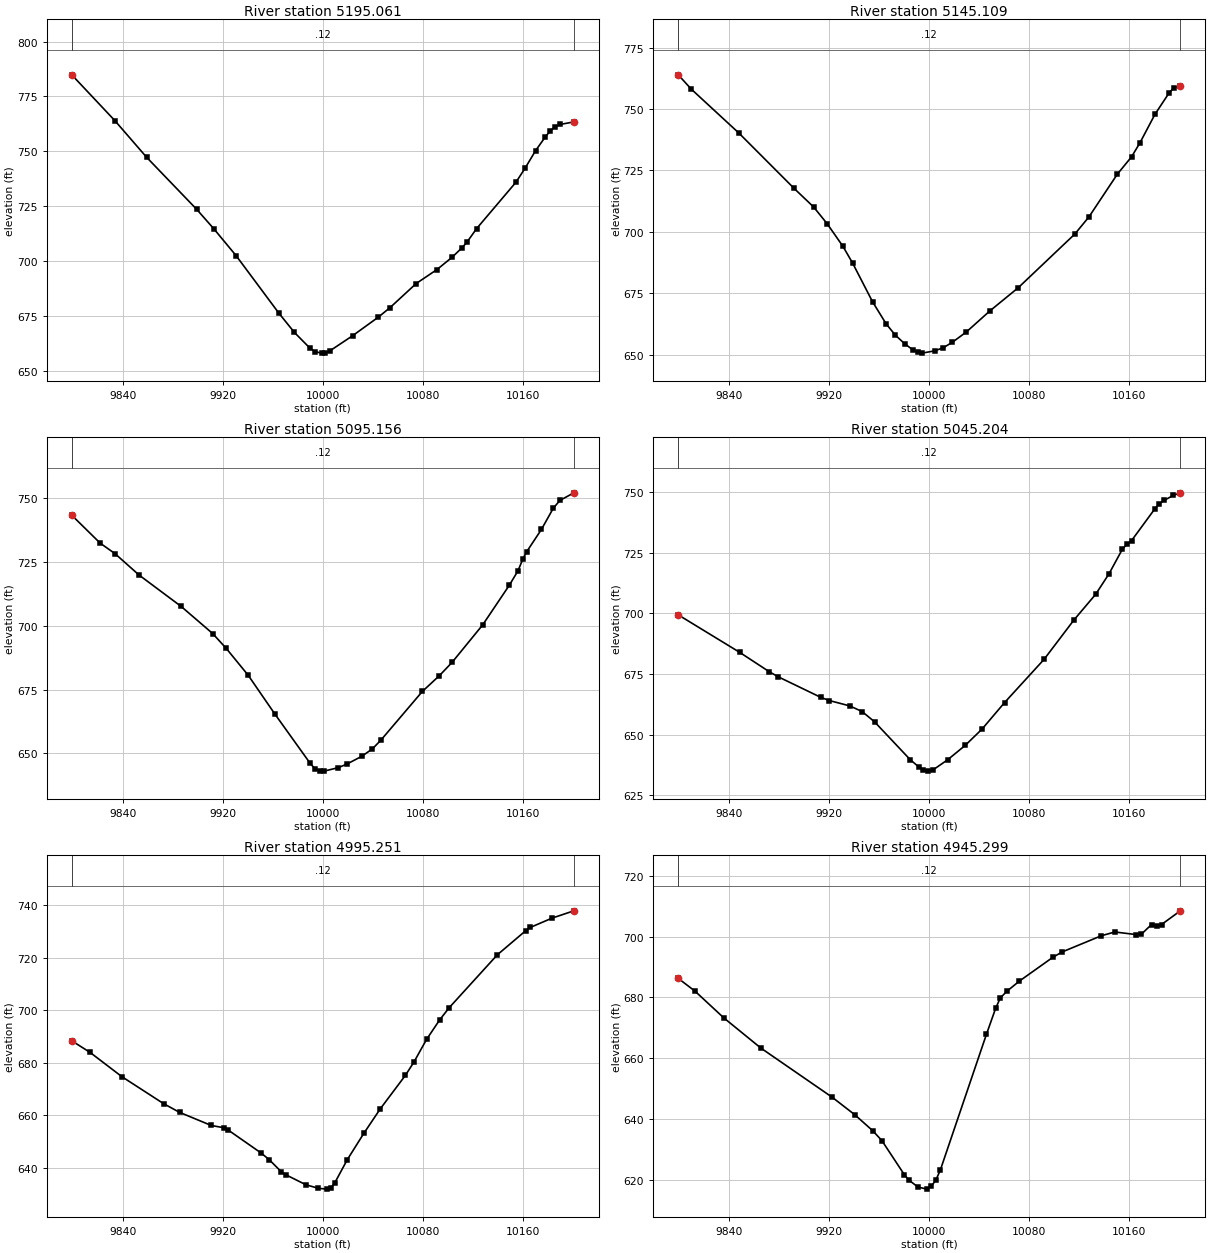
Type RM Length L Ch R = 1 ,5195.061,49.952500,49.952500,49.952500
XS GIS Cut Line= 6
1159538.47204105848715.3102832991159627.36084737848802.721687004
1159689.12584473848881.4921729021159707.01148034848900.557345403
1159743.42662374848929.4482725641159830.64443739848986.894723099
#Sta/Elev= 30
9799.023784.86629833.451764.03869859.021747.24889898.907723.65749912.655714.7844
9930.552702.4974    9965 676.1439977.263667.49289989.447660.49459993.508 658.781
    9999658.084510001.63658.123710005.73659.153410023.87666.025410044.47674.5021
10053.71678.770110074.65689.756610091.41696.176710103.51701.775910111.36706.0586
10115.29708.573610123.15714.852810154.58735.936110161.87742.303310170.29750.3102
10178.15756.635510182.08759.307210185.73 761.20910189.93762.261710200.93763.4153
#Mann= 3 , 0 , 0
9799.023    0.12       09799.023    0.12       010200.93    0.12       0
#XS Ineff= 2 , 0
       0                               0
Bank Sta=9799.023,10200.93
Exp/Cntr=0.3,0.1

Type RM Length L Ch R = 1 ,5145.109,49.952500,49.952500,49.952500
XS GIS Cut Line= 6
1159470.63551698848788.601118952  1159535.789009848836.460438066
1159600.19978888848877.7793163061159624.26809888848890.260203745
1159660.34043926848902.644809642  1159816.078458848991.235683999
#Sta/Elev= 30
 9799.07763.8911 9809.55758.05289847.639 740.1889891.887717.65729907.479 710.114
9918.214 703.3669930.866 694.1559938.662687.29669954.671671.51969965.454662.6278
9972.845658.00019980.236654.55539987.345651.83759990.785650.95749994.225650.6909
10004.45651.624210011.38652.926510018.57655.132210029.74659.317410048.61667.9013
10071.26677.309910116.55699.144510127.88706.147210150.52723.466310161.99730.5929
10168.62736.214110180.72747.885810192.04756.581310195.82758.675910200.95759.4016
#Mann= 3 , 0 , 0
 9799.07    0.12       0 9799.07    0.12       010200.95    0.12       0
#XS Ineff= 2 , 0
       0                               0
Bank Sta=9799.07,10200.95
Exp/Cntr=0.3,0.1

Type RM Length L Ch R = 1 ,5095.156,49.952500,49.952500,49.952500
XS GIS Cut Line= 6
1159441.40955412848849.6787394491159516.95747194848895.126492208
1159606.13712798848931.7780807171159631.32220626848946.037763339
1159726.99793629848967.8548571111159808.36081807849005.822816705
#Sta/Elev= 30
9799.066743.32449821.862732.36359833.575 728.3139852.975719.87399886.588707.6042
9911.847696.96349922.662 691.1689940.246680.63269961.346665.61059989.868646.1066
9993.624644.0466 9997.38643.1255   10001643.062410012.53644.445110019.39645.8634
10031.39648.932510039.68651.802610046.33655.131210079.62674.275910093.25680.4611
10103.47685.700810127.95700.3861 10149.2715.870110156.15721.536810160.12726.2085
10163.23729.098210174.93737.758210184.47746.115110189.74749.134710200.88752.1076
#Mann= 3 , 0 , 0
9799.066    0.12       09799.066    0.12       010200.88    0.12       0
#XS Ineff= 2 , 0
       0                               0
Bank Sta=9799.066,10200.88
Exp/Cntr=0.3,0.1

Type RM Length L Ch R = 1 ,5045.204,49.952500,49.952500,49.952500
XS GIS Cut Line= 6
1159438.96277252848954.7636982471159549.30991064849002.548048363
1159594.47762128849001.3958686891159681.94602044848970.440598705
1159742.21799119848983.0992075721159813.36183107849016.892613944
#Sta/Elev= 30
9799.184699.40959848.206683.98979872.003675.96059879.002673.90819913.248  665.38
 9920.16664.05649936.438 661.8559946.309659.52949956.244655.28689984.814639.6611
9991.427636.78529995.338635.46749999.262634.961410003.31635.572110014.82639.6831
10028.84 645.61710042.24652.306110060.23663.228110091.86681.065910115.71697.2783
 10133.2707.933810143.85716.3877 10154.5726.494210158.14728.554510161.84730.0367
10180.35 743.05310184.06745.223610187.76746.597210195.17748.652610200.84749.7361
#Mann= 3 , 0 , 0
9799.184    0.12       09799.184    0.12       010200.84    0.12       0
#XS Ineff= 2 , 0
       0                               0
Bank Sta=9799.184,10200.84
Exp/Cntr=0.3,0.1

Type RM Length L Ch R = 1 ,4995.251,49.952500,49.952500,49.952500
XS GIS Cut Line= 6
1159454.33270025848979.9543543781159511.48334383849010.467928671
1159557.24477922849026.2018299281159678.16592179849034.172161877
1159729.25379467849045.0228099691159832.14665665849095.387733379
#Sta/Elev= 30
9799.094688.36879813.808683.91969839.265674.68199872.689664.40159885.345661.1226
9910.757656.1197 9920.75655.26739924.064654.45219950.521645.67269957.083643.1112
9966.927638.42579970.208637.40159986.614633.51739996.475632.205710003.09 631.886
10006.38632.254410009.68634.370810019.56643.081610032.75653.070710046.03662.4846
 10066.1675.208510072.89680.247810083.07688.918710093.56696.356910101.24701.0215
10139.68721.111310162.27730.240510166.04731.5269 10183.4735.0624 10200.9737.8518
#Mann= 3 , 0 , 0
9799.094    0.12       09799.094    0.12       0 10200.9    0.12       0
#XS Ineff= 2 , 0
       0                               0
Bank Sta=9799.094,10200.9
Exp/Cntr=0.3,0.1

Type RM Length L Ch R = 1 ,4945.299,49.952500,49.952500,49.952500
XS GIS Cut Line= 6
1159450.37600294848987.9120793341159523.80723546 849029.96810447
1159642.32372088849083.7641352681159680.00176341849103.591995964
1159741.48097562849140.7251863581159800.94681823849182.567782563
#Sta/Elev= 30
9799.033686.28419812.418 682.0959835.747673.20829865.208663.35679922.391647.1539
9940.436  641.419954.872636.12659962.089632.90699980.134621.65989983.743619.9211
9990.961617.65019998.179 616.96910001.72617.984710005.29619.962410008.86623.2596
10045.74667.864610053.15676.465310056.87  679.8510062.02682.0118 10072.2685.4116
10099.03693.243410106.44694.990410137.79700.309510148.57 701.54210165.87700.6749
10169.88700.8401 10177.9703.991110181.91703.392110185.93703.995410200.96708.5006
#Mann= 3 , 0 , 0
9799.033    0.12       09799.033    0.12       010200.96    0.12       0
#XS Ineff= 2 , 0
       0                               0
Bank Sta=9799.033,10200.96
Exp/Cntr=0.3,0.1

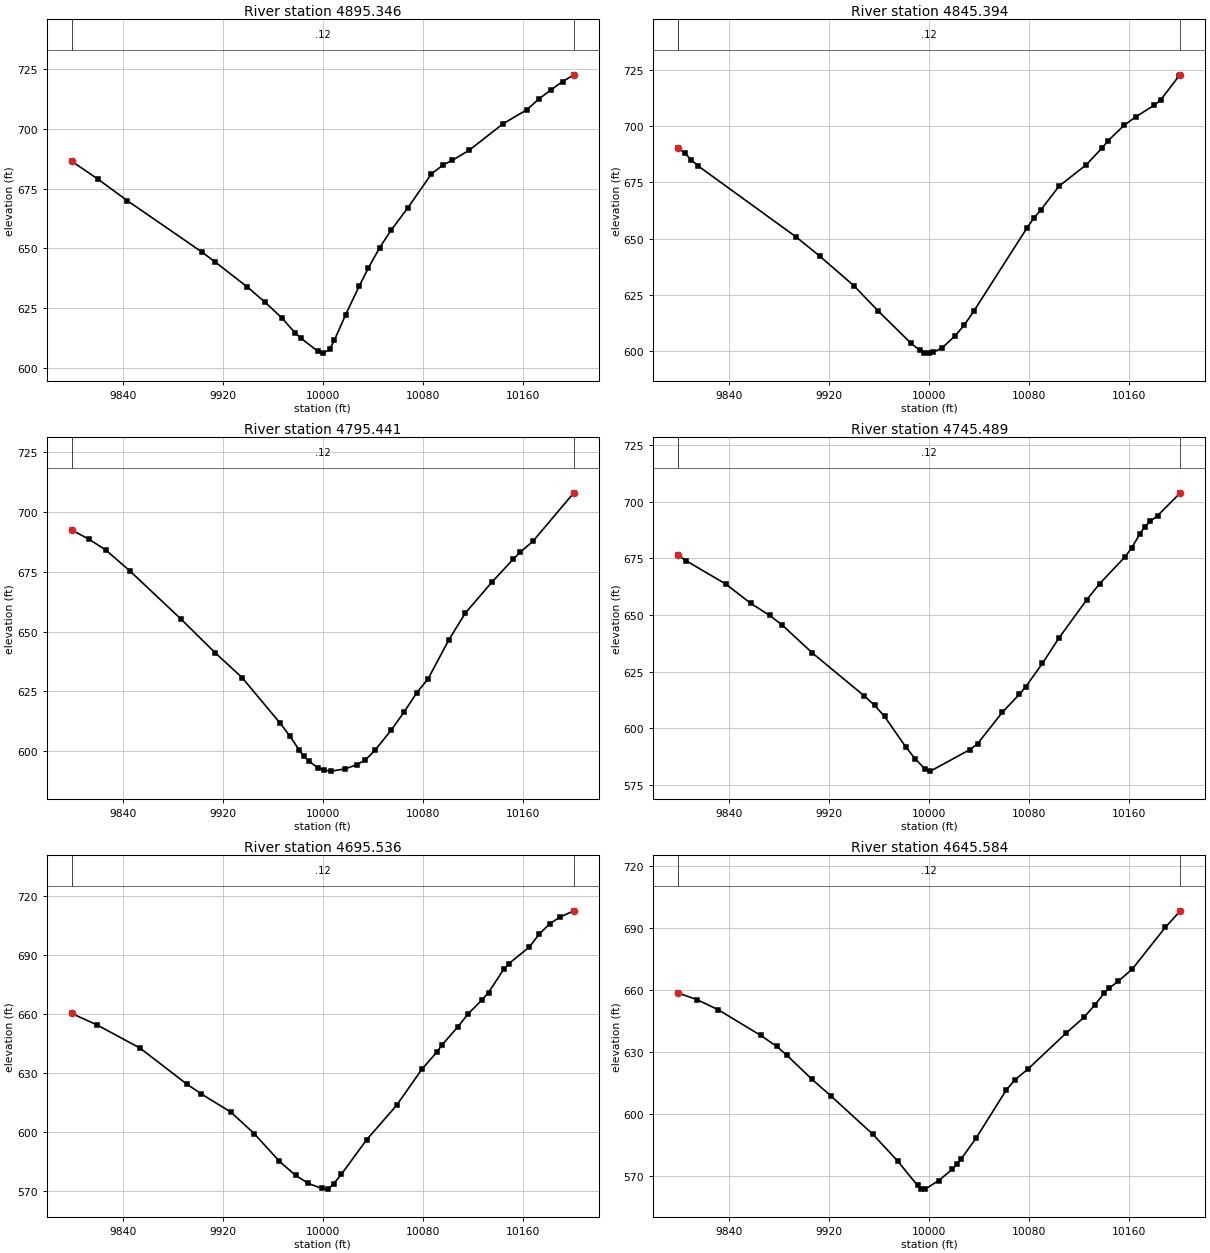
Type RM Length L Ch R = 1 ,4895.346,49.952600,49.952600,49.952600
XS GIS Cut Line= 6
1159440.06247033848993.045074249 1159526.8832569849051.087114541
1159555.51554333849073.252934366 1159576.4258863849093.168981108
  1159648.686472 849169.483360341159741.18195652849257.001395531
#Sta/Elev= 30
 9799.03686.47189819.748679.05649843.426669.98919903.466648.33829913.569644.3786
9939.675633.76169953.537 627.5149967.129620.8888  9977.8614.55789982.292612.4327
 9995.86606.912210000.26606.081410005.43 607.62110009.31611.577110018.37 622.258
10029.22634.263110036.49641.792210045.55650.264610054.61657.4994 10068.2667.0506
10087.01681.192210096.55685.019710103.74686.863810117.29691.118210144.29702.1596
10163.38708.057110172.93712.547810182.48716.320410192.02719.855210200.99722.6777
#Mann= 3 , 0 , 0
 9799.03    0.12       0 9799.03    0.12       010200.99    0.12       0
#XS Ineff= 2 , 0
       0                               0
Bank Sta=9799.03,10200.99
Exp/Cntr=0.3,0.1

Type RM Length L Ch R = 1 ,4845.394,49.952500,49.952500,49.952500
XS GIS Cut Line= 6
1159422.70781229848998.1677898151159489.44665639849049.777601259
 1159525.2033569849085.1308160621159544.48951113849114.058149722
 1159583.3703753849195.6706418471159674.38051357849304.198695266
#Sta/Elev= 30
9799.119690.19469804.562687.9533 9809.65 684.9889815.288682.25089893.228650.8786
9912.231642.30529939.775629.0481 9959.25617.80199985.298603.55889992.419600.3416
 9995.98599.31099999.525599.106610003.03599.4542 10010.1 601.339 10020.7606.7981
10028.07611.621710035.68617.788310078.41654.957710083.79659.216810089.17662.7446
10104.01 673.42410125.54682.804410138.64690.5394   10143693.481810156.11700.5226
10165.28704.191410180.19   709.410185.16711.664710199.78 722.29810200.93722.8732
#Mann= 3 , 0 , 0
9799.119    0.12       09799.119    0.12       010200.93    0.12       0
#XS Ineff= 2 , 0
       0                               0
Bank Sta=9799.119,10200.93
Exp/Cntr=0.3,0.1

Type RM Length L Ch R = 1 ,4795.441,49.952500,49.952500,49.952500
XS GIS Cut Line= 6
1159378.33064771849009.2687565431159442.00821666849068.895091539
1159475.23682316849105.0278481151159498.18230666849136.666889268
1159530.61118489849194.3567080381159632.39855718849317.843854333
#Sta/Elev= 30
9799.069692.47539812.848688.65889826.332684.0982  9845.3675.50959886.305655.3009
9913.722641.15349935.394630.71639965.563611.81469973.668606.21879981.254 600.249
9985.018597.70089988.782595.77119995.985592.9819   10001591.9389 10006.6591.5571
10018.12592.4938   10027594.250610033.88596.109510041.83600.344510054.59608.6135
 10064.9616.191810075.22624.367410084.35630.271210101.01646.636310114.11657.7357
10135.37670.687310152.59680.366910157.75 683.13210168.06687.722210200.94708.0708
#Mann= 3 , 0 , 0
9799.069    0.12       09799.069    0.12       010200.94    0.12       0
#XS Ineff= 2 , 0
       0                               0
Bank Sta=9799.069,10200.94
Exp/Cntr=0.3,0.1

Type RM Length L Ch R = 1 ,4745.489,49.952500,49.952500,49.952500
XS GIS Cut Line= 6
1159333.75011282 849055.595594991159398.00137993849129.193423238
1159429.26432254849160.9168242741159504.77941774849215.192800528
1159530.58627958849237.947080603 1159616.5226047849338.325059655
#Sta/Elev= 30
 9799.04676.2888 9805.62673.79669837.222663.57269857.177 655.0569872.143649.8047
 9882.12645.61759906.311633.26079947.794614.36929956.252610.13339964.201605.2323
9981.005  591.919988.914586.41029996.822581.965710000.91581.135910032.49590.6194
10038.66593.2406 10058.5607.073410071.98614.927310077.32618.4284 10090.6628.6712
10103.88 639.90710125.97656.623510136.29663.724210156.92675.758910162.08679.6216
10168.35685.510710172.39688.859510176.86 691.24410182.71693.748410200.94703.8311
#Mann= 3 , 0 , 0
 9799.04    0.12       0 9799.04    0.12       010200.94    0.12       0
#XS Ineff= 2 , 0
       0                               0
Bank Sta=9799.04,10200.94
Exp/Cntr=0.3,0.1

Type RM Length L Ch R = 1 ,4695.536,49.952500,49.952500,49.952500
XS GIS Cut Line= 6
1159325.31448172849090.5671790821159416.99714611849204.434359029
1159446.49463385849234.3487789721159477.06103813849257.434504068
1159503.97569156849286.0117600221159586.25969318849394.343540395
#Sta/Elev= 30
 9799.05660.30089819.221654.51569853.662642.73069890.902624.52579902.871619.3735
9926.404610.17729945.271599.1422 9965.27 585.1569978.191578.03389988.459573.9151
    9999571.480410004.24571.045110008.84573.8893 10014.9578.634610035.05596.1403
10058.97613.566410079.44632.0874 10091.2640.644610095.24644.210310107.98653.4395
 10116.3660.128910127.46667.230810132.62670.964310144.86682.841610148.94685.6744
10165.26694.052610173.42700.825810181.58705.854310189.74709.293810200.92712.4795
#Mann= 3 , 0 , 0
 9799.05    0.12       0 9799.05    0.12       010200.92    0.12       0
#XS Ineff= 2 , 0
       0                               0
Bank Sta=9799.05,10200.92
Exp/Cntr=0.3,0.1

Type RM Length L Ch R = 1 ,4645.584,49.952500,49.952500,49.952500
XS GIS Cut Line= 6
1159304.35500929849091.3032605171159364.77220933 849176.78190085
1159392.24406022849219.561854078 1159412.7074112849261.254322692
 1159444.7257396849332.1502662051159505.14536365849438.307859509
#Sta/Elev= 30
 9799.04 658.4219813.894655.31439830.946650.39319865.051637.94839877.894632.6299
9885.929628.36129905.949616.76539921.546608.46699954.556590.23439974.769577.0713
9990.568565.31079993.032563.79789996.684563.519610007.57567.674310018.37573.1056
10021.97575.463210025.57578.182610037.57588.306110061.57611.465910068.77616.5886
10078.79621.538210109.81639.216810124.08646.837910132.46652.664110140.01658.4143
10143.78660.728710151.33664.178510162.66670.187410189.08690.357710200.94698.2549
#Mann= 3 , 0 , 0
 9799.04    0.12       0 9799.04    0.12       010200.94    0.12       0
#XS Ineff= 2 , 0
       0                               0
Bank Sta=9799.04,10200.94
Exp/Cntr=0.3,0.1

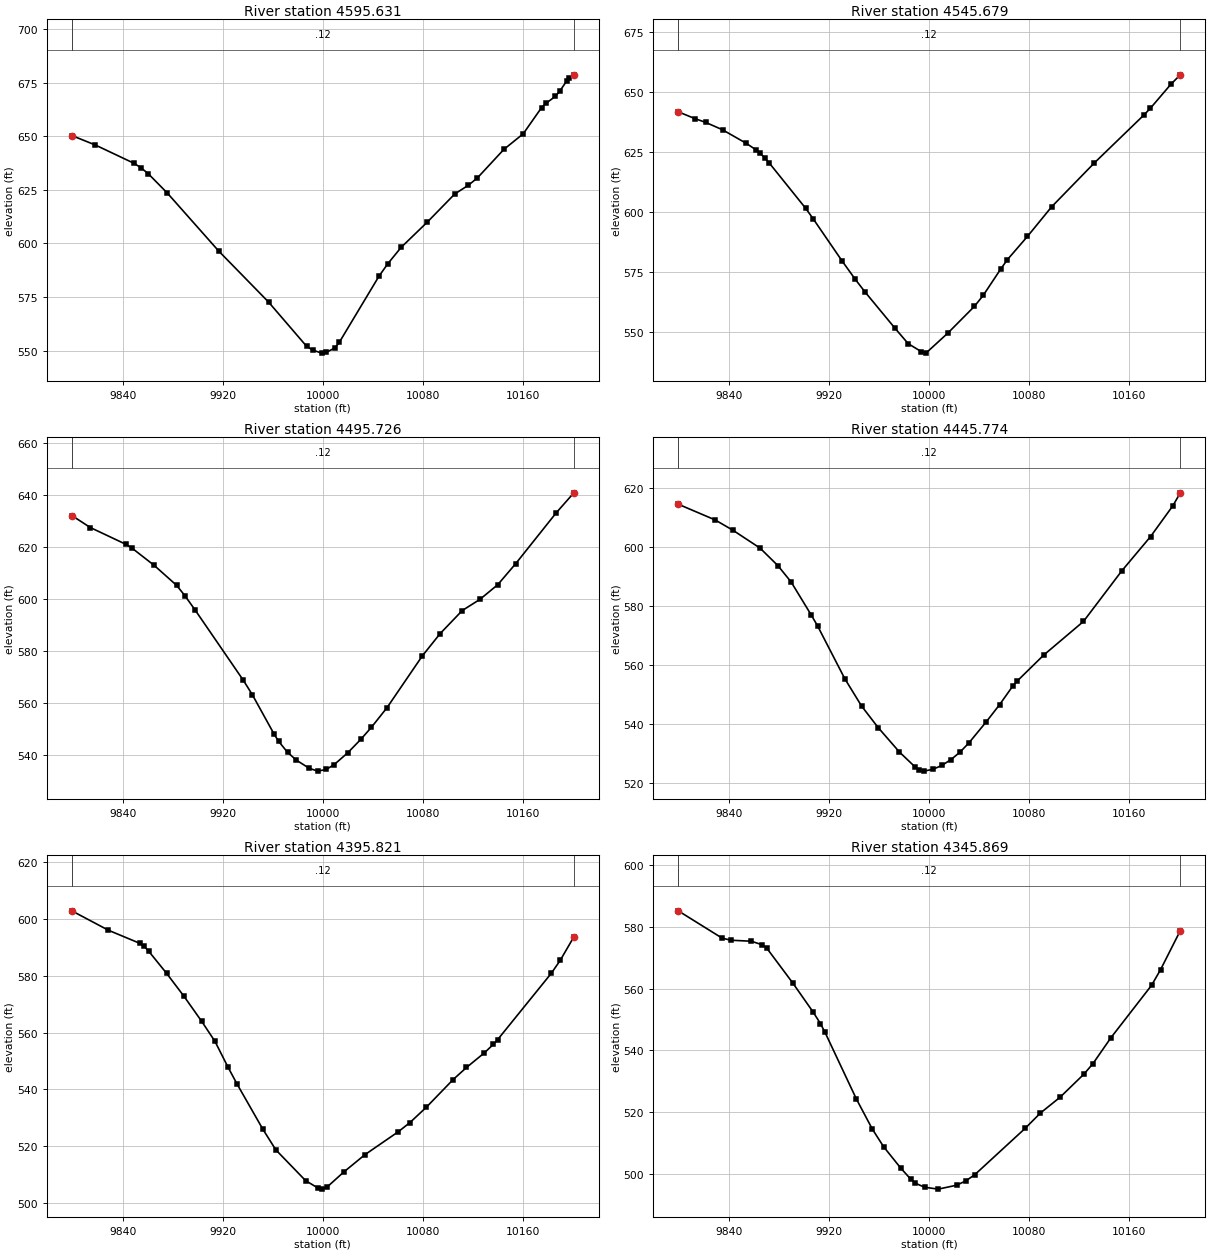
Type RM Length L Ch R = 1 ,4595.631,49.952500,49.952500,49.952500
XS GIS Cut Line= 6
 1159273.9626437849103.6050888991159312.28326313849165.507112849
1159338.56544442849214.2561016981159352.90955229849246.123827476
1159399.18823213849361.0799046041159450.12407805849464.049214345
#Sta/Elev= 30
9799.026650.26939817.847645.86479848.716637.35419854.357635.28259860.292632.4427
9875.593623.39689916.593596.44129956.539572.62139987.153551.87829991.949550.2193
 9999.01548.780910002.57549.080610009.64551.184910013.18553.794210045.03584.7108
10052.11590.534310062.72598.107810083.53609.817210105.64623.006910116.51627.0738
10123.75630.491510144.95643.798310160.44651.0735 10175.2663.341810178.89665.3941
10186.27668.575810189.96671.192710195.12675.589910197.34677.050610200.98678.5823
#Mann= 3 , 0 , 0
9799.026    0.12       09799.026    0.12       010200.98    0.12       0
#XS Ineff= 2 , 0
       0                               0
Bank Sta=9799.026,10200.98
Exp/Cntr=0.3,0.1

Type RM Length L Ch R = 1 ,4545.679,49.952600,49.952600,49.952600
XS GIS Cut Line= 6
1159233.47598009 849114.502604221159262.46759811849167.132239678
1159289.02880346849221.9627297131159318.92946541 849295.04468127
1159356.81845243849390.1048932921159398.42698066849480.649121241
#Sta/Elev= 30
9799.026641.68389812.346638.84569820.903637.28479834.502634.18119853.548628.5127
9860.988625.92469864.634624.35659868.279622.47399871.925620.31099901.089601.4058
 9907.13597.00469929.971579.65299940.605571.92769948.497566.59319972.508  551.45
9983.153544.98529993.777541.62919997.322541.049210014.97549.449410036.16560.5626
10043.23565.160110057.36576.2383 10062.6580.064910078.56589.687810097.99602.0814
10132.21620.389110171.93640.390310176.94643.109510193.59653.257210200.98657.0995
#Mann= 3 , 0 , 0
9799.026    0.12       09799.026    0.12       010200.98    0.12       0
#XS Ineff= 2 , 0
       0                               0
Bank Sta=9799.026,10200.98
Exp/Cntr=0.3,0.1

Type RM Length L Ch R = 1 ,4495.726,49.952500,49.952500,49.952500
XS GIS Cut Line= 6
1159195.33881021849132.5036292681159246.49857956849242.141322421
1159267.14419805849294.2987721571159279.93584405849336.144079727
1159296.36493781849379.4932114981159349.74728957849503.175742276
#Sta/Elev= 30
9799.026632.04349813.917627.41239842.294 620.9899846.851619.66319865.025 612.878
9882.948 605.2199889.485601.30539897.629595.84539936.455568.68679943.512563.2659
9961.155547.93959964.683545.2613 9971.74541.10479978.732538.10879989.055534.9596
9995.938533.852810002.77534.5033 10009.1536.3513 10019.9540.862410030.42 546.057
10038.93550.697210051.47558.2698 10079.7578.135110093.91586.663510111.67595.5487
10125.87 599.852 10140.1605.4885 10154.5613.5851 10186.9633.093510200.98640.7538
#Mann= 3 , 0 , 0
9799.026    0.12       09799.026    0.12       010200.98    0.12       0
#XS Ineff= 2 , 0
       0                               0
Bank Sta=9799.026,10200.98
Exp/Cntr=0.3,0.1

Type RM Length L Ch R = 1 ,4445.774,49.952500,49.952500,49.952500
XS GIS Cut Line= 6
1159149.14619206849148.4905032881159179.12395161849214.836989152
1159217.48096802849311.8345332981159235.87854201849351.552194453
1159271.14829867849440.2030409161159305.43340991849518.721012196
#Sta/Elev= 30
9799.019614.35619828.528609.04399842.928605.5134 9864.53599.49799878.788593.5765
9889.372 588.0519905.582576.8092 9910.54573.18769932.347555.31639945.821546.0302
9959.112538.7393 9976.13 530.478 9988.43525.52129992.038524.37319995.646524.0188
 10002.9524.627810010.14525.963210017.38527.9288 10024.5530.403710031.57533.4893
10045.69540.735510056.28546.500610066.88552.826210070.41554.511710091.59563.2834
10123.48574.692210154.13591.796310177.18 603.40710195.08 613.86410200.99618.2071
#Mann= 3 , 0 , 0
9799.019    0.12       09799.019    0.12       010200.99    0.12       0
#XS Ineff= 2 , 0
       0                               0
Bank Sta=9799.019,10200.99
Exp/Cntr=0.3,0.1

Type RM Length L Ch R = 1 ,4395.821,49.952500,49.952500,49.952500
XS GIS Cut Line= 6
1159110.19334219849161.5735251411159161.91651013849285.947375381
1159173.50114174849321.6974406641159186.63558479849374.931473583
1159197.63372514849407.2744133021159253.20480593849536.479723171
#Sta/Elev= 30
 9799.02602.88959828.399596.04259853.452591.44999857.031590.3925 9860.61588.6625
9874.878580.90229888.977572.71289903.076563.9257 9913.65556.91449924.225547.7077
9931.274541.9275 9952.02525.93299962.366518.69749986.203507.85169996.342505.1806
9999.711504.851210003.07505.446510016.61 510.816 10033.7 516.98110060.32525.0304
 10069.8528.314510082.89533.700210104.32543.446510115.03547.699210129.32552.8547
10136.46555.823510140.03557.554510182.89580.864710190.03585.417410200.97593.7011
#Mann= 3 , 0 , 0
 9799.02    0.12       0 9799.02    0.12       010200.97    0.12       0
#XS Ineff= 2 , 0
       0                               0
Bank Sta=9799.02,10200.97
Exp/Cntr=0.3,0.1

Type RM Length L Ch R = 1 ,4345.869,49.952500,49.952500,49.952500
XS GIS Cut Line= 6
1159050.20639534849179.1618204421159101.08171835849296.907898151
1159132.01899226849361.6101286941159132.80009201849363.451292235
1159170.25437445849438.7741499311159218.53013365849544.101001545
#Sta/Elev= 30
9799.015585.23579834.211576.36519841.359575.69399857.561575.37779866.377574.1936
9869.951573.10619890.648561.86729907.191552.29899912.838548.67199916.412545.9193
9941.678 524.1739954.442  514.429963.498508.69339977.259501.74819985.317498.1285
9988.954496.87929996.227495.588710007.14494.9747 10021.8496.235410029.13497.6157
10036.45 499.66210076.76514.684310088.96 519.64810104.71524.7746 10123.8532.2666
10131.02535.668810145.46544.098210177.94561.063510185.16566.148510200.98578.8204
#Mann= 3 , 0 , 0
9799.015    0.12       09799.015    0.12       010200.98    0.12       0
#XS Ineff= 2 , 0
       0                               0
Bank Sta=9799.015,10200.98
Exp/Cntr=0.3,0.1

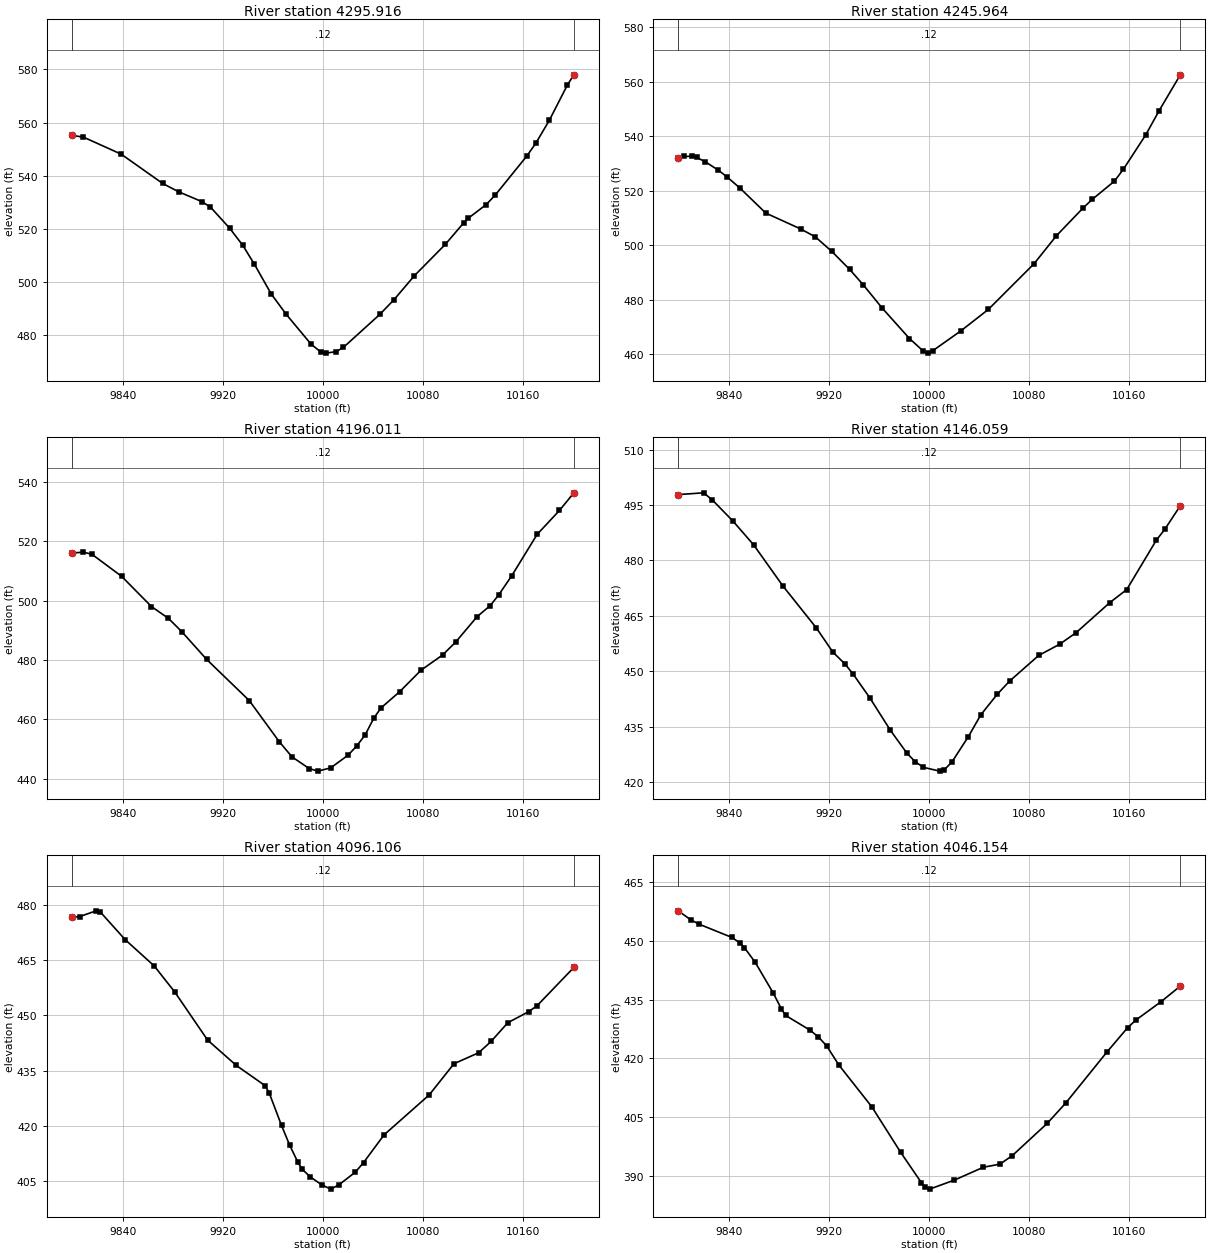
Type RM Length L Ch R = 1 ,4295.916,49.952500,49.952500,49.952500
XS GIS Cut Line= 6
1159004.40742299849213.9717612971159030.81229667849281.819948987
1159051.04116875849325.5731773791159070.14543049849358.923653586
1159129.30231007849448.9698896871159187.17224895849570.593900283
#Sta/Elev= 30
9799.034555.2249 9808.42554.52269838.597548.12949871.839537.10149884.698533.9628
9903.027530.3221    9910528.25979925.478 520.2679936.004513.8129 9945.28506.7033
9958.701495.5805 9970.64487.94939990.539476.72169998.498473.698810002.48473.3199
10010.68473.8721 10016.5475.468710045.63487.869610057.11493.461710073.25502.3906
10097.99514.166510112.73522.263310116.56524.078510130.82529.181310138.03532.7418
10163.27547.394110170.48 552.20210181.29560.801510195.71574.048510200.98 577.959
#Mann= 3 , 0 , 0
9799.034    0.12       09799.034    0.12       010200.98    0.12       0
#XS Ineff= 2 , 0
       0                               0
Bank Sta=9799.034,10200.98
Exp/Cntr=0.3,0.1

Type RM Length L Ch R = 1 ,4245.964,49.952500,49.952500,49.952500
XS GIS Cut Line= 6
1158974.53273889849233.5759467851158997.62495109849302.625149169
1159017.85095594849354.1820305171159032.91118837849385.717770027
1159084.24651952849482.2653910211159135.71759975849601.055990801
#Sta/Elev= 30
9799.021532.09959803.388532.66429810.307532.69769813.767532.27849820.686530.6896
9831.064527.62179837.983525.17369848.361521.07659869.118511.86889897.261505.9946
9908.705503.17499921.931497.82069936.307491.17669947.214485.50719962.159477.0989
9984.139465.85479995.335461.18379999.068460.4969 10002.8461.377810025.03468.5701
10047.27476.520510083.89493.292310101.76503.541910123.22513.784710130.37516.8527
10148.25523.5904 10155.4527.951510173.28540.5434   10184549.435510200.97562.5847
#Mann= 3 , 0 , 0
9799.021    0.12       09799.021    0.12       010200.97    0.12       0
#XS Ineff= 2 , 0
       0                               0
Bank Sta=9799.021,10200.97
Exp/Cntr=0.3,0.1

Type RM Length L Ch R = 1 ,4196.011,49.952600,49.952600,49.952600
XS GIS Cut Line= 6
1158951.48472449849248.4182158121158993.00608054849398.181938665
1159006.43044989849440.6868400831159006.94870708849442.618525743
1159042.12316181849551.6162948361159069.81573556849632.463409628
#Sta/Elev= 30
9799.013516.04049808.336516.32549815.145515.62849838.977508.17159862.809498.0191
9876.428494.02649887.041489.58259907.069480.18599941.115466.35789965.058452.5463
 9975.38447.37359989.142443.45599996.023442.592410006.33443.692610020.12447.9339
10027.01450.987910033.91454.8024 10040.8460.402510046.54463.860610061.49469.3267
10078.73476.611510095.96481.721810106.31486.020610123.59494.639110133.99498.3036
10140.93501.995910151.39 508.46910171.64522.343610189.48530.381410200.99536.3152
#Mann= 3 , 0 , 0
9799.013    0.12       09799.013    0.12       010200.99    0.12       0
#XS Ineff= 2 , 0
       0                               0
Bank Sta=9799.013,10200.99
Exp/Cntr=0.3,0.1

Type RM Length L Ch R = 1 ,4146.059,49.952500,49.952500,49.952500
XS GIS Cut Line= 6
1158928.26729304849250.7374549931158952.04603391849376.656883388
1158959.52036987849483.4970443241158966.13170078849534.729516016
1158976.09641991849585.5570718561158992.13059493849646.643088073
#Sta/Elev= 30
9799.025497.81529819.278498.29239825.993496.47779842.782490.66839859.378484.2308
9882.839473.09449909.434461.83359922.731455.2641 9932.66451.95369939.256449.1774
9952.447442.82639968.937434.04769982.081427.90419988.648425.61249995.215424.0749
10008.35423.042810011.64423.267810018.21425.553610031.35432.403310041.26438.2681
10054.49443.860610064.41 447.42810087.59454.3197 10104.3457.341610117.68460.5182
10144.52 468.60810158.09472.144710181.83485.519110188.61488.452510200.96494.8084
#Mann= 3 , 0 , 0
9799.025    0.12       09799.025    0.12       010200.96    0.12       0
#XS Ineff= 2 , 0
       0                               0
Bank Sta=9799.025,10200.96
Exp/Cntr=0.3,0.1

Type RM Length L Ch R = 1 ,4096.106,49.952500,49.952500,49.952500
XS GIS Cut Line= 6
 1158897.5713396 849251.279165651158907.53020161849311.992807245
1158911.12337199849354.8606990841158907.73464104849537.591503507
1158913.94822163 849589.382143161158927.26173902849650.267642751
#Sta/Elev= 30
9799.044 476.6859805.249476.87969818.548478.46449821.872478.1574 9841.82470.6119
9865.049463.46379881.511456.36869907.835443.27389930.801436.38479953.792430.9006
9957.079428.91939966.939420.07539973.513  414.679980.086 410.0219983.373 408.196
9989.947406.0765    9999403.937810006.37402.743410012.94403.931510026.06407.3699
10032.63409.979410049.04417.512110085.14428.369310104.96436.850910124.78 439.858
10134.69442.928710148.06448.017510164.86  451.0410171.57452.666710200.94463.0591
#Mann= 3 , 0 , 0
9799.044    0.12       09799.044    0.12       010200.94    0.12       0
#XS Ineff= 2 , 0
       0                               0
Bank Sta=9799.044,10200.94
Exp/Cntr=0.3,0.1

Type RM Length L Ch R = 1 ,4046.154,49.952500,49.952500,49.952500
XS GIS Cut Line= 6
1158855.90401498849237.8403078471158865.08561426 849298.80699495
1158867.94813537849358.9521589481158853.99233812849482.517286124
1158853.08452664849531.4262682791158869.47230708849636.597237536
#Sta/Elev= 30
9799.076457.60629808.905455.36269815.541454.23419842.084450.81919848.719449.3682
9852.037448.2276 9860.73444.46679875.116436.65679881.685432.5927 9884.97 430.972
9904.677 427.1879911.246425.46899917.815423.22859927.673418.31139953.964407.7082
9977.078396.10039993.635388.39889996.946387.158310000.25386.724110020.14389.0349
10043.35392.3079 10056.5393.078410066.34395.235810094.31403.454310109.08408.6094
10142.07421.604610158.71427.837710165.42429.808110185.54434.477510200.89438.4401
#Mann= 3 , 0 , 0
9799.076    0.12       09799.076    0.12       010200.89    0.12       0
#XS Ineff= 2 , 0
       0                               0
Bank Sta=9799.076,10200.89
Exp/Cntr=0.3,0.1

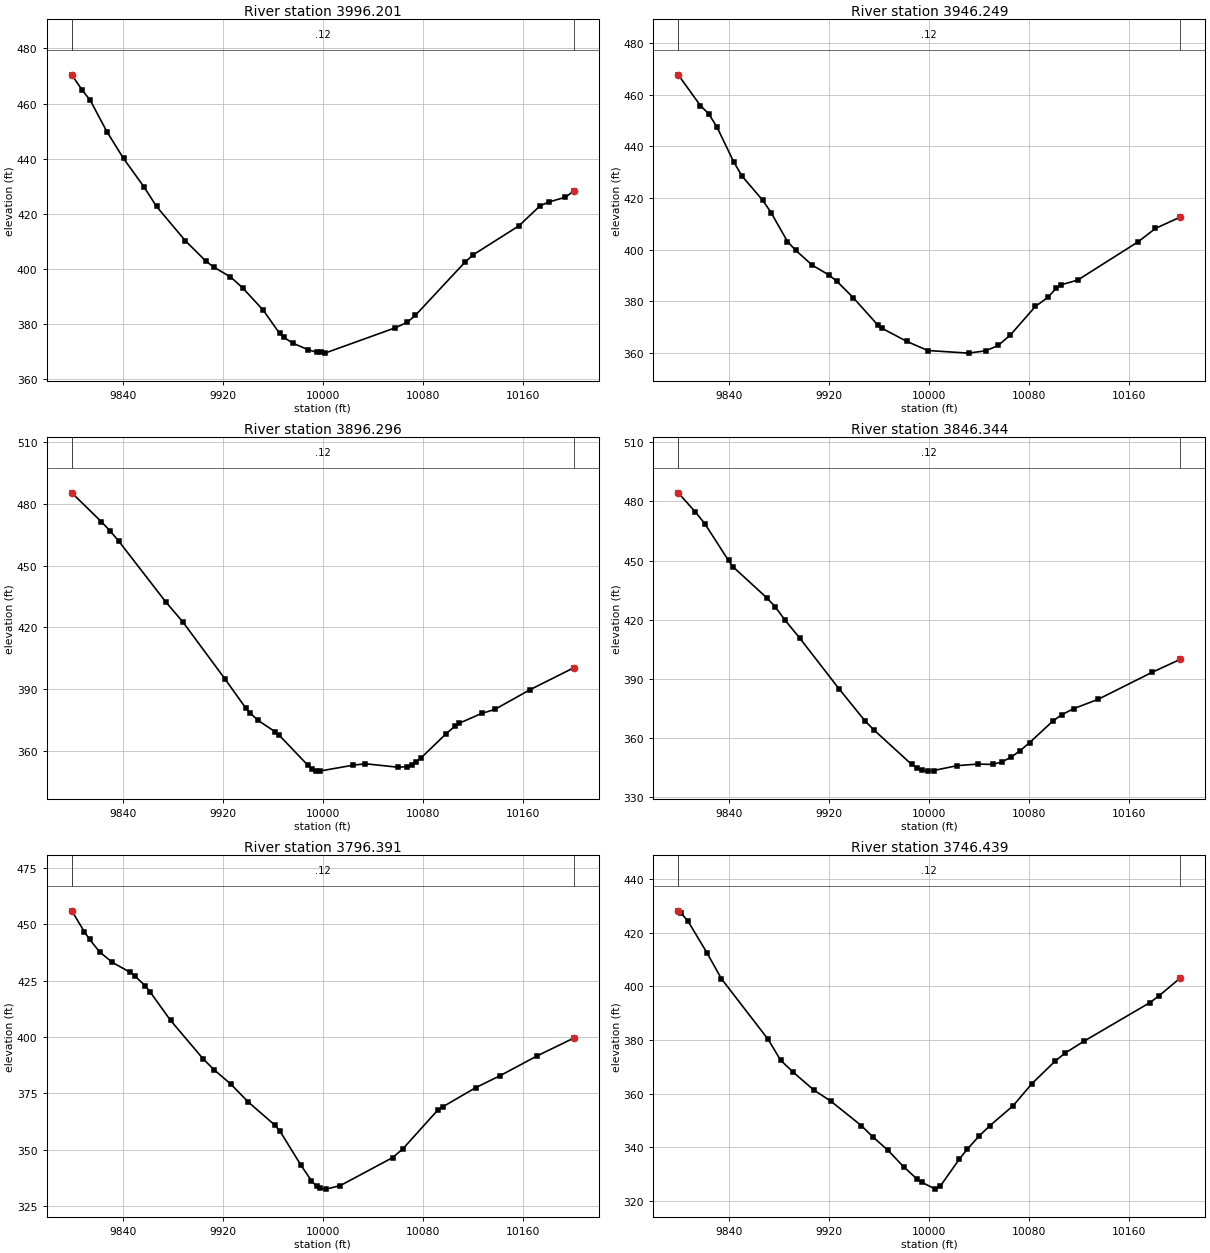
Type RM Length L Ch R = 1 ,3996.201,49.952500,49.952500,49.952500
XS GIS Cut Line= 6
1158794.35800505849239.5170271511158805.17865246849317.433069726
1158807.85953494849415.7827060371158814.06595296849463.102998589
1158819.39141855849545.1498159211158838.83670257849637.915177978
#Sta/Elev= 30
9799.048470.41599807.206 464.9889813.862461.15119827.173449.79929840.482  440.08
9856.977429.68519866.874422.66969889.904410.26689906.314402.87549912.878400.6197
9926.006397.14289935.852393.13089952.263385.06589965.391376.62669968.673375.2149
9976.138373.03949988.453370.66599995.064369.7678 9998.37369.945610001.69 369.465
10057.74 378.612 10067.6380.624810074.18383.208510113.72402.417810120.37 405.135
10157.01415.648810173.93422.9065 10180.7424.248410194.24426.039110200.95428.2973
#Mann= 3 , 0 , 0
9799.048    0.12       09799.048    0.12       010200.95    0.12       0
#XS Ineff= 2 , 0
       0                               0
Bank Sta=9799.048,10200.95
Exp/Cntr=0.3,0.1

Type RM Length L Ch R = 1 ,3946.249,49.952500,49.952500,49.952500
XS GIS Cut Line= 6
1158754.81217187849239.9850441341158766.43468322849304.130507628
1158770.40821421849364.9399849641158755.95058166849469.961121334
1158756.21539255849504.710193629 1158793.7197959849633.843154364
#Sta/Elev= 30
9799.112467.70739816.813455.82919823.481452.6254 9830.15447.44839843.487434.0439
9850.155428.52039866.792419.12779873.367414.42989886.518403.21019893.094399.8226
9906.245394.09479919.397390.33369925.973 387.8649939.126381.50339958.855 370.873
9962.144369.63629982.089364.54329998.799361.034310031.43  360.0210045.25360.9311
10055.09362.974410064.94367.049210084.88378.076810094.98381.636910101.75385.1994
10105.14386.410710118.73388.269210167.18403.111110181.03408.287410200.89412.6735
#Mann= 3 , 0 , 0
9799.112    0.12       09799.112    0.12       010200.89    0.12       0
#XS Ineff= 2 , 0
       0                               0
Bank Sta=9799.112,10200.89
Exp/Cntr=0.3,0.1

Type RM Length L Ch R = 1 ,3896.296,49.952500,49.952500,49.952500
XS GIS Cut Line= 6
1158669.92026191849228.2604871871158690.56651022849291.708753911
1158706.01198166849354.7004115851158719.95655054849483.359245938
1158730.97026726849517.6007445911158770.53478615849614.508004803
#Sta/Elev= 30
9799.089 485.2289822.835471.19029829.735466.78279836.636461.85739874.404432.2987
9887.916422.71639921.696395.05229938.417380.86649941.722378.52549948.333374.9302
9961.556369.55669964.861367.9444    9988353.23559991.306351.38989994.611350.3754
9997.917350.449510024.26353.254210034.11353.938510060.29352.264610067.62352.5729
10071.07353.219610074.52354.591410078.92356.955610098.71368.5036 10105.8372.1663
10109.34373.630510127.06378.319210137.69380.284210166.04389.886410200.93400.4745
#Mann= 3 , 0 , 0
9799.089    0.12       09799.089    0.12       010200.93    0.12       0
#XS Ineff= 2 , 0
       0                               0
Bank Sta=9799.089,10200.93
Exp/Cntr=0.3,0.1

Type RM Length L Ch R = 1 ,3846.344,49.952500,49.952500,49.952500
XS GIS Cut Line= 6
1158559.17406712849278.2759057171158631.28732303849398.285536901
1158684.91157218849458.4490427341158699.86118163 849479.28737765
1158732.52457639849541.3579146631158767.33754132849619.173323387
#Sta/Elev= 30
9799.051484.32839812.809474.58489820.373468.64689839.283450.02679843.065446.7243
9869.915431.1153 9876.51426.67249884.667419.68249896.365410.64719927.617 385.077
9948.556368.70859955.957363.95639985.796 346.6999990.453344.64789994.269343.6523
9998.891343.247810003.38343.541510022.25346.023810038.95346.829310050.61346.6358
10058.02347.877610065.44350.293610072.75353.641510080.27  357.69 10098.8368.5705
10106.22371.924510115.67374.926810135.26379.686110178.39393.365110200.92399.9193
#Mann= 3 , 0 , 0
9799.051    0.12       09799.051    0.12       010200.92    0.12       0
#XS Ineff= 2 , 0
       0                               0
Bank Sta=9799.051,10200.92
Exp/Cntr=0.3,0.1

Type RM Length L Ch R = 1 ,3796.391,49.952600,49.952600,49.952600
XS GIS Cut Line= 6
1158503.29470054   849334.3879551158548.84597834849397.717611338
 1158582.9072079849436.4967852831158701.12482287849530.110123251
1158728.07823453849568.7813112721158761.12250826849634.757351905
#Sta/Elev= 30
9799.076455.9538 9809.06446.77979813.361443.25239821.444437.70129831.535433.0985
9845.692428.74929849.733  427.029857.816422.71079861.857419.93629878.098407.4154
9904.298390.26679913.032385.47299926.269 379.1999940.421371.15749961.652360.9347
9965.813 358.1759982.458343.24139990.781336.37589994.942333.7995 9997.66332.9803
10002.67332.594710014.05 334.18410055.75346.542210063.81350.307210091.77367.5085
10095.89369.057810122.51377.6301 10142.1382.950910171.45391.648210200.87399.5631
#Mann= 3 , 0 , 0
9799.076    0.12       09799.076    0.12       010200.87    0.12       0
#XS Ineff= 2 , 0
       0                               0
Bank Sta=9799.076,10200.87
Exp/Cntr=0.3,0.1

Type RM Length L Ch R = 1 ,3746.439,49.952500,49.952500,49.952500
XS GIS Cut Line= 6
1158484.66604843849390.0264799341158574.43592565849495.308651277
1158652.49803833849544.8767793621158682.28314051 849571.40068774
1158713.88013848849614.5471908251158750.56304067849682.269311565
#Sta/Elev= 30
  9799.1428.2044 9801.53427.24799806.871424.37799822.285412.41229833.574402.9488
9870.958380.3438 9881.08372.50319890.944368.12559907.454361.45579921.222357.2549
9945.557348.17569954.718343.97999966.828339.00979979.559332.77179989.857328.3695
9993.844327.045610004.89324.4659 10008.7325.485310023.94335.568910030.42339.3407
10039.99344.307610048.32348.037510067.07355.525910081.89363.640910100.73372.1799
10108.64375.1558 10123.9379.625210176.67394.014810184.13396.616210200.92403.1903
#Mann= 3 , 0 , 0
  9799.1    0.12       0  9799.1    0.12       010200.92    0.12       0
#XS Ineff= 2 , 0
       0                               0
Bank Sta=9799.1,10200.92
Exp/Cntr=0.3,0.1

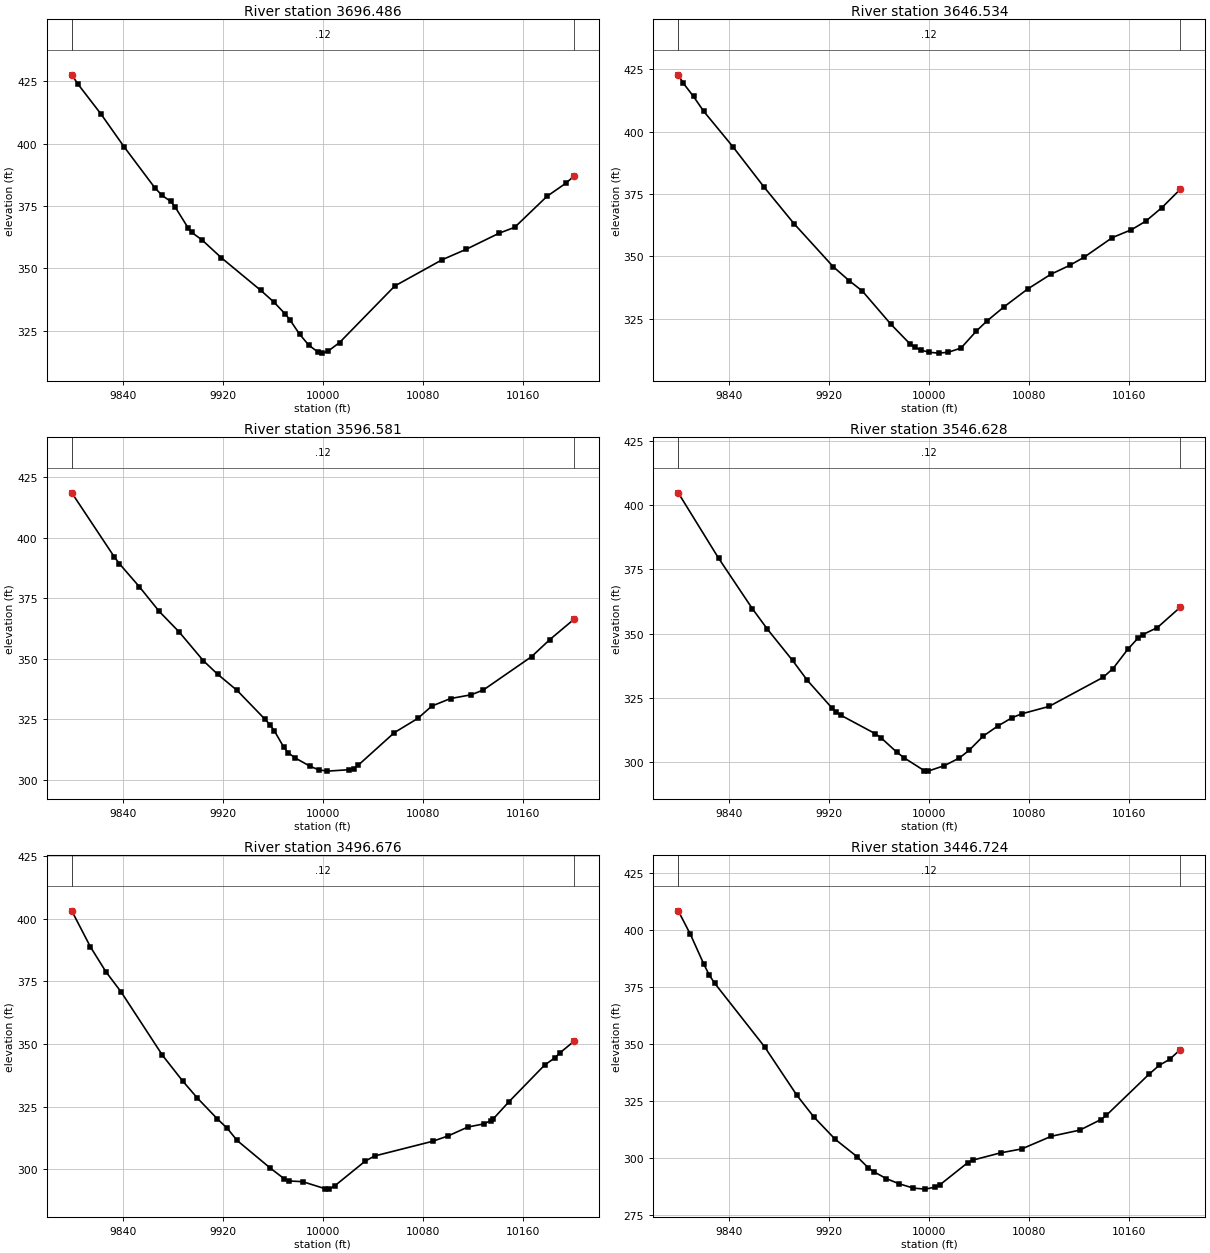
Type RM Length L Ch R = 1 ,3696.486,49.952500,49.952500,49.952500
XS GIS Cut Line= 6
1158468.82918722849394.5310787341158572.88023473849528.331959517
1158581.34284588849543.6727847071158593.10101444849573.531365487
1158605.29232388849597.9757840981158684.01310684849732.058439182
#Sta/Elev= 30
9799.058427.53199803.988423.82569822.503411.78569840.871398.74759865.594382.2659
9871.329379.25759878.162376.8759 9881.88374.53119892.431366.03879894.921364.4885
  9903.3361.42839918.809 354.2689950.462341.17639961.013336.45999970.147331.6353
9973.894 329.2679981.388323.69729988.723319.31289995.792316.63599999.322316.0846
10003.86316.7416 10013.4320.313110057.65342.975110095.69 353.51310114.76357.6581
10141.35 364.15510153.64366.464910179.39378.835210194.61384.138310200.98386.9004
#Mann= 3 , 0 , 0
9799.058    0.12       09799.058    0.12       010200.98    0.12       0
#XS Ineff= 2 , 0
       0                               0
Bank Sta=9799.058,10200.98
Exp/Cntr=0.3,0.1

Type RM Length L Ch R = 1 ,3646.534,49.952500,49.952500,49.952500
XS GIS Cut Line= 6
1158431.29797699849411.4667213381158481.98005717849482.732156027
1158511.15385228849527.2351877971158551.62964459849594.492471117
 1158593.2179303849671.9584388331158641.25203698849753.780942309
#Sta/Elev= 30
9799.019422.75039803.104 419.3679811.262414.07089819.314408.2048 9842.73393.9688
9867.624377.84439891.644363.15849923.028345.9046 9935.98340.22019946.382336.1444
9969.291322.80869984.564314.93869988.382313.58019993.436312.45389999.871311.5907
10007.61311.242910015.31 311.60610025.43 313.27910037.75 320.11610046.24324.1433
10060.09329.879410078.71336.909710097.33342.840610112.36346.394310123.77 349.605
 10146.6357.546110161.82360.670410173.23 364.07910186.26369.541610200.99376.9094
#Mann= 3 , 0 , 0
9799.019    0.12       09799.019    0.12       010200.99    0.12       0
#XS Ineff= 2 , 0
       0                               0
Bank Sta=9799.019,10200.99
Exp/Cntr=0.3,0.1

Type RM Length L Ch R = 1 ,3596.581,49.952500,49.952500,49.952500
XS GIS Cut Line= 6
1158394.60354448849426.2609839051158472.49073135849543.319324071
1158489.01633402849575.7977133671158502.06004333849615.735276201
1158517.64332541849649.0080724861158591.42226908849774.987145679
#Sta/Elev= 30
9799.061418.46219832.991392.08159837.157389.20289853.144379.6701 9869.13 369.437
9884.908361.04299904.407349.09249915.826343.51699931.422336.82669953.892 324.831
9957.573322.73719961.254320.10689968.616313.49959972.298311.11469977.471 309.062
9989.845305.49359996.773304.031110003.64303.4909   10021 304.06910024.62304.5668
10028.24305.882910057.31319.416910076.04325.263510087.28330.373610102.26333.4771
10118.82335.0348 10128.5337.005610167.12350.787610181.78 357.86310200.96366.1669
#Mann= 3 , 0 , 0
9799.061    0.12       09799.061    0.12       010200.96    0.12       0
#XS Ineff= 2 , 0
       0                               0
Bank Sta=9799.061,10200.96
Exp/Cntr=0.3,0.1

Type RM Length L Ch R = 1 ,3546.628,49.952500,49.952500,49.952500
XS GIS Cut Line= 6
1158342.84022642849458.1626130851158400.57270911849540.209090473
1158441.35963041849605.2631111691158469.97379122849646.297245377
1158522.47314609849733.7707030881158562.92763139849794.301032593
#Sta/Elev= 30
9799.023404.76519831.426  379.269858.429359.66889870.464351.69949890.522339.5926
9902.445331.79389921.807321.2434 9925.68319.40999929.552318.17499956.658311.1146
9961.644309.38679973.997303.88899980.022301.64469996.043296.6972    9999296.5284
10012.06298.657110024.02 301.61210031.76304.566510043.24310.172710054.72314.0265
 10066.2317.280810073.85318.792710095.86 321.68610139.23333.020710147.13336.4361
10158.96343.926610166.86348.1358 10170.8349.596910182.64352.365810200.98 360.279
#Mann= 3 , 0 , 0
9799.023    0.12       09799.023    0.12       010200.98    0.12       0
#XS Ineff= 2 , 0
       0                               0
Bank Sta=9799.023,10200.98
Exp/Cntr=0.3,0.1

Type RM Length L Ch R = 1 ,3496.676,49.952500,49.952500,49.952500
XS GIS Cut Line= 6
1158301.74839889849478.4357276291158384.74476936849593.256007915
1158402.66648303849626.1221721241158420.11405434849670.757373186
1158440.39066224849705.3315111711158520.01093361849813.966071996
#Sta/Elev= 30
9799.054403.2071    9814388.80739826.356378.90289838.711370.7089 9871.66345.5374
9887.773335.30549899.668328.43439915.528320.17779923.458316.42639931.388311.5453
9958.087300.44949969.297296.16979973.034295.36499983.888295.089110001.44292.3417
10004.97292.111210009.64293.454310033.78303.231310041.39 305.331 10088.1311.2337
10100.36313.359410116.09 316.898   10129 318.169 10134.4319.466110136.35320.1069
10148.74326.867510177.62341.667810185.91344.566810190.04346.606610200.94351.0887
#Mann= 3 , 0 , 0
9799.054    0.12       09799.054    0.12       010200.94    0.12       0
#XS Ineff= 2 , 0
       0                               0
Bank Sta=9799.054,10200.94
Exp/Cntr=0.3,0.1

Type RM Length L Ch R = 1 ,3446.724,49.952600,49.952600,49.952600
XS GIS Cut Line= 6
1158233.60223181849527.5428360751158344.28331124849652.186528335
 1158360.0902204849666.825219251 1158383.2873503849682.337591116
1158396.99512057849695.8830065271158502.05946876849825.035809129
#Sta/Elev= 30
9799.035408.57419808.816398.20249819.486385.20019823.874380.37149828.261376.7431
9868.109348.92229894.076327.55769907.638318.05689924.789308.23659942.226300.6295
9951.115295.79649955.503294.06419965.728290.99469975.761288.77349987.272286.8582
9996.828286.409210004.66287.319710008.64288.360510030.66297.971110035.38299.2212
10057.09302.3323   10074304.055610097.76309.631610120.52312.313810137.44316.9604
10141.67318.778210175.75336.774810183.96340.701610192.42343.392510200.95347.6626
#Mann= 3 , 0 , 0
9799.035    0.12       09799.035    0.12       010200.95    0.12       0
#XS Ineff= 2 , 0
       0                               0
Bank Sta=9799.035,10200.95
Exp/Cntr=0.3,0.1