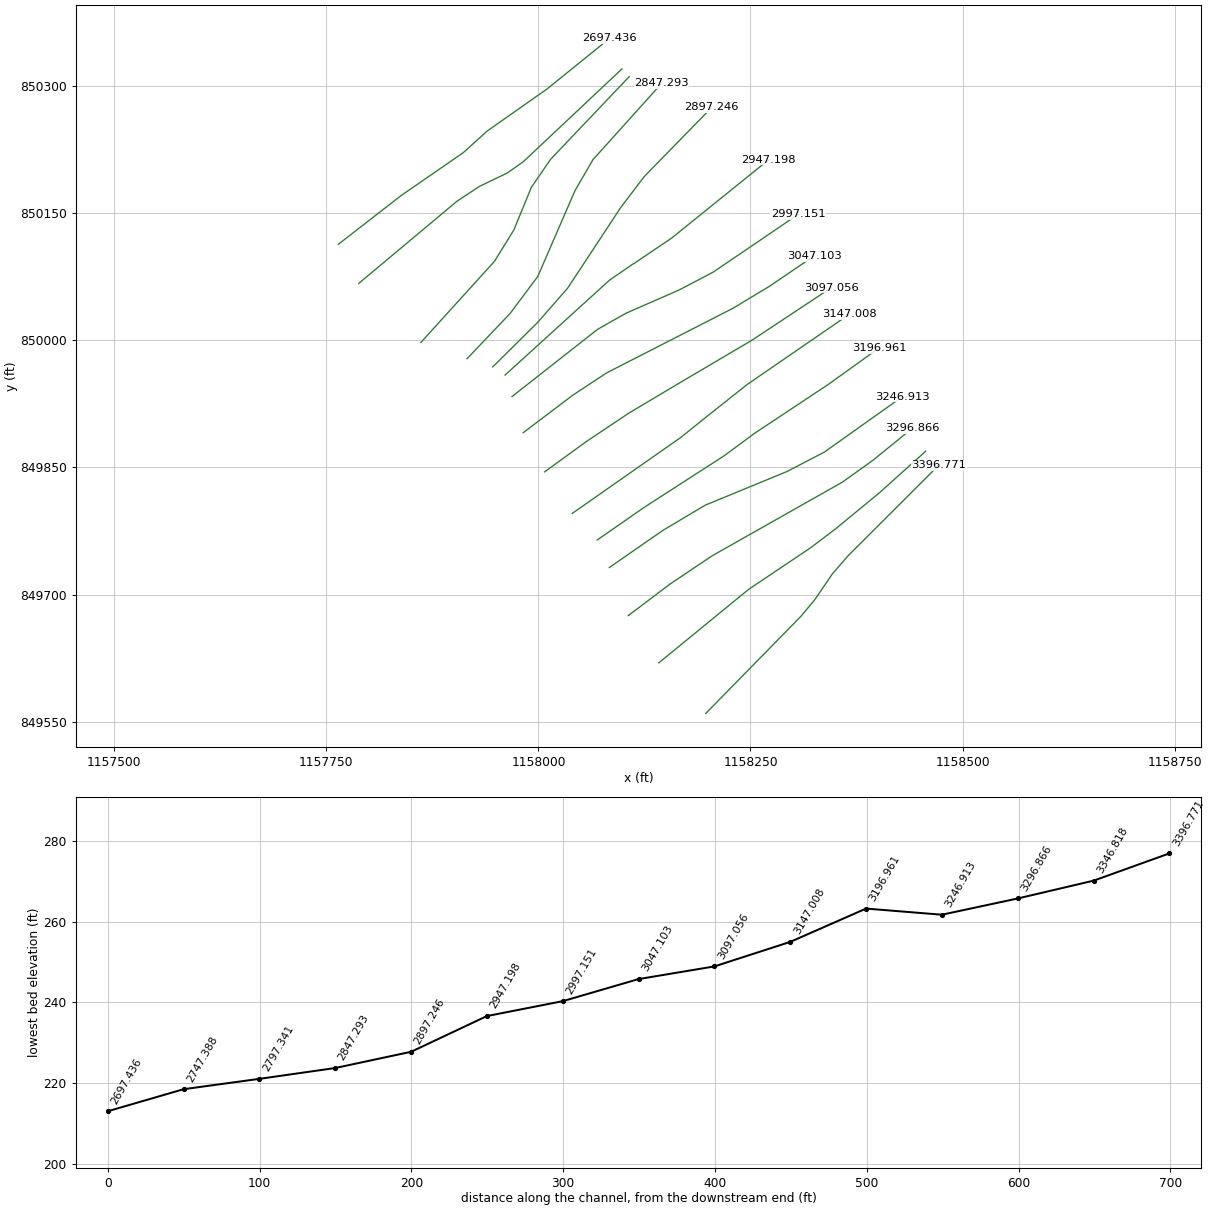
HEC-RAS study 177_ras.prj: 177

--- 177_ras.g01 (geometry) --- (continued)

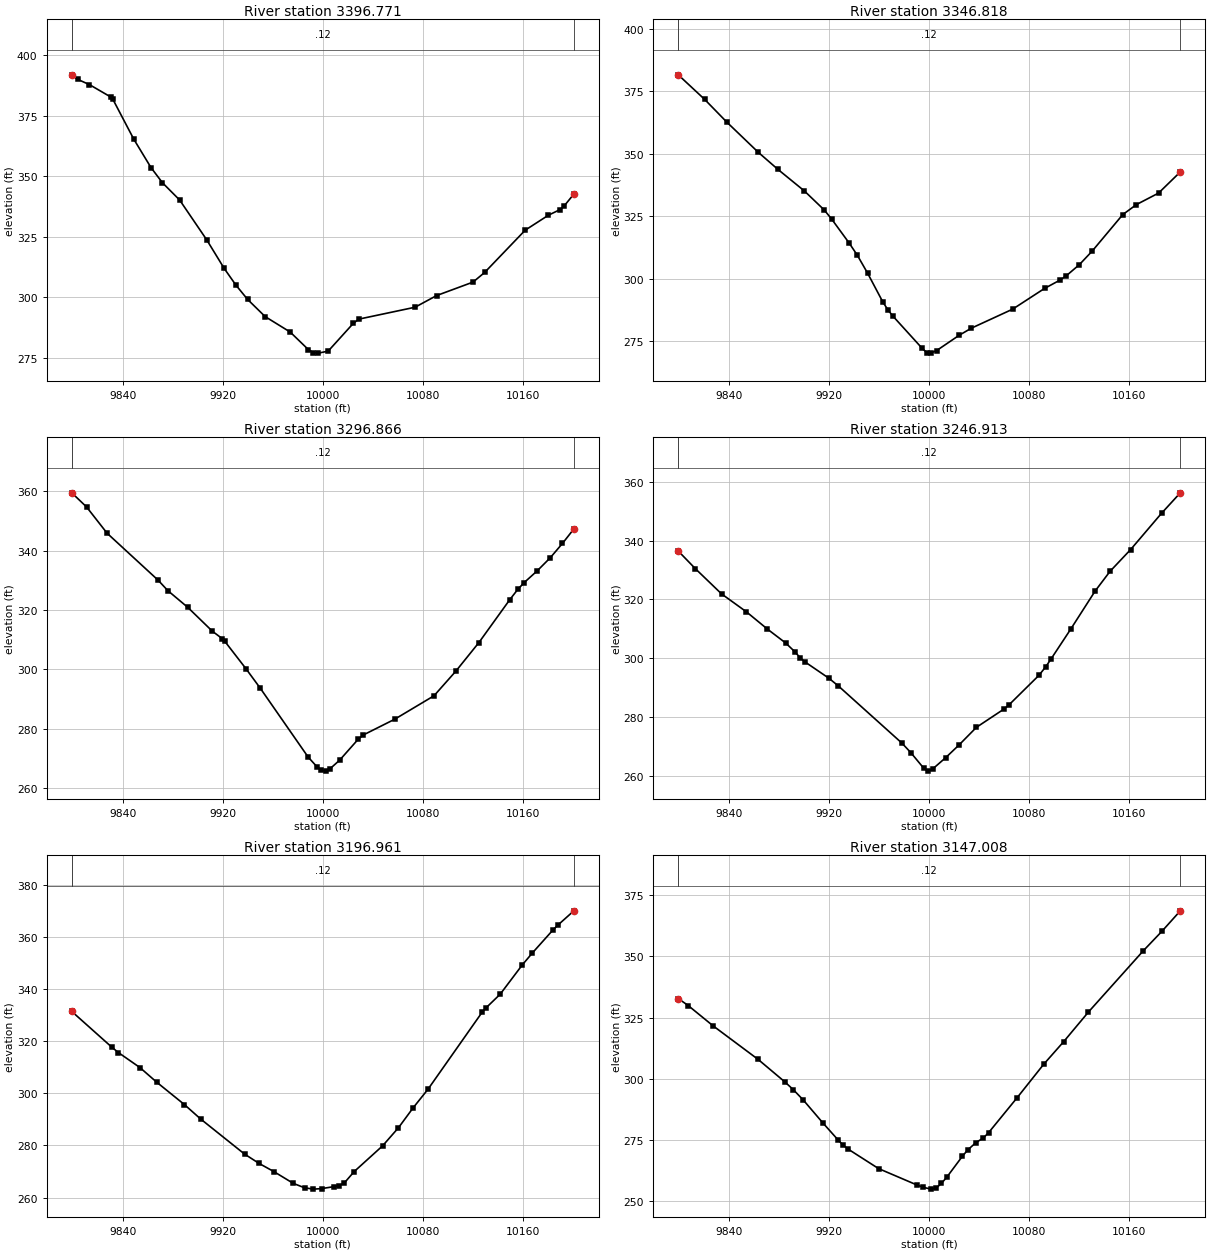
Type RM Length L Ch R = 1 ,3396.771,49.952500,49.952500,49.952500
XS GIS Cut Line= 6
1158197.35854361849559.8838106131158309.23012554849674.080078212
1158325.89760411 849694.004470441158346.65158762849724.531719721
1158365.19126566849745.8208161031158472.00989695849852.488790811
#Sta/Elev= 30
9799.024391.97689803.837390.08239813.213387.91719830.271382.79819831.966381.8227
9848.643365.39649862.421353.65329871.607347.36389885.385340.22139906.978323.8272
9921.043311.94379930.419305.04829939.796299.11999953.861292.01699973.858285.6453
 9988.52 278.3379992.481277.12579996.441276.9205 10004.3277.748710024.39289.2133
10028.83290.973310073.83295.893110091.14300.724510120.26306.286910129.55310.2667
10162.05327.764110180.62333.942710189.91336.255810193.15337.732610200.97342.6597
#Mann= 3 , 0 , 0
9799.024    0.12       09799.024    0.12       010200.97    0.12       0
#XS Ineff= 2 , 0
       0                               0
Bank Sta=9799.024,10200.97
Exp/Cntr=0.3,0.1

Type RM Length L Ch R = 1 ,3346.818,49.952500,49.952500,49.952500
XS GIS Cut Line= 6
1158141.95887896849619.4635057281158247.86450909 849706.12797702
1158320.89368786849755.1177245431158349.95994908849777.118529675
1158402.35105855849820.2328145721158456.47927005849868.921618539
#Sta/Elev= 30
9799.016381.62239820.159371.78469837.761362.75729863.106350.5902 9878.83343.7496
9900.017335.11049915.906327.4969 9921.81323.87399935.884314.23859942.489309.2911
9950.582302.22649962.721290.73789966.767 287.5779970.814285.02859994.278 272.103
 9998.15270.3051   10001 270.16910005.87271.183710023.87277.298510033.63280.1436
10066.75 287.77610092.25296.068710104.68299.424610109.84 301.20810120.17305.6098
10130.38311.003110154.91325.654610165.88 329.66710183.53334.252110200.98342.7352
#Mann= 3 , 0 , 0
9799.016    0.12       09799.016    0.12       010200.98    0.12       0
#XS Ineff= 2 , 0
       0                               0
Bank Sta=9799.016,10200.98
Exp/Cntr=0.3,0.1

Type RM Length L Ch R = 1 ,3296.866,49.952500,49.952500,49.952500
XS GIS Cut Line= 6
1158105.96845666849675.1871628991158155.13649821849712.302569958
1158204.64600297849745.5612058711158358.04121302849832.298081571
1158394.11804697849858.0799395871158440.75350086849895.962269888
#Sta/Elev= 30
9799.022359.4846 9810.87354.72449827.312345.87929868.119330.07469876.023  326.51
9891.833320.93799911.595312.86989919.499 310.3799921.627309.42689938.533300.2166
9949.935 293.6839988.263270.49149995.201267.27719998.589266.152910002.28265.7596
   10006266.638210013.45269.442710028.33276.496910032.05277.858210057.57283.2409
10089.04291.141710106.54 299.44310124.98309.068810149.57323.440810156.05326.9413
10161.25329.276810171.66333.221510182.07337.608110191.84342.438610200.97347.3166
#Mann= 3 , 0 , 0
9799.022    0.12       09799.022    0.12       010200.97    0.12       0
#XS Ineff= 2 , 0
       0                               0
Bank Sta=9799.022,10200.97
Exp/Cntr=0.3,0.1

Type RM Length L Ch R = 1 ,3246.913,49.952500,49.952500,49.952500
XS GIS Cut Line= 6
1158083.65837752849731.8582652431158146.64937341849775.552045554
1158196.73019911 849805.353174051158292.67831732849844.821208427
1158337.03842701 849867.889655861158429.19063049849933.342924242
#Sta/Elev= 30
9799.049336.44049812.781330.43889833.717321.89229853.681315.78269870.344309.9727
9885.189305.17789892.825302.07229896.642300.1905 9900.46298.82299919.549 293.292
9927.185290.66019978.149271.22339985.145268.0566 9995.64262.68599999.137  261.74
10002.62262.439810013.15266.318410023.69270.571310037.73276.604110059.92282.8455
10063.61284.148810087.83294.273310093.36297.246910097.44299.791910113.13309.8788
10132.73322.850310144.69329.553110161.18336.947710185.93349.262910200.93356.1922
#Mann= 3 , 0 , 0
9799.049    0.12       09799.049    0.12       010200.93    0.12       0
#XS Ineff= 2 , 0
       0                               0
Bank Sta=9799.049,10200.93
Exp/Cntr=0.3,0.1

Type RM Length L Ch R = 1 ,3196.961,49.952500,49.952500,49.952500
XS GIS Cut Line= 6
1158069.39756725849764.3307445411158124.37491042 849802.54419126
1158218.69833018849863.3818588871158255.45719404849890.469030045
1158342.38586331849948.1242602351158401.49850804849990.619498721
#Sta/Elev= 30
9799.014331.39989831.095317.68229836.309315.63589853.554309.8867 9867.03304.2621
9889.214 295.6749902.166 290.1599937.303276.71479949.015273.10329960.727270.0079
9976.343265.46729985.424263.76359992.519263.2571    9999263.454310008.86264.2106
10013.05 264.63610017.01265.513110025.12269.991210047.86279.854310060.56286.7965
10072.37294.468510084.18301.545110127.48331.046610130.81332.833310142.05338.0325
10159.79349.299610167.87353.871310184.03362.515110188.07364.454610200.98369.9834
#Mann= 3 , 0 , 0
9799.014    0.12       09799.014    0.12       010200.98    0.12       0
#XS Ineff= 2 , 0
       0                               0
Bank Sta=9799.014,10200.98
Exp/Cntr=0.3,0.1

Type RM Length L Ch R = 1 ,3147.008,49.952500,49.952500,49.952500
XS GIS Cut Line= 6
1158040.03807164849795.7048336811158167.37628169849884.841440009
1158202.12350525849912.7126600261158203.69050065849913.955449403
1158245.94493234849947.4539465641158366.28531559850030.210946521
#Sta/Elev= 30
 9799.02332.76089806.941329.91759826.965321.60369863.008307.91099884.408298.7383
9891.041295.6309 9899.05291.4088 9915.07281.86779927.084275.01939931.089272.9258
9935.093271.31379959.356263.40039989.882256.75059995.125255.7654 10001.4255.0094
10005.59255.462410009.78257.400210013.96259.839110026.52268.424210030.71270.9609
10037.35274.005210043.27275.871110047.46278.030810070.39292.344210091.62305.9535
10107.55315.140910127.46327.281510171.26352.198610186.19360.162110200.97368.5396
#Mann= 3 , 0 , 0
 9799.02    0.12       0 9799.02    0.12       010200.97    0.12       0
#XS Ineff= 2 , 0
       0                               0
Bank Sta=9799.02,10200.97
Exp/Cntr=0.3,0.1

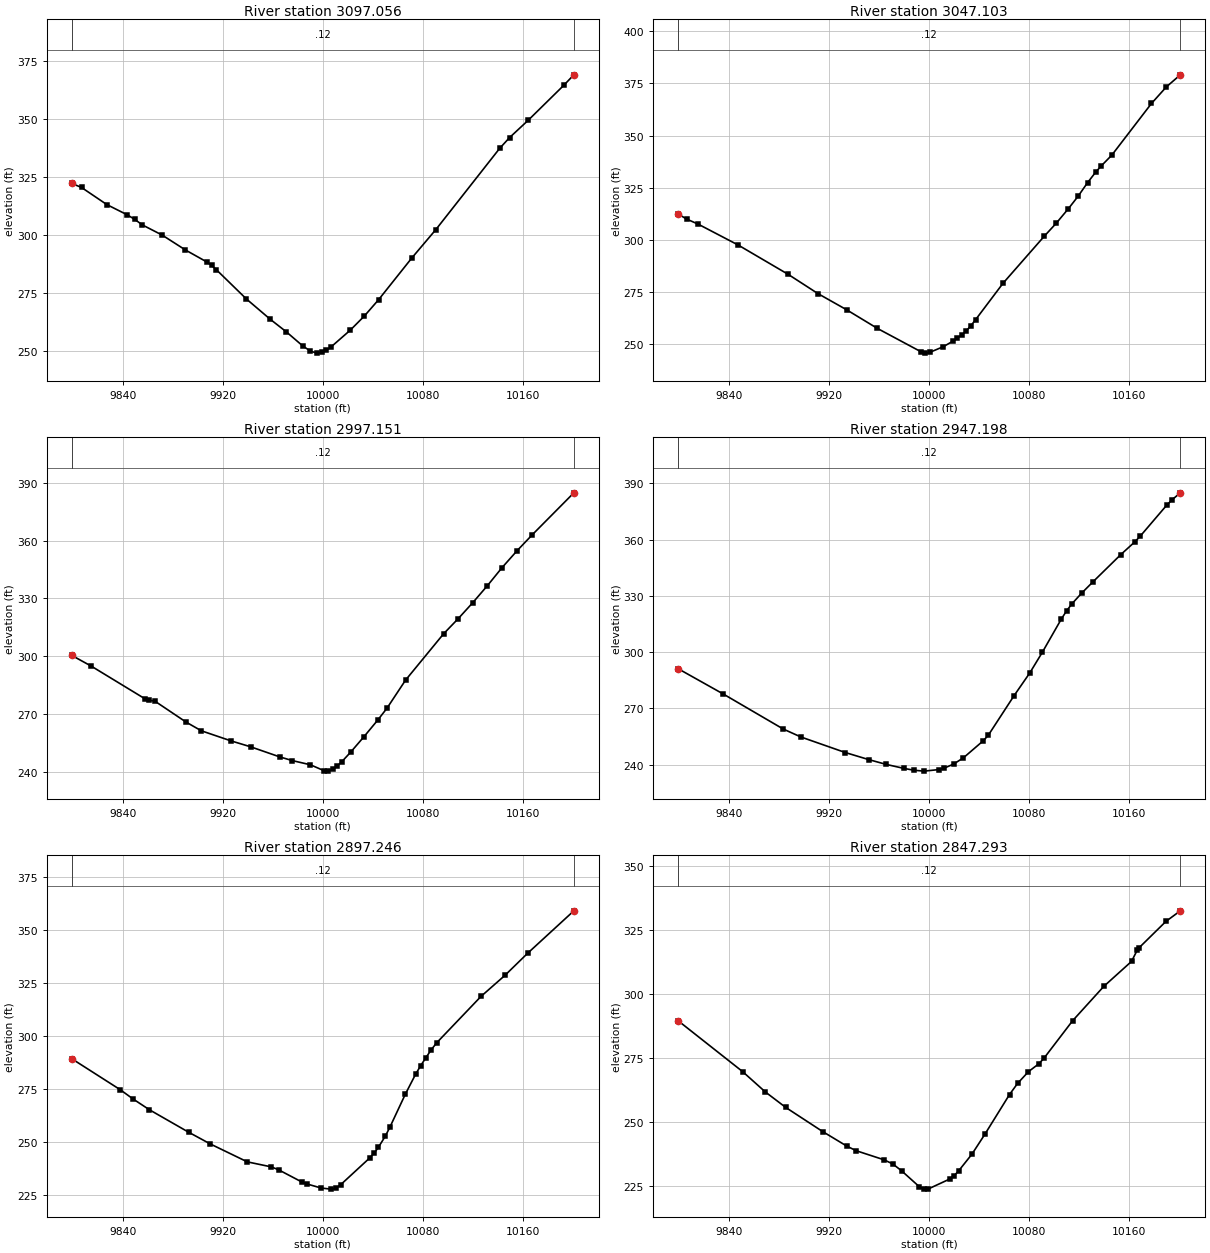
Type RM Length L Ch R = 1 ,3097.056,49.952500,49.952500,49.952500
XS GIS Cut Line= 6
1158007.38641058849844.6043196431158055.96434732849879.970678668
1158106.61187055849913.8414099551158174.45740815849954.229251209
1158251.01639879849999.3362827421158345.34570437850061.746812871
#Sta/Elev= 30
9799.025322.16129806.858320.40629827.149313.01199843.382308.62999849.308  306.69
9855.557304.25019871.442299.85459890.044293.43749906.964288.32439910.911286.8178
9914.857284.88549938.753272.33669957.994 263.5099970.822258.11229983.753252.1256
9990.064249.80829995.208 248.9369999.026249.231610002.81250.187210006.62251.6187
10021.86258.782710033.28264.952510044.71272.023410071.37290.0657 10090.5302.2431
10141.64337.318310149.51341.935810164.31349.347410192.78364.421910200.97369.0174
#Mann= 3 , 0 , 0
9799.025    0.12       09799.025    0.12       010200.97    0.12       0
#XS Ineff= 2 , 0
       0                               0
Bank Sta=9799.025,10200.97
Exp/Cntr=0.3,0.1

Type RM Length L Ch R = 1 ,3047.103,49.952600,49.952600,49.952600
XS GIS Cut Line= 6
1157982.12024277849890.8141464471158040.19462631849934.717525209
1158080.41988994849961.2816396161158229.08660867850037.292459064
1158272.57015531850063.4943615011158324.78923173850099.003184713
#Sta/Elev= 30
9799.029312.41039805.738310.02719815.001307.58239846.867297.63199887.037283.5362
9910.874274.31319933.823 266.5739958.476257.63369993.022246.56789996.682245.8002
10000.36 246.15710011.37248.9261 10018.7 251.45910022.37252.941210026.03254.5258
 10029.7256.485510033.36258.993910037.03 261.79110059.02279.255510092.23301.9236
10101.59307.995910111.39315.018810119.05320.885410126.71327.464810133.38332.6271
10137.81 335.57410146.15340.665510177.89365.417810189.79373.330610200.96379.1202
#Mann= 3 , 0 , 0
9799.029    0.12       09799.029    0.12       010200.96    0.12       0
#XS Ineff= 2 , 0
       0                               0
Bank Sta=9799.029,10200.96
Exp/Cntr=0.3,0.1

Type RM Length L Ch R = 1 ,2997.151,49.952500,49.952500,49.952500
XS GIS Cut Line= 6
1157968.83458946849933.3457069751158069.59621211850012.482817061
1158102.86446106850031.4173680271158166.05719026850059.063184777
 1158206.1916439850080.166496012 1158306.3517729850148.194424432
#Sta/Elev= 30
9799.053300.42969814.735294.82489857.341278.01119860.618277.25689865.862276.5498
9890.538265.80079902.727261.28649926.406256.06629942.215252.96519965.513247.7273
9975.658245.78889990.004243.643510000.75240.621310004.32240.3284 10007.9241.2269
10011.48242.926210015.05245.108110022.21250.108110032.94258.193210044.01266.8611
10051.42273.046610066.25287.5875 10096.7311.649210108.37319.496210120.05327.8085
10131.72336.6116 10143.5346.025910155.65354.888210167.79363.152110200.96384.8555
#Mann= 3 , 0 , 0
9799.053    0.12       09799.053    0.12       010200.96    0.12       0
#XS Ineff= 2 , 0
       0                               0
Bank Sta=9799.053,10200.96
Exp/Cntr=0.3,0.1

Type RM Length L Ch R = 1 ,2947.198,49.952500,49.952500,49.952500
XS GIS Cut Line= 6
1157960.70713326849958.7345799521158083.93130629850070.689074158
1158111.49280347850089.6236642291158113.24523532850090.587501679
1158157.23874169850120.3394980521158271.49664123850212.553503131
#Sta/Elev= 30
9799.074291.15829835.236277.67189883.155259.05139897.294254.81689932.756246.5549
 9951.46242.80159965.561240.21879979.888 238.0719987.849237.11859995.809236.6432
10007.59237.457410011.55238.132510019.47240.393110027.39243.758610043.24252.8216
 10047.2255.702710067.83 276.79210080.48288.958510090.55299.998310105.78317.7285
10109.99322.075810114.21325.7696 10121.9331.390310131.07337.485610153.24351.9281
 10164.8358.909210169.02361.9088 10190.1378.316910194.31381.149710200.94384.8632
#Mann= 3 , 0 , 0
9799.074    0.12       09799.074    0.12       010200.94    0.12       0
#XS Ineff= 2 , 0
       0                               0
Bank Sta=9799.074,10200.94
Exp/Cntr=0.3,0.1

Type RM Length L Ch R = 1 ,2897.246,49.952500,49.952500,49.952500
XS GIS Cut Line= 6
1157946.11337458849968.2771863381157999.14597671850020.804158807
1158034.40603881 850061.088819651158097.06590595850156.273746254
1158124.77980435850192.7280872021158204.31715893850274.218128424
#Sta/Elev= 30
 9799.04 289.3449837.852274.72099848.016270.38359861.163265.27679892.495254.6936
9909.935249.12029939.556240.66269958.877238.27999964.708236.88639983.154231.1791
9987.014230.27529998.596228.329310006.35227.792510010.23228.108610014.29 229.869
10037.44242.450610041.34 244.99310044.47247.515610049.89252.6467 10053.7257.0358
10066.15272.715110074.31 282.05710078.43286.147310082.55289.864310086.67293.4798
10091.08296.823910126.61 318.75410145.76328.677410164.02339.168510200.96359.1717
#Mann= 3 , 0 , 0
 9799.04    0.12       0 9799.04    0.12       010200.96    0.12       0
#XS Ineff= 2 , 0
       0                               0
Bank Sta=9799.04,10200.96
Exp/Cntr=0.3,0.1

Type RM Length L Ch R = 1 ,2847.293,49.952500,49.952500,49.952500
XS GIS Cut Line= 6
1157915.80102091849977.9489277341157966.52082079850031.164019284
1157999.22434577850074.9076683251158043.14235164850176.192149492
1158064.28385967850212.580607054 1158145.0981792 850302.39977769
#Sta/Elev= 30
 9799.08 289.5929850.644269.71759868.774261.78669885.125255.71729914.631 246.301
9934.018240.5862 9941.44238.80489963.706235.25799970.821233.60919977.838230.9363
9991.871224.77949995.379 223.7959998.888223.774810016.49227.759410020.02229.0849
10023.54230.955710034.13237.450210044.56245.2951 10064.2260.772810070.68265.1326
10079.38269.7273 10087.7272.801310091.89275.042310114.69289.627610139.62303.0502
10161.84312.830210166.42317.2549 10167.8318.120210189.35328.469310200.88332.6111
#Mann= 3 , 0 , 0
 9799.08    0.12       0 9799.08    0.12       010200.88    0.12       0
#XS Ineff= 2 , 0
       0                               0
Bank Sta=9799.08,10200.88
Exp/Cntr=0.3,0.1

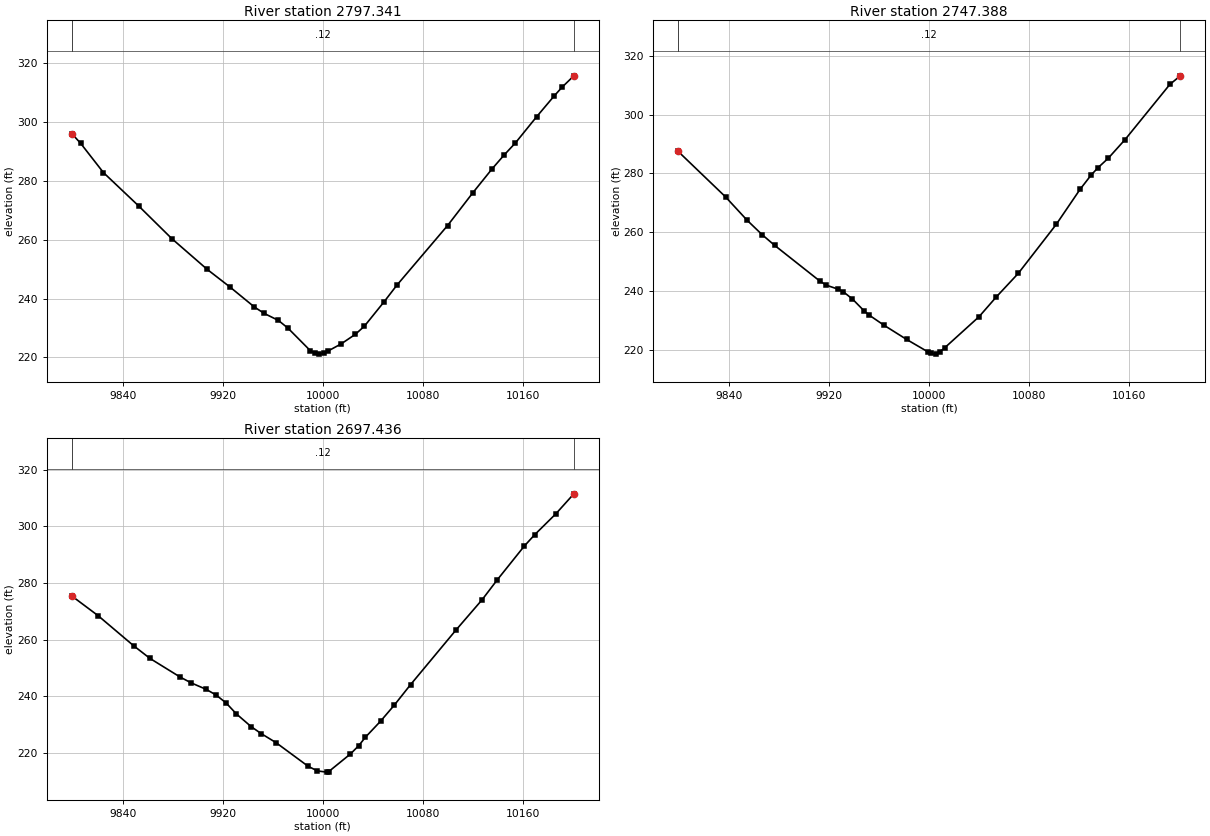
Type RM Length L Ch R = 1 ,2797.341,49.952500,49.952500,49.952500
XS GIS Cut Line= 6
 1157861.4553353849997.1477092941157948.30097602850092.909980781
1157971.04500412850129.7630459951157991.67981344850179.984087031
1158014.30900077850212.9833690621158107.10274977850310.560639751
#Sta/Elev= 30
9799.112296.13129806.116292.86969824.485282.85139852.611271.52539879.163260.3965
9907.429249.94769925.714243.9286 9945.24237.13249952.951 234.9799964.517232.5508
9972.195229.90459989.922222.30649993.468221.39259997.013221.094210000.55221.4456
10004.09222.128810014.75 224.59610026.12227.862310033.27230.602610049.18238.9826
10059.29244.566310099.83264.844710120.13276.042510135.49284.146610144.83  288.72
10154.17292.983110171.08 301.85710184.91308.829310191.53311.951910200.88315.7888
#Mann= 3 , 0 , 0
9799.112    0.12       09799.112    0.12       010200.88    0.12       0
#XS Ineff= 2 , 0
       0                               0
Bank Sta=9799.112,10200.88
Exp/Cntr=0.3,0.1

Type RM Length L Ch R = 1 ,2747.388,49.952500,49.952500,49.952500
XS GIS Cut Line= 6
1157788.15168506850066.7100902431157904.31494403 850163.85675753
1157930.51592707850181.1482286261157963.21941943850196.842753086
1157982.27357096 850210.283036951158098.39410294850319.549168584
#Sta/Elev= 30
9799.043287.47539836.885 272.0429854.179 264.0779866.157259.18789876.233255.5284
9912.188 243.4549917.445242.00679926.754240.66349930.954239.8147 9938.47237.2872
9947.751233.27719951.857231.8124 9963.65228.38599981.888 223.517    9999219.2746
10001.34218.766510004.99218.527810008.64219.3399 10012.3220.666910039.82 231.261
10053.75 238.03910071.15 245.96310101.62262.6711 10120.7274.607810129.71279.5457
10135.14281.997710143.23285.168210156.74291.544710192.59310.312710200.93313.2208
#Mann= 3 , 0 , 0
9799.043    0.12       09799.043    0.12       010200.93    0.12       0
#XS Ineff= 2 , 0
       0                               0
Bank Sta=9799.043,10200.93
Exp/Cntr=0.3,0.1

Type RM Length L Ch R = 1 ,2697.436,49.952600,49.952600,49.952600
XS GIS Cut Line= 6
 1157764.1238807850112.8590327031157838.19711479850170.323944662
1157911.47311198850220.9101758511157939.69846088 850246.42722164
1158010.21592449850295.9887572671158083.99539379850355.638904611
#Sta/Elev= 30
9799.041275.41259820.121268.44279848.585257.79299861.644253.31299886.052  246.65
 9894.78244.62959906.741242.34769914.714 240.3229922.687237.51829930.661 233.744
9942.621229.17679950.594226.73159962.554223.50849988.358215.10839995.729213.4992
10002.98213.072410004.68213.241710022.14219.5081 10028.7222.407110034.17225.4541
 10046.2231.082510057.23236.781410070.26244.044410106.36263.233310127.46274.0454
10139.68281.140610161.21293.026210169.65297.109710186.53304.476910200.96311.5626
#Mann= 3 , 0 , 0
9799.041    0.12       09799.041    0.12       010200.96    0.12       0
#XS Ineff= 2 , 0
       0                               0
Bank Sta=9799.041,10200.96
Exp/Cntr=0.3,0.1