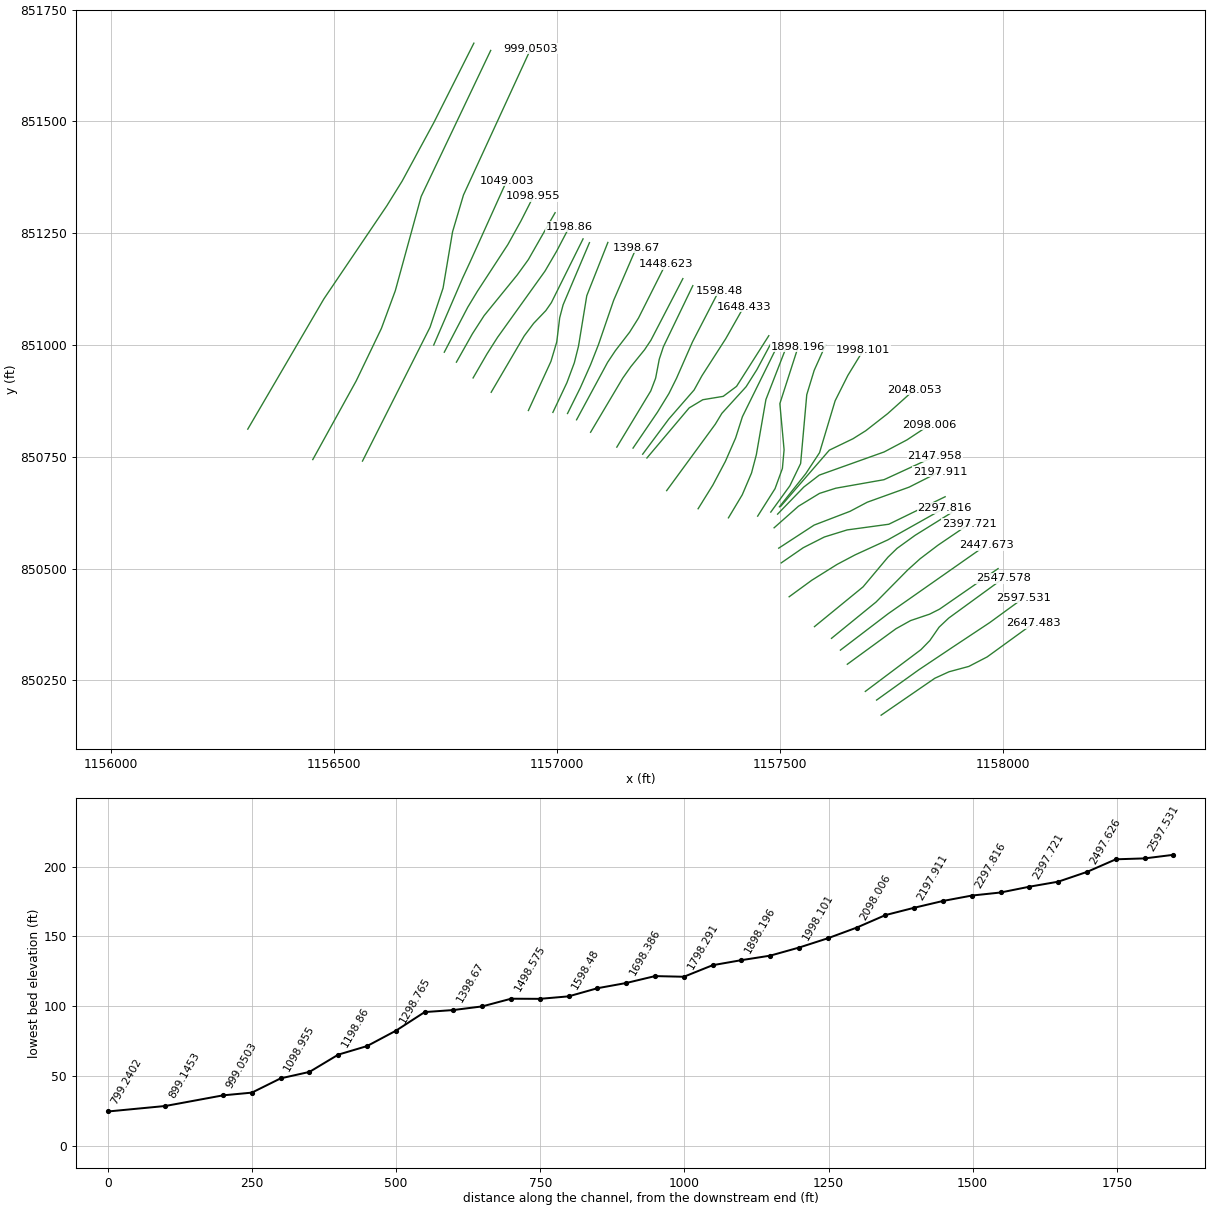
HEC-RAS study 177_ras.prj: 177

--- 177_ras.g01 (geometry) --- (continued)

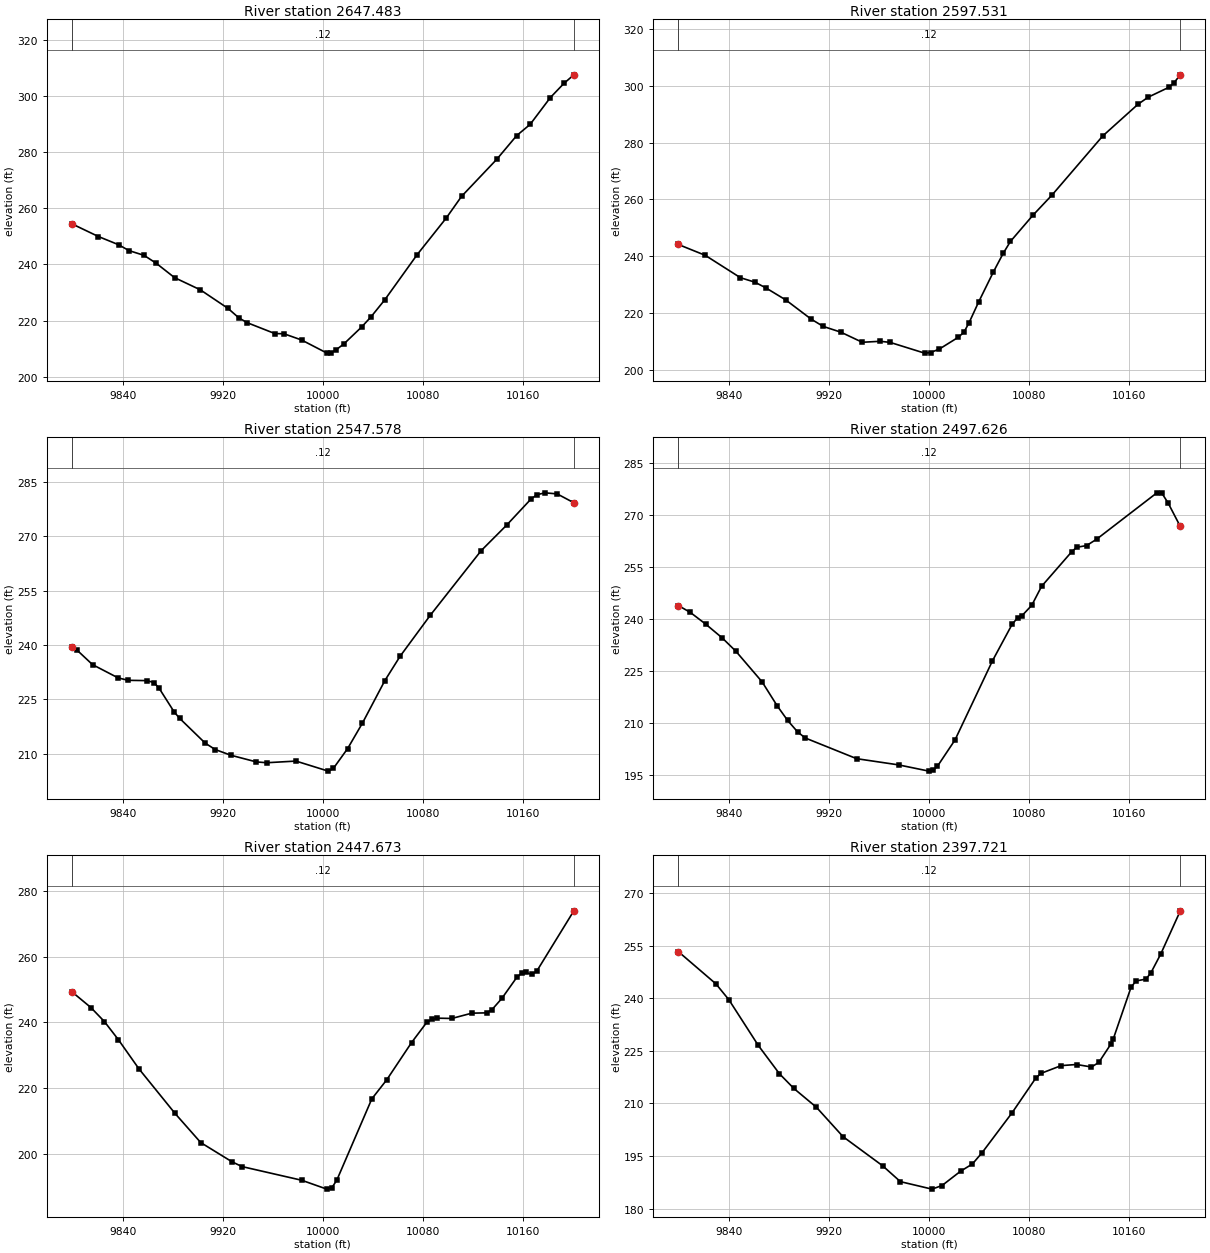
Type RM Length L Ch R = 1 ,2647.483,49.952500,49.952500,49.952500
XS GIS Cut Line= 6
1157727.46287386 850172.184331821157847.80471076850254.745123286
1157879.64254641 850269.265876781157924.03908777  850281.2163852
1157965.19872101850302.4998107991158069.18973979850377.757363982
#Sta/Elev= 30
9799.097 254.4319820.423249.89389836.667246.9605 9844.79244.90129856.973243.1922
9866.864240.31939881.341235.26869901.989230.92479924.091224.33369932.841 220.935
9939.587219.21259961.605215.36419968.916215.28689983.049 213.06710003.34208.4009
10006.76208.620710010.17209.4071   10017211.745310031.04217.693710038.42221.2408
 10049.5227.329110075.56 243.48810098.79256.493310111.04264.193310139.25277.4077
10155.12285.808610165.91289.804210182.09299.349810192.99304.407710200.88307.4395
#Mann= 3 , 0 , 0
9799.097    0.12       09799.097    0.12       010200.88    0.12       0
#XS Ineff= 2 , 0
       0                               0
Bank Sta=9799.097,10200.88
Exp/Cntr=0.3,0.1

Type RM Length L Ch R = 1 ,2597.531,49.952500,49.952500,49.952500
XS GIS Cut Line= 6
1157717.28843716850205.9837644331157811.68627205850273.514305725
1157881.51207438850320.0626767391157883.16015826850321.195734338
 1157970.8011487 850379.142363861158047.56127413850434.978051862
#Sta/Elev= 30
9799.015244.10539820.605 240.2849848.843232.3821 9860.32 230.8329869.012228.8511
9885.148224.5502 9905.43217.80429915.081 215.2419929.196 213.2139946.361209.6555
 9960.74209.99769968.626209.61599996.227205.8314   10001206.024510008.06207.2671
10023.34211.443710027.72213.195110031.66216.353110039.52223.841810051.32234.4093
10059.19240.972510064.98 245.16510082.82254.302910098.52261.625710138.85282.2903
10167.25293.522610175.36295.987410191.59299.388310195.65300.872610200.99303.8372
#Mann= 3 , 0 , 0
9799.015    0.12       09799.015    0.12       010200.99    0.12       0
#XS Ineff= 2 , 0
       0                               0
Bank Sta=9799.015,10200.99
Exp/Cntr=0.3,0.1

Type RM Length L Ch R = 1 ,2547.578,49.952500,49.952500,49.952500
XS GIS Cut Line= 6
1157692.02557233850225.3530485061157816.66759743850318.657378252
 1157836.7503698850339.1861432791157857.44594746850369.082011301
 1157879.0577102850389.3636264051158001.55316652850478.347891853
#Sta/Elev= 30
9799.085239.45079803.397238.54549815.692234.58449836.183230.9193 9844.38230.2469
9859.132230.16849864.871229.63599868.969228.07619881.031221.52919885.362 219.778
9905.853 212.9219913.879211.15089926.345209.58199946.727207.73789955.069207.5035
9978.527207.961810004.37205.187510008.41205.916810019.87211.412610031.72218.4414
10049.69230.190210061.86 236.88610086.19248.280110126.74266.033610147.02273.0407
10166.61280.274310171.35281.469210177.78281.995210187.57281.699310200.92279.2584
#Mann= 3 , 0 , 0
9799.085    0.12       09799.085    0.12       010200.92    0.12       0
#XS Ineff= 2 , 0
       0                               0
Bank Sta=9799.085,10200.92
Exp/Cntr=0.3,0.1

Type RM Length L Ch R = 1 ,2497.626,49.952500,49.952500,49.952500
XS GIS Cut Line= 6
1157651.68007254850286.121300274 1157760.6072639850365.416431998
1157793.37975251850383.6874868951157836.25485522850398.135446954
 1157858.4719931850409.3264212241157989.66123718850499.944068257
#Sta/Elev= 30
9799.079243.90959808.722241.92779821.035238.54879834.278234.56869845.199230.7328
9866.181221.91169878.493214.88459886.624210.79649894.591207.49319900.737205.7278
9941.909199.75979975.394197.97789999.726196.174210003.15196.403210006.59197.5994
10020.62205.1678 10050.6227.976710066.32238.480610070.65240.354910074.18 240.957
10082.04243.9638 10089.9249.4328 10113.9259.348710117.92260.682910125.95261.1846
10133.99263.0225 10182.2276.384110186.22276.259410191.13273.493810200.95266.6798
#Mann= 3 , 0 , 0
9799.079    0.12       09799.079    0.12       010200.95    0.12       0
#XS Ineff= 2 , 0
       0                               0
Bank Sta=9799.079,10200.95
Exp/Cntr=0.3,0.1

Type RM Length L Ch R = 1 ,2447.673,49.952500,49.952500,49.952500
XS GIS Cut Line= 5
1157636.25053779850317.7002460681157743.48906504850399.258023022
 1157797.0228638850436.5873148631157798.65033078850437.749791204
1157962.58344572850552.315587569
#Sta/Elev= 30
9799.008249.35029814.295244.52739825.134240.24449836.321234.72549852.809225.8204
9881.662212.24749902.271203.35419927.002 197.5669935.201196.04739983.197191.8593
10003.21189.163910007.22189.585410011.22191.900810039.24216.674710051.24222.5153
10071.04233.825210083.27240.019410087.27240.895110091.27241.280210103.28 241.188
10119.29242.8014 10131.3242.8996 10135.3 243.81410143.31247.275410155.31253.7109
10159.32255.039410162.68255.212910167.32254.592810171.32255.6188   10201273.9987
#Mann= 3 , 0 , 0
9799.008    0.12       09799.008    0.12       0   10201    0.12       0
#XS Ineff= 2 , 0
       0                               0
Bank Sta=9799.008,10201
Exp/Cntr=0.3,0.1

Type RM Length L Ch R = 1 ,2397.721,49.952500,49.952500,49.952500
XS GIS Cut Line= 6
1157616.19411188850344.0174883671157716.11686116850425.231518761
1157787.05672248850496.9218998191157814.97744933850522.070164034
1157855.12506333850552.4505453141157924.98144978850599.763546963
#Sta/Elev= 30
9799.029253.29039829.195244.07539839.598239.53849863.147226.51159880.059 218.455
9891.616214.26019909.653208.90659931.008200.51599962.726192.21169976.894187.7077
10002.17185.578210010.22 186.605   10025190.668210034.53192.743910042.31195.9751
10066.25207.314710085.08217.1286 10089.2218.534810105.65220.782510117.95221.0938
10129.87220.383410135.72 221.68510145.68227.074710147.42228.501710161.53243.1017
 10165.5244.904110173.42 245.42810177.38247.194610185.31252.578610200.97264.8899
#Mann= 3 , 0 , 0
9799.029    0.12       09799.029    0.12       010200.97    0.12       0
#XS Ineff= 2 , 0
       0                               0
Bank Sta=9799.029,10200.97
Exp/Cntr=0.3,0.1

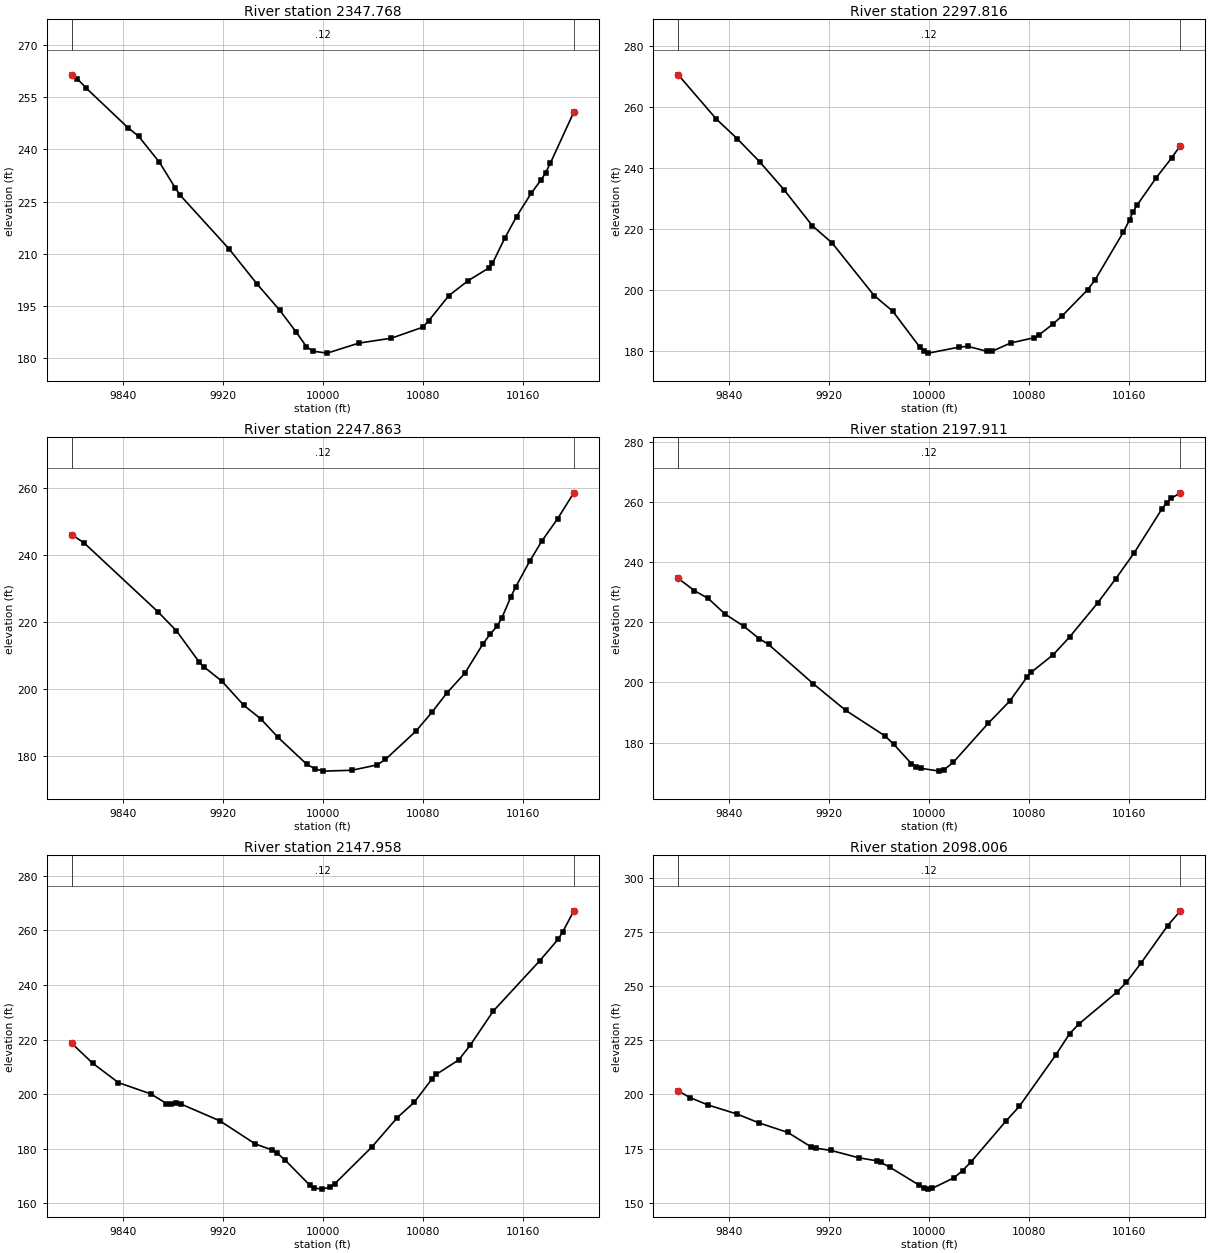
Type RM Length L Ch R = 1 ,2347.768,49.952500,49.952500,49.952500
XS GIS Cut Line= 6
 1157578.0339359850370.2102269261157686.97769713850459.113778282
1157742.54722895850525.2313395211157763.19542897850545.236114226
1157803.47928249850574.2803201751157885.34961303850625.108425086
#Sta/Elev= 30
9799.035261.45279803.353260.33769810.726257.58459844.167246.19829852.527243.7872
9869.247236.28549881.787228.96789885.967226.77419924.837211.43339947.283201.3281
9965.509193.74549978.631187.50559986.925183.24369992.278181.967510003.49181.4219
10028.82184.3025 10054.9185.721410079.97188.877410084.67190.695810100.85197.9549
10116.46202.296210133.27205.985810135.77207.219610145.71214.536110155.08220.7114
10166.67227.332410174.39231.083810178.25233.236810182.11236.032710200.93250.7623
#Mann= 3 , 0 , 0
9799.035    0.12       09799.035    0.12       010200.93    0.12       0
#XS Ineff= 2 , 0
       0                               0
Bank Sta=9799.035,10200.93
Exp/Cntr=0.3,0.1

Type RM Length L Ch R = 1 ,2297.816,49.952600,49.952600,49.952600
XS GIS Cut Line= 6
 1157521.2989122850436.9911626741157571.99346501850473.910372151
1157628.66298133850509.3049698061157669.12092247850530.656422851
1157742.34462929850564.121519744 1157869.7585115850635.510745304
#Sta/Elev= 30
9799.061270.46949829.494256.00159846.213249.54649864.243241.95969883.584232.8734
9906.413220.98699922.266 215.3349955.912198.08979970.751192.98479992.276181.2907
 9995.84179.91899999.386179.229610023.47181.168110030.81 181.45910046.54179.7929
10050.21179.813210065.13182.549810083.94184.2725 10087.7185.136610098.98 188.753
 10106.5191.498210126.82200.017710132.83203.300610155.39218.919310160.38222.9624
10162.91225.439810166.67227.933310181.71236.733410193.94243.175310200.97247.2559
#Mann= 3 , 0 , 0
9799.061    0.12       09799.061    0.12       010200.97    0.12       0
#XS Ineff= 2 , 0
       0                               0
Bank Sta=9799.061,10200.97
Exp/Cntr=0.3,0.1

Type RM Length L Ch R = 1 ,2247.863,49.952500,49.952500,49.952500
XS GIS Cut Line= 6
1157503.47993323 850512.693829311157552.95620853850546.738294568
1157600.23921699850570.6609721731157651.14302189850586.443099813
1157744.67544198850599.1623470971157870.96140788850660.650168943
#Sta/Elev= 30
9799.116246.15659809.156243.61419868.147 223.0359882.855217.37369901.239207.9451
9904.916206.56199919.244202.29569936.695195.10829950.329191.02369964.297185.4407
 9987.07177.45829993.635176.0956 10000.2 175.37310023.21 175.62710043.39177.2265
10050.15178.879510074.33187.267610087.69193.140510099.25198.761810113.71204.6927
10128.24213.492110133.86216.350810139.43 218.71410143.16221.138510150.61227.6095
10154.34230.501210165.53238.173610175.28244.2445 10187.9250.9028 10200.9258.6679
#Mann= 3 , 0 , 0
9799.116    0.12       09799.116    0.12       0 10200.9    0.12       0
#XS Ineff= 2 , 0
       0                               0
Bank Sta=9799.116,10200.9
Exp/Cntr=0.3,0.1

Type RM Length L Ch R = 1 ,2197.911,49.952500,49.952500,49.952500
XS GIS Cut Line= 6
1157497.90691624850545.6679647871157577.27463514850597.275474438
1157657.75189178   850628.0388991157696.39439228850648.441450619
1157790.29954784850682.1610138781157859.28721816850716.957318353
#Sta/Elev= 30
9799.097234.59229811.991230.5226 9823.03227.93559836.712222.67679851.699218.6538
9863.795214.57619871.356212.6453 9907.16199.56689933.042190.73559964.427182.2508
9971.401179.52439985.696173.01069989.414171.97639993.132171.457310008.05170.5035
10011.74170.925110019.11 173.37410047.12186.376710064.44 193.804 10078.3201.8041
10081.76203.4185 10099.3209.246110112.27215.077210134.85 226.46110149.34 234.518
10163.92243.021910186.28257.711310190.01259.746710193.74 261.22810200.93263.0387
#Mann= 3 , 0 , 0
9799.097    0.12       09799.097    0.12       010200.93    0.12       0
#XS Ineff= 2 , 0
       0                               0
Bank Sta=9799.097,10200.93
Exp/Cntr=0.3,0.1

Type RM Length L Ch R = 1 ,2147.958,49.952500,49.952500,49.952500
XS GIS Cut Line= 6
 1157487.5723107850591.231827168 1157542.1010218  850639.4232287
1157589.31631394850668.1412078161157625.75249557850679.725448534
1157733.88733559850698.7836384931157847.60865311850750.958022421
#Sta/Elev= 30
9799.086218.60449815.761211.34079836.462204.21579862.344200.08939874.865196.5803
9878.838 196.318 9882.81196.72089886.783196.32499917.499190.25459946.032181.7598
9959.608179.54659963.002178.58589969.682175.93079989.528166.71619992.835165.6917
9999.448165.241910006.05165.986110009.35167.111610039.34 180.71210059.63191.4478
10073.16 197.03110087.14205.424710090.66207.204210108.75212.526710117.81217.8252
10136.42230.422410173.53248.792610188.38256.725310192.09259.492910200.88 267.099
#Mann= 3 , 0 , 0
9799.086    0.12       09799.086    0.12       010200.88    0.12       0
#XS Ineff= 2 , 0
       0                               0
Bank Sta=9799.086,10200.88
Exp/Cntr=0.3,0.1

Type RM Length L Ch R = 1 ,2098.006,49.952500,49.952500,49.952500
XS GIS Cut Line= 6
1157495.38440927850621.7664574511157554.09489565850682.333310025
1157588.78052334850709.0085975191157734.25963233850760.856586362
1157785.26348544850787.7040372731157836.49033323850821.398283193
#Sta/Elev= 30
9799.113201.51959808.487198.54889822.628195.15879846.197190.92199863.727186.8381
9886.887182.41569905.359175.7812 9909.36175.13989921.362174.13839943.675170.7254
9957.969169.3374 9961.39168.58169968.231166.45199992.175158.02079995.596156.9176
9999.017156.269510002.53156.663610019.74161.495410026.63164.816510033.51168.8806
10061.45187.721210072.03194.425110101.31218.219510112.29 227.97410119.71232.4494
10149.95 247.067 10157.8251.704610169.58260.678110190.73277.812210200.92284.7104
#Mann= 3 , 0 , 0
9799.113    0.12       09799.113    0.12       010200.92    0.12       0
#XS Ineff= 2 , 0
       0                               0
Bank Sta=9799.113,10200.92
Exp/Cntr=0.3,0.1

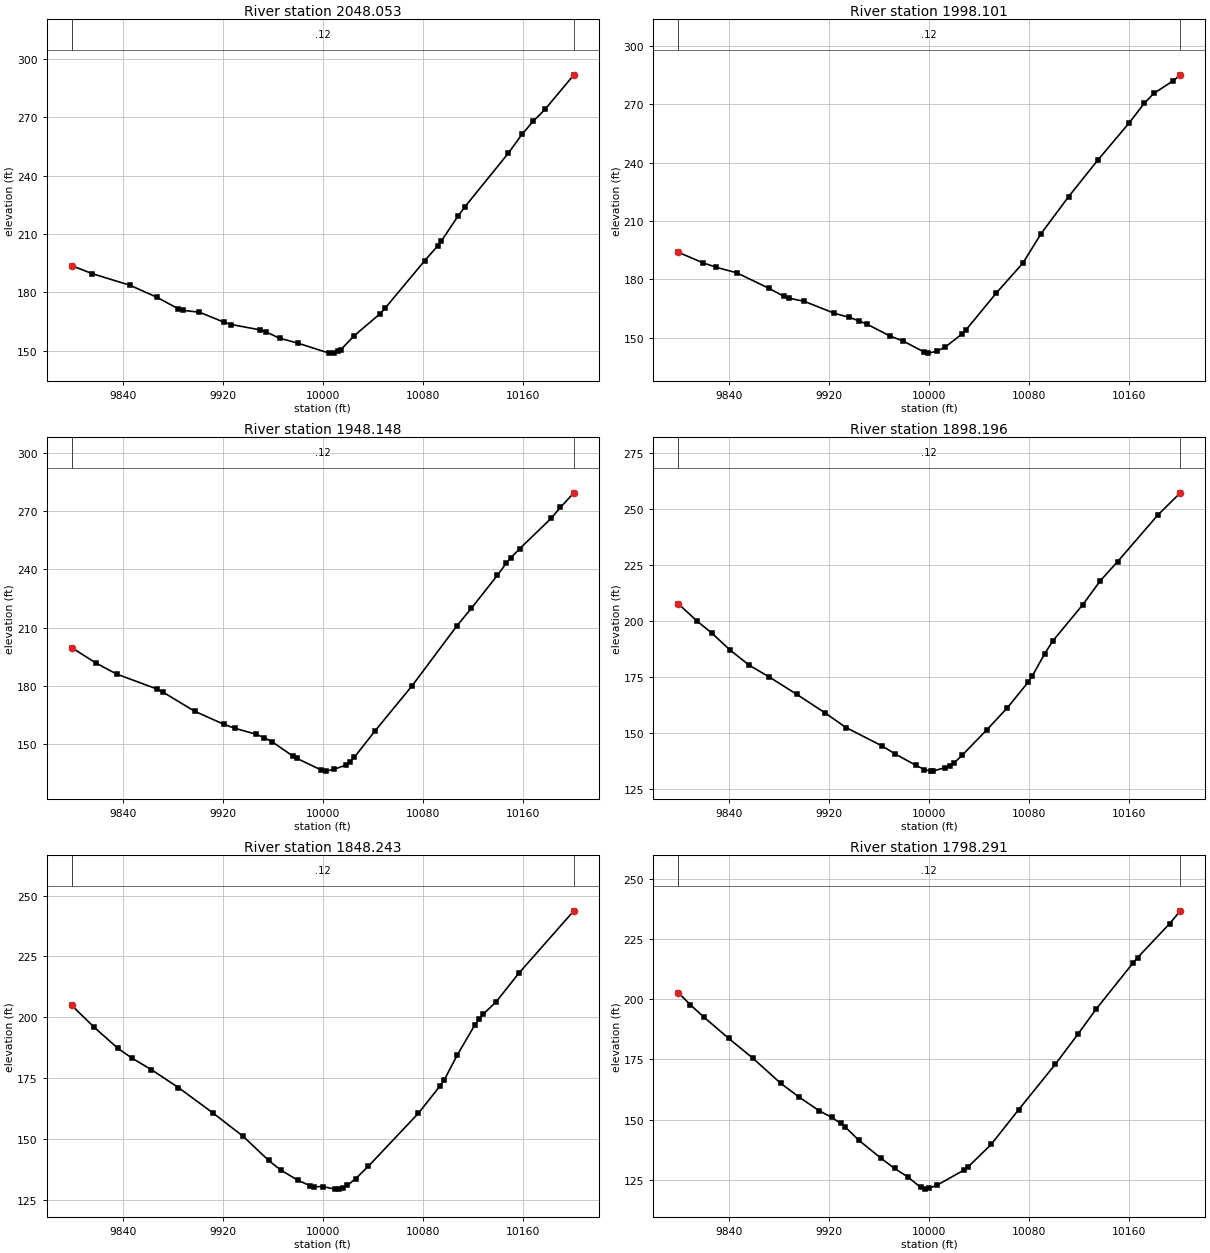
Type RM Length L Ch R = 1 ,2048.053,49.952500,49.952500,49.952500
XS GIS Cut Line= 6
1157502.29386373850639.1820570451157611.37969862850764.832288919
1157664.38676164850790.3575168351157693.20469869 850808.40037436
1157742.15380964850846.5304343081157801.86211933850899.961570127
#Sta/Elev= 30
 9799.11193.67469815.532189.53929845.523183.62769866.946177.49469884.084171.5541
9888.369170.64099901.222169.7129 9920.94 164.5759926.929163.35569949.748160.6383
9954.423159.57039965.581156.31429979.888153.814610005.07 148.64910008.63148.8536
10012.19149.547710014.22150.281510024.74157.380310045.94168.980610049.81171.7397
10081.45196.152310092.13203.986610094.89206.360510108.15219.109210113.49223.7702
 10148.5251.581610159.41261.261810168.22267.907210178.02 274.23910200.91291.9021
#Mann= 3 , 0 , 0
 9799.11    0.12       0 9799.11    0.12       010200.91    0.12       0
#XS Ineff= 2 , 0
       0                               0
Bank Sta=9799.11,10200.91
Exp/Cntr=0.3,0.1

Type RM Length L Ch R = 1 ,1998.101,49.952500,49.952500,49.952500
XS GIS Cut Line= 6
1157499.46319054850638.1663539421157558.59932108850712.349506522
1157589.39534927850759.156034314 1157624.2990636850875.120617511
 1157652.8799712850931.949052165 1157687.3072679 850988.04634405
#Sta/Elev= 30
9799.085193.90989818.798 188.5159829.052186.26989845.835183.35469871.431175.4489
9883.596171.26839887.792 170.2859900.092 168.6259924.144162.46849935.751160.4652
9943.391158.6905 9950.02156.92689968.725150.76449979.063148.22659995.797142.5873
9999.147141.9941 10005.9142.925810012.62145.051910026.06151.792210029.42153.9898
10053.79173.038610074.86188.293210089.55203.562310111.58222.613710134.98241.4426
10160.09260.599910172.04270.588210179.74275.739710195.14282.151710200.92285.2721
#Mann= 3 , 0 , 0
9799.085    0.12       09799.085    0.12       010200.92    0.12       0
#XS Ineff= 2 , 0
       0                               0
Bank Sta=9799.085,10200.92
Exp/Cntr=0.3,0.1

Type RM Length L Ch R = 1 ,1948.148,49.952600,49.952600,49.952600
XS GIS Cut Line= 6
1157480.09229438 850626.353549091157522.91055224850685.194997121
1157546.99549611850734.9158289911157560.78015525850888.947794797
1157577.38688844850943.2202899361157602.71172336850999.551779469
#Sta/Elev= 30
9799.118199.68449818.676191.74649835.132186.1019 9867.21178.4803 9871.92176.9158
9897.466167.00889920.664160.34249929.465 158.298 9946.19155.24389952.879153.4653
9959.548151.28539975.956144.00129979.237142.78359998.926136.720710002.21136.2096
10008.77137.070110018.61139.3725 10021.9141.051810025.18143.295310041.63 156.764
10071.43180.082110107.11210.7698 10118.9219.993910139.73 236.92810146.92243.2688
10150.52 245.96910157.72250.7303 10182.9266.351110190.09271.841410200.91279.3812
#Mann= 3 , 0 , 0
9799.118    0.12       09799.118    0.12       010200.91    0.12       0
#XS Ineff= 2 , 0
       0                               0
Bank Sta=9799.118,10200.91
Exp/Cntr=0.3,0.1

Type RM Length L Ch R = 1 ,1898.196,49.952500,49.952500,49.952500
XS GIS Cut Line= 6
1157450.73169033850617.3140459351157489.65892201850678.739963794
1157506.14511125850723.9246161061157509.92065038850765.775484018
 1157500.4319904850868.8225943961157541.69004375850996.549151088
#Sta/Elev= 30
9799.094207.62069814.243199.84469825.902194.55719840.763186.89479856.021180.1612
9871.884174.98079893.952167.22189916.654158.92929933.371152.42519962.178144.2166
 9972.88140.5799 9989.47135.51879996.184133.6584   10001132.9825 10002.9133.0228
 10012.9134.579910016.23135.295410019.57136.477510026.23140.007610045.93151.3293
10062.37161.143610078.98172.543510082.31175.256510092.31185.286210099.05191.1427
10122.89207.218510136.82217.826110150.77226.421510182.72247.048910200.92257.0745
#Mann= 3 , 0 , 0
9799.094    0.12       09799.094    0.12       010200.92    0.12       0
#XS Ineff= 2 , 0
       0                               0
Bank Sta=9799.094,10200.92
Exp/Cntr=0.3,0.1

Type RM Length L Ch R = 1 ,1848.243,49.952500,49.952500,49.952500
XS GIS Cut Line= 6
1157385.20561457850613.5027181371157416.13676368850664.983859204
1157436.93787984850713.7152665251157447.72230809  850754.5817185
1157469.16959433 850877.945727961157513.14793206850990.834860855
#Sta/Elev= 30
9799.078204.89639816.913195.9382 9836.05187.21879847.309183.18829862.657178.5331
9884.435171.12119912.161160.63799936.303151.04349956.616141.17219966.588137.1153
9979.883133.07179989.855130.73949993.179130.34499999.825130.427510009.78129.3644
10013.09129.382610016.41129.922610019.73130.909910026.36133.677110036.31 138.684
10076.53160.540810093.75171.709810097.21174.2478 10107.6184.449810121.45196.6281
10124.91199.160910128.37201.251810138.94206.467710156.81218.054210200.95243.7662
#Mann= 3 , 0 , 0
9799.078    0.12       09799.078    0.12       010200.95    0.12       0
#XS Ineff= 2 , 0
       0                               0
Bank Sta=9799.078,10200.95
Exp/Cntr=0.3,0.1

Type RM Length L Ch R = 1 ,1798.291,49.952500,49.952500,49.952500
XS GIS Cut Line= 6
1157317.21453162850633.8381622811157350.19020366850686.698461553
1157378.28480135  850739.66127631157401.21376151850791.902423741
1157416.51847661850839.7061975581157492.93965938850994.143842601
#Sta/Elev= 30
9799.072202.82759808.591197.81969819.496192.64589839.526183.7302 9858.86175.4955
9881.243165.02579896.098159.25449912.091153.62379922.068150.88039929.234148.3968
9932.817146.88469943.566141.4374 9961.48133.88829972.229129.67469982.772126.2012
9993.039121.83929996.462121.0869 9999.86121.4077 10006.6122.821610027.65128.9689
10031.27130.400110049.58139.685310071.54154.104810100.82172.943310119.13185.6092
10133.77196.063310163.05 215.07510166.71217.317110192.34231.429210200.97236.7986
#Mann= 3 , 0 , 0
9799.072    0.12       09799.072    0.12       010200.97    0.12       0
#XS Ineff= 2 , 0
       0                               0
Bank Sta=9799.072,10200.97
Exp/Cntr=0.3,0.1

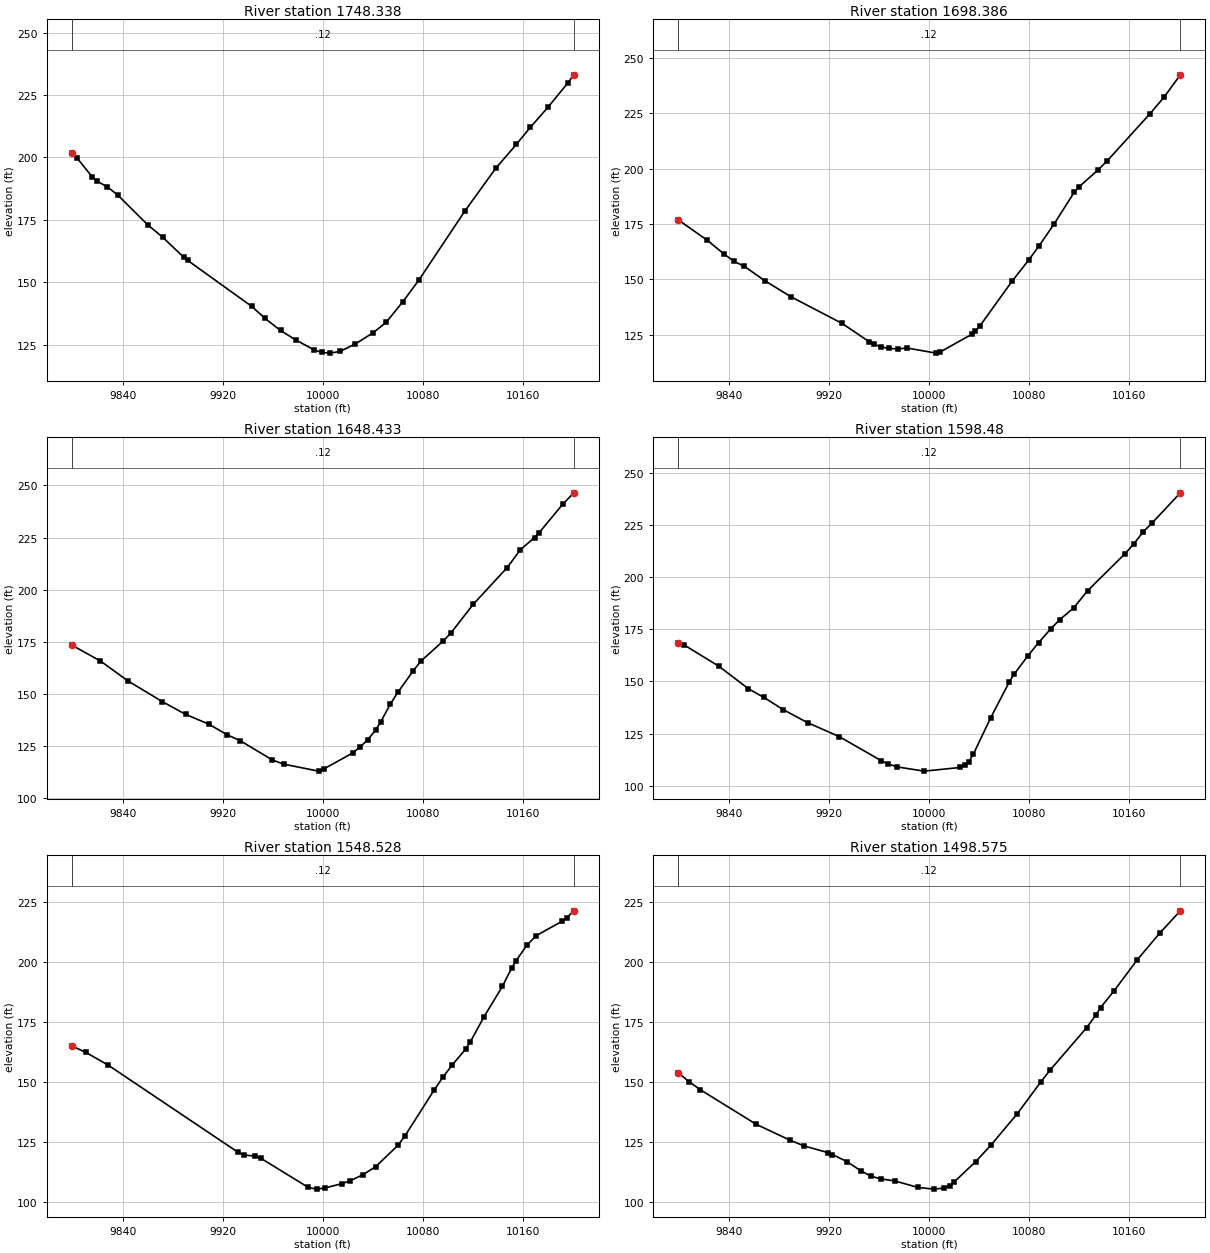
Type RM Length L Ch R = 1 ,1748.338,49.952500,49.952500,49.952500
XS GIS Cut Line= 6
 1157246.7188445850674.3305945211157355.85997491 850823.07572421
1157370.41979072850847.1013105561157424.60010673850906.418336764
1157448.91439799850944.7933189911157478.92121107851000.641905952
#Sta/Elev= 30
9799.027201.66449803.522199.60089815.567192.05889819.582190.39969827.612188.1431
9835.642185.00399859.732173.03069871.777168.01369888.853159.88679891.852158.7036
9943.186140.25339953.718135.46639966.119130.64049978.519126.79219993.092 122.839
    9999 121.87110005.71121.562810013.77122.245210026.06125.276810040.09129.6767
10050.58133.859310064.03142.143910076.73150.749110113.92 178.68310138.56195.7351
10154.94205.244210166.11212.062110180.15 220.07610195.91229.7229 10200.9233.0894
#Mann= 3 , 0 , 0
9799.027    0.12       09799.027    0.12       0 10200.9    0.12       0
#XS Ineff= 2 , 0
       0                               0
Bank Sta=9799.027,10200.9
Exp/Cntr=0.3,0.1

Type RM Length L Ch R = 1 ,1698.386,49.952500,49.952500,49.952500
XS GIS Cut Line= 6
1157202.43823704850747.3051940841157297.12637321850859.303208569
1157327.65140154850877.5704515451157373.44919907850885.144163829
1157403.35658466850907.457771118 1157475.6432197851020.751781042
#Sta/Elev= 30
9799.117 176.8539822.391167.6062 9835.63161.47449843.856158.08569852.083155.8259
9868.536149.28539889.466142.04849930.212130.04839951.842121.80849955.857120.5637
9961.749119.39159967.684118.72959974.971118.52519982.226118.925710005.45116.6233
10008.74117.133610034.12125.198410036.86126.454110040.68129.051810066.08149.0299
10079.39158.586310087.99165.211810100.07175.177510115.98189.333310119.76191.7414
10134.86 199.34410142.42 203.56310176.41224.711910187.74232.221410200.84242.3962
#Mann= 3 , 0 , 0
9799.117    0.12       09799.117    0.12       010200.84    0.12       0
#XS Ineff= 2 , 0
       0                               0
Bank Sta=9799.117,10200.84
Exp/Cntr=0.3,0.1

Type RM Length L Ch R = 1 ,1648.433,49.952500,49.952500,49.952500
XS GIS Cut Line= 6
1157192.91247057850755.8071784791157251.40421772850834.353137628
1157308.21519768850899.4171450031157325.86195661850931.353494817
1157379.18789056851014.1146983681157419.99871563 851085.96701163
#Sta/Elev= 30
9799.084173.37779822.058165.7276 9844.03156.19219871.496146.26989890.245140.1146
9908.759 135.4289923.723 130.258  9933.7127.56339959.494118.29999968.617116.2389
9996.659112.8876   10001113.994710023.88121.559110029.94124.483710035.99127.9858
10042.44132.724610046.34136.489710054.16145.158410060.22150.789210072.34160.9712
10078.39165.601910096.57175.426710102.62179.219510120.43192.9436 10147.6210.5601
10158.16219.125410169.48224.987610173.25227.361510192.11241.000310200.97246.4436
#Mann= 3 , 0 , 0
9799.084    0.12       09799.084    0.12       010200.97    0.12       0
#XS Ineff= 2 , 0
       0                               0
Bank Sta=9799.084,10200.97
Exp/Cntr=0.3,0.1

Type RM Length L Ch R = 1 , 1598.48,49.952600,49.952600,49.952600
XS GIS Cut Line= 6
1157171.31874153850769.4324181091157226.06949672850849.708252554
1157251.69411394850891.3272054861157268.79320688850925.607264826
 1157304.5730783851006.8401104781157363.88683883851121.202196596
#Sta/Elev= 30
9799.026168.52959803.523167.54559831.322157.3742 9855.15146.53289867.525142.3751
9882.948136.54319902.608130.25289927.959123.58869961.723 111.9979966.991110.5135
9974.323 109.0799995.948107.062810024.62108.803810028.21109.8728 10031.8111.6586
10035.39115.299510049.19132.621910064.14149.827910067.73153.324410078.69162.0446
10087.45  168.5410097.17175.117710104.56179.649410115.65185.228810126.74193.4242
 10156.3210.900710163.69215.759410171.09221.537610178.48225.904310200.98240.2971
#Mann= 3 , 0 , 0
9799.026    0.12       09799.026    0.12       010200.98    0.12       0
#XS Ineff= 2 , 0
       0                               0
Bank Sta=9799.026,10200.98
Exp/Cntr=0.3,0.1

Type RM Length L Ch R = 1 ,1548.528,49.952500,49.952500,49.952500
XS GIS Cut Line= 6
1157134.93014086850771.5811997831157211.07420982850897.281225378
1157221.92819988850925.7364308731157230.11606202850968.253126746
 1157239.3121075850995.989875833 1157305.3505208851132.685160855
#Sta/Elev= 30
9799.078165.05489810.403162.35539828.169157.06929931.769120.79929936.865119.5272
9946.116119.00879950.203 118.2299988.272106.01919994.977 105.27410001.64105.7437
10014.99107.521810021.74108.733410032.11111.274310042.47114.709210060.19123.5665
10065.47 127.26410088.95146.496610096.14151.969910103.46157.041410114.46163.7915
10118.13166.773710129.13177.3106 10143.8189.943910151.13197.5442 10154.8200.7024
10163.59207.265710170.94211.146710191.47217.086410195.14218.441210200.96221.4752
#Mann= 3 , 0 , 0
9799.078    0.12       09799.078    0.12       010200.96    0.12       0
#XS Ineff= 2 , 0
       0                               0
Bank Sta=9799.078,10200.96
Exp/Cntr=0.3,0.1

Type RM Length L Ch R = 1 ,1498.575,49.952500,49.952500,49.952500
XS GIS Cut Line= 6
1157076.14921933850804.8616920051157148.12915542850925.698860892
1157166.38756361850951.5490988671157197.04922044850989.228933705
1157211.33350657851010.5492282961157283.03487154   851148.405942
#Sta/Elev= 30
9799.024153.88189807.935150.10249816.794146.80099861.399132.4243 9888.13125.8771
9899.586123.4157 9918.68120.60759922.499119.78879933.956116.88179945.709112.8347
9953.743110.66899961.469109.62899972.708108.74519990.912106.073410003.63105.3631
10012.06 105.84310016.27106.865110019.49108.153710037.12116.808810049.41123.7477
10070.46136.825710089.21150.038210096.65154.968110126.06172.761510133.41178.0478
10137.09181.089410147.98188.1084 10166.5201.052710184.34212.068910200.98221.4793
#Mann= 3 , 0 , 0
9799.024    0.12       09799.024    0.12       010200.98    0.12       0
#XS Ineff= 2 , 0
       0                               0
Bank Sta=9799.024,10200.98
Exp/Cntr=0.3,0.1

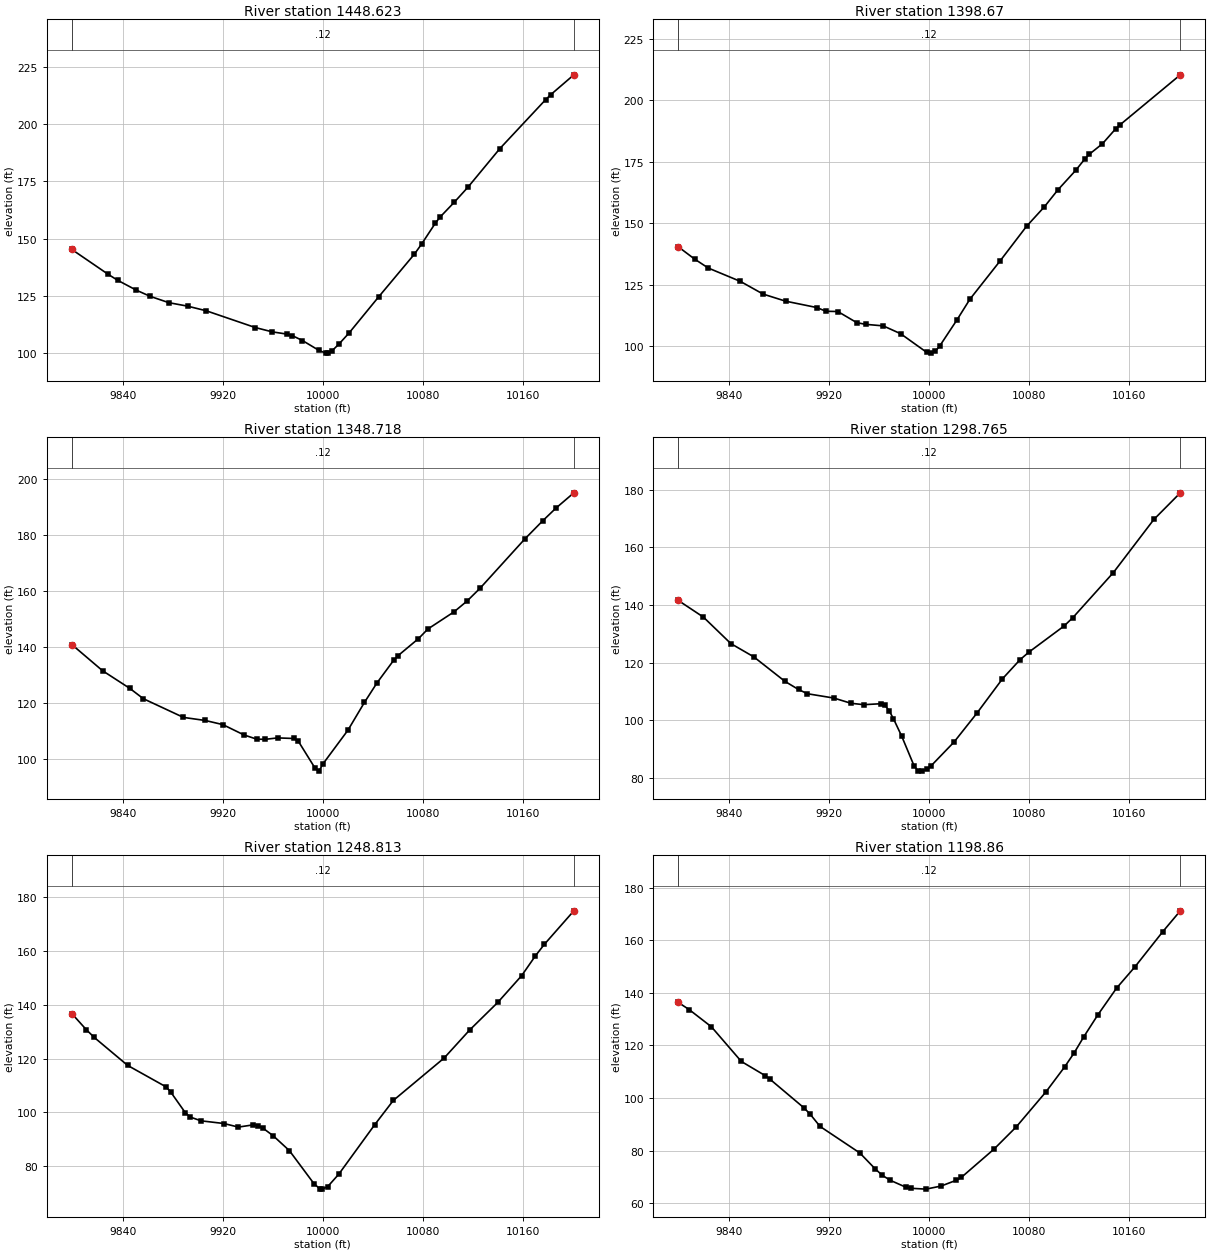
Type RM Length L Ch R = 1 ,1448.623,49.952500,49.952500,49.952500
XS GIS Cut Line= 6
1157044.71592183850832.7365763821157114.25128996850961.162067671
1157131.50408184850986.9839335951157163.59774083851028.588311492
1157183.48294447851060.1505373531157244.27872616851180.663204298
#Sta/Elev= 30
9799.029145.23619828.269134.30959835.731131.75259850.654127.42759861.847124.6998
9876.771121.93439891.694120.42879906.618118.40579946.006111.05069959.643109.1596
9971.481108.17779975.426107.56269983.716105.37979996.904101.0721 10002.299.87013
10004.5399.9326910007.62100.998910013.04103.909210021.02 108.67810044.73 124.499
10073.36143.196410079.06147.558710090.21156.816910093.92159.410510105.07165.7722
10116.19172.454910141.76189.353210178.29210.689710182.51212.946310200.97221.6089
#Mann= 3 , 0 , 0
9799.029    0.12       09799.029    0.12       010200.97    0.12       0
#XS Ineff= 2 , 0
       0                               0
Bank Sta=9799.029,10200.97
Exp/Cntr=0.3,0.1

Type RM Length L Ch R = 1 , 1398.67,49.952500,49.952500,49.952500
XS GIS Cut Line= 6
1157024.42812342 850846.788214921157052.91236335850903.881722374
1157076.26003571850956.2312726481157093.95470767851001.294930289
1157127.81201762851099.7463667791157178.68446295851217.521633878
#Sta/Elev= 30
9799.017140.49179812.049135.51539823.048131.84699848.714126.43049866.961121.2592
9884.922118.38689910.069115.77779917.254 114.2719926.767114.18049941.981109.6432
 9949.03108.96679963.129108.34379977.061105.15789997.80197.6273410001.2597.26687
10004.7297.97496 10008.2100.0568 10022.1110.725810032.53119.184710056.86134.8465
10077.86148.805710092.16156.742310102.88163.567610117.17171.512410124.32176.0418
10127.89177.999910138.62182.349710149.34188.497210152.91190.134210200.96210.3613
#Mann= 3 , 0 , 0
9799.017    0.12       09799.017    0.12       010200.96    0.12       0
#XS Ineff= 2 , 0
       0                               0
Bank Sta=9799.017,10200.96
Exp/Cntr=0.3,0.1

Type RM Length L Ch R = 1 ,1348.718,49.952500,49.952500,49.952500
XS GIS Cut Line= 6
1156991.63623873850849.3099377891157022.99016424850915.532932753
1157039.69878715850960.2340238191157049.06938399850997.498060351
1157067.58852868851110.1686847411157114.84087756851229.231021386
#Sta/Elev= 30
9799.065140.88639823.697131.55669845.477125.27659856.367121.5852 9888.45 114.928
9905.963113.82789919.973 112.3659936.891108.6871 9947.04  107.199953.806107.1128
9963.838107.62729977.081 107.4199980.392106.45659993.63496.974099996.94595.79672
10000.2598.4508610020.11 110.36910033.34 120.27410043.42127.247210056.88135.3601
10060.24136.917210076.55142.966910084.16146.418110105.01152.506610115.44156.3468
10125.87160.913210161.57178.399410175.87184.8652 10186.6189.449310200.95194.9003
#Mann= 3 , 0 , 0
9799.065    0.12       09799.065    0.12       010200.95    0.12       0
#XS Ineff= 2 , 0
       0                               0
Bank Sta=9799.065,10200.95
Exp/Cntr=0.3,0.1

Type RM Length L Ch R = 1 ,1298.765,49.952500,49.952500,49.952500
XS GIS Cut Line= 6
1156936.71077639850853.475726844 1156987.2817508850963.342625659
1157000.30063781851006.8833757961157006.86662851851060.821778059
1157014.57948391851089.9234261281157073.60877122851228.781240713
#Sta/Elev= 30
9799.094141.58449819.265135.79269841.207126.62869859.492122.05289884.525113.5368
9895.355110.72439902.455109.25899923.625107.76399937.322105.95419947.595 105.465
9961.293105.79559964.717105.18549968.055103.25169971.365100.57989977.98594.51457
9987.91584.217519991.22582.444579994.53582.459739997.84583.0371310001.14 84.1308
10019.8992.5464910037.94102.409610058.61114.435610072.68121.052910079.71123.6591
10107.86132.705410114.95135.629710147.36151.226710179.77169.633310200.94178.8593
#Mann= 3 , 0 , 0
9799.094    0.12       09799.094    0.12       010200.94    0.12       0
#XS Ineff= 2 , 0
       0                               0
Bank Sta=9799.094,10200.94
Exp/Cntr=0.3,0.1

Type RM Length L Ch R = 1 ,1248.813,49.952500,49.952500,49.952500
XS GIS Cut Line= 6
1156853.29219193850894.264885256 1156927.3483108851020.300104465
1156948.28137891851048.162054928 1156975.8115383851076.879548883
1156988.16256819851094.6057412961157059.29376755851237.291890382
#Sta/Elev= 30
9799.042136.79999810.657130.80849817.059127.90069843.764117.50069874.697  109.47
9878.464 107.4489889.91599.910869893.77798.297539902.48596.875869920.80595.87937
9932.38894.541379943.97295.354519947.99595.111149952.09894.146229960.30691.30287
9973.25585.776789993.08773.380719997.81571.541279999.13571.4588110003.7672.31584
10012.7877.0207110041.4995.3921210056.45104.469610097.16120.263110117.48130.6394
10140.06140.945810159.14150.879710170.16158.248610177.36162.564710200.95175.0246
#Mann= 3 , 0 , 0
9799.042    0.12       09799.042    0.12       010200.95    0.12       0
#XS Ineff= 2 , 0
       0                               0
Bank Sta=9799.042,10200.95
Exp/Cntr=0.3,0.1

Type RM Length L Ch R = 1 , 1198.86,49.952600,49.952600,49.952600
XS GIS Cut Line= 6
 1156812.7153384850926.2917181361156843.85455474850979.963293635
1156867.38773921851016.8130995641156974.04567231851165.352083691
1156999.69932501 851209.161056971157028.78399234851264.510266318
#Sta/Elev= 30
9799.024136.3534 9807.83133.6054 9825.61127.06819849.553113.88929868.714108.4829
9872.607 107.0829899.85796.176489904.79893.729899912.57689.174059944.39379.08577
9956.94672.913539962.49370.550549968.80868.675979981.015 66.10679985.08465.65393
9997.29265.3248710009.4966.4986610021.6168.6945410025.6569.7762510051.9180.58266
10069.6989.0280110093.48102.366810108.43111.850510116.03117.186310123.64123.2356
10135.04131.674510149.95141.788210164.78149.956610187.01163.309610200.98 171.194
#Mann= 3 , 0 , 0
9799.024    0.12       09799.024    0.12       010200.98    0.12       0
#XS Ineff= 2 , 0
       0                               0
Bank Sta=9799.024,10200.98
Exp/Cntr=0.3,0.1

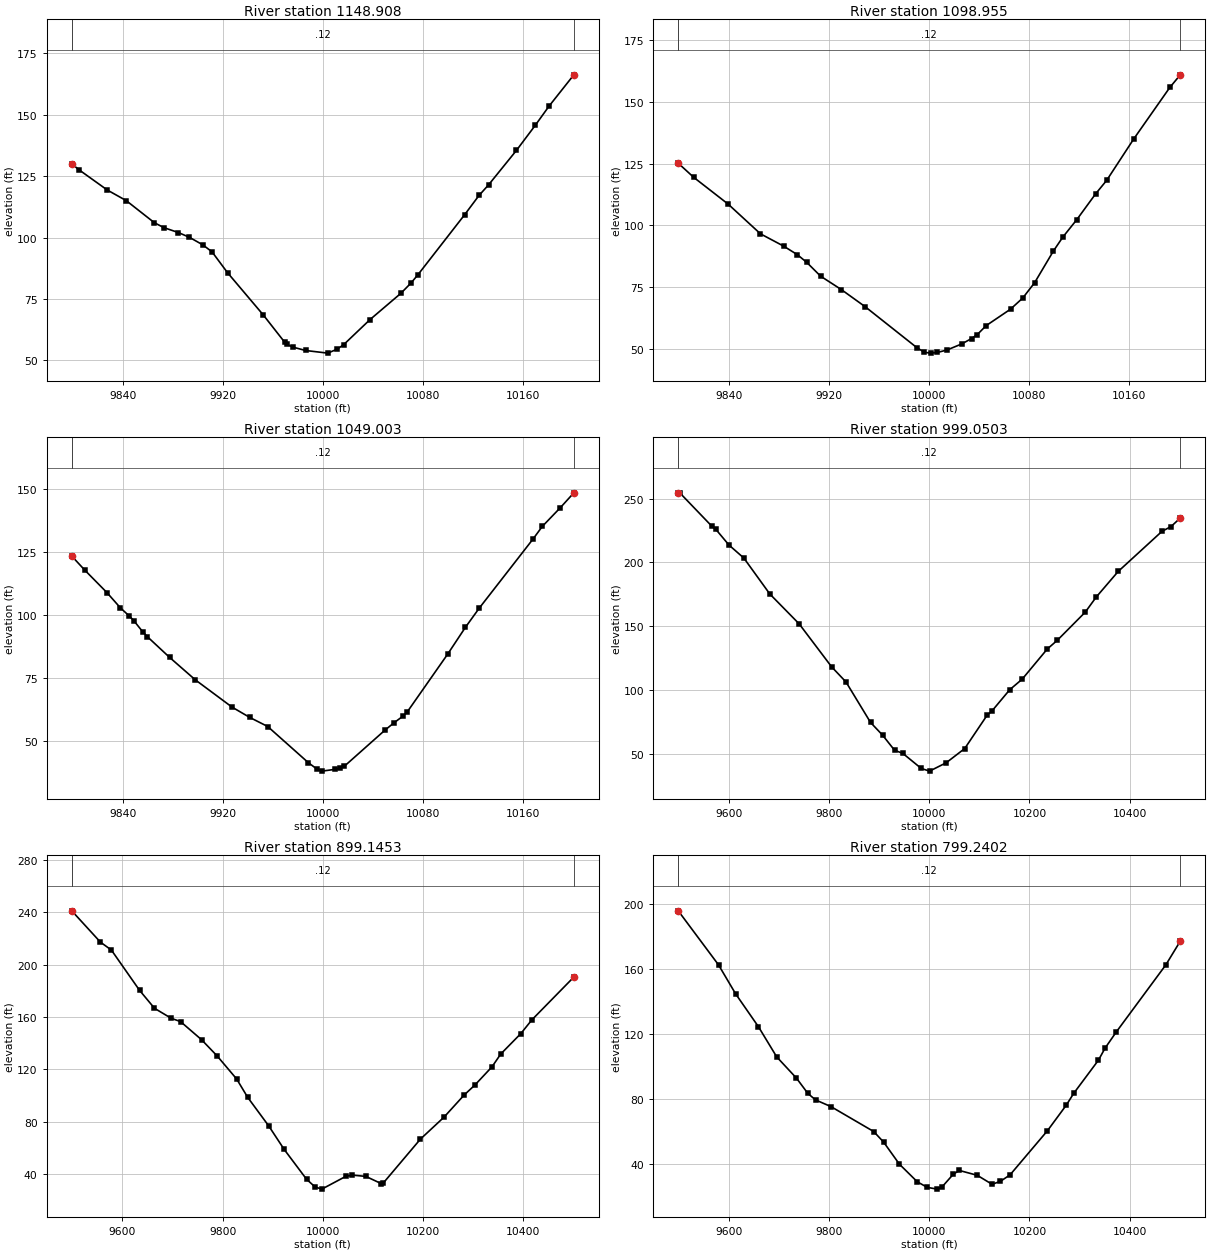
Type RM Length L Ch R = 1 ,1148.908,49.952500,49.952500,49.952500
XS GIS Cut Line= 6
1156775.35755996850961.6179130461156811.19850354851025.039155692
1156837.34141717851065.4882086421156911.76650742851156.734394786
1156936.53088221851190.7952300721156996.60957823851295.799361954
#Sta/Elev= 30
9799.028 130.0389804.884127.60149827.495119.37439842.569115.0957 9865.18106.0626
9872.748104.07219884.467102.04479893.205100.13089903.99997.035759911.33794.19558
9923.71285.724579952.472 68.42679969.453  57.4069971.10856.562159976.14555.39304
9986.21854.0304610003.9652.9590910011.6454.6109510016.7556.4320810037.8366.63492
 10062.577.3219910070.6281.5149610076.1984.9126710113.54109.327810125.12117.2163
10132.68121.478310155.06135.554310169.99145.669510181.18153.595610200.97166.3011
#Mann= 3 , 0 , 0
9799.028    0.12       09799.028    0.12       010200.97    0.12       0
#XS Ineff= 2 , 0
       0                               0
Bank Sta=9799.028,10200.97
Exp/Cntr=0.3,0.1

Type RM Length L Ch R = 1 ,1098.955,49.952500,49.952500,49.952500
XS GIS Cut Line= 6
1156748.15306586850983.8395202381156800.56328184851084.080739576
1156822.48572474851120.2422114251156890.86258997851224.881460925
1156920.09515698851277.4814336681156947.97210305851332.158390247
#Sta/Elev= 30
9799.019125.13149811.377119.42269838.932108.60459864.84796.576799883.35891.61843
9894.46588.12257 9901.8785.048429913.00779.457299929.66874.013529948.65467.12196
9990.27250.48077 9996.1648.67801   1000148.3492910006.5348.6179810014.3449.64353
10026.0452.0812510033.8454.2429810038.46 55.873210045.5459.4617810065.04 66.1168
10074.8670.6386510084.3576.8265410099.3689.6114410106.8795.2195110118.13102.3315
10133.14  112.7110142.04118.201110163.71134.9424 10192.6155.759710200.98160.8503
#Mann= 3 , 0 , 0
9799.019    0.12       09799.019    0.12       010200.98    0.12       0
#XS Ineff= 2 , 0
       0                               0
Bank Sta=9799.019,10200.98
Exp/Cntr=0.3,0.1

Type RM Length L Ch R = 1 ,1049.003,49.952500,49.952500,49.952500
XS GIS Cut Line= 5
1156724.49020861 850999.88047405 1156789.2546103851149.619435968
1156804.80257485851183.0188180981156805.65144266851184.829735946
1156888.07739745851367.047159674
#Sta/Elev= 30
9799.014123.32039809.351117.80949827.223108.83379837.947102.81729845.09699.56688
9848.67197.74918 9855.8293.333489859.39591.458329877.26783.218789897.83974.32643
9927.31163.494559941.609  59.3779955.90855.80132  9988.441.483299995.63838.81023
9999.25738.1231510010.0738.8435610013.6739.2341410017.2740.0672710049.6854.32208
10056.8857.2296310064.08  59.87410067.68  61.63710100.0984.5686510114.19 95.1133
 10125.3102.737710168.51130.216710175.71135.074810190.11142.475510200.99 148.396
#Mann= 3 , 0 , 0
9799.014    0.12       09799.014    0.12       010200.99    0.12       0
#XS Ineff= 2 , 0
       0                               0
Bank Sta=9799.014,10200.99
Exp/Cntr=0.3,0.1

Type RM Length L Ch R = 1 ,999.0503,99.905000,99.905000,99.905000
XS GIS Cut Line= 6
1156564.79104563850740.3957828751156716.19214842851039.599309047
1156745.46510537851127.422804582 1156766.7234899851253.151165178
1156791.14377448851335.3116786061156942.08494533851662.429011251
#Sta/Elev= 30
9499.052254.47649503.332253.97699566.562228.1044 9574.07225.84899600.349213.4934
9629.999203.31679681.815175.12459740.341151.69069805.204117.96229833.827106.1036
9882.81274.362769906.77264.42819 9930.6352.60228 9947.3850.051999984.04638.26794
10000.5936.1818110033.7742.7417610070.7253.8891910115.1679.8768710125.5483.57361
10160.56100.032110185.31108.273510235.31131.892410255.71138.892110311.32160.9001
10333.18172.7308 10376.9192.779210464.33224.249610482.55228.055610500.96234.7464
#Mann= 3 , 0 , 0
9499.052    0.12       09499.052    0.12       010500.96    0.12       0
#XS Ineff= 2 , 0
       0                10063.62       0
Bank Sta=9499.052,10500.96
Exp/Cntr=0.3,0.1

Type RM Length L Ch R = 1 ,899.1453,99.905100,99.905100,99.905100
XS GIS Cut Line= 6
1156453.35578601850743.7433904611156550.85211947850919.995259387
1156607.22549911851037.1400049461156638.37461192851121.432441848
1156696.33854965851332.1454282651156852.19393965851658.631464276
#Sta/Elev= 30
9499.034241.01639556.216217.11919578.103211.07039634.285180.34449664.098166.6182
9697.637158.94919716.029156.48149758.189 142.5749789.164130.22549828.117112.6167
9850.07698.643299891.93176.887519922.95858.851119967.46336.156959984.46530.24682
9998.06728.5700210045.3838.2175310058.8339.2788210085.8938.2790210117.0232.71335
10120.4833.1180710194.8366.7740910241.8483.5007810281.93100.360710303.87108.1736
10337.76122.010510355.06131.698310395.28147.345910417.23157.803710500.95190.4645
#Mann= 3 , 0 , 0
9499.034    0.12       09499.034    0.12       010500.95    0.12       0
#XS Ineff= 2 , 0
       0                 10078.1       0
Bank Sta=9499.034,10500.95
Exp/Cntr=0.3,0.1

Type RM Length L Ch R = 1 ,799.2402,99.905000,99.905000,99.905000
XS GIS Cut Line= 6
1156307.61768625850811.8353704181156478.18846358851102.977487534
 1156619.2300943851311.0796806661156653.61189751851366.363522109
1156724.55713407851496.9398845551156814.47831493851674.905738339
#Sta/Elev= 30
9499.009195.71899579.411162.48969613.531144.68379659.025124.47969695.566105.9034
9734.84892.889469757.80583.417799773.06679.468929803.76775.360349889.131 60.0212
9908.92653.508489940.36739.963079976.12629.115799995.99125.6952810015.9824.61929
 10025.1 25.841510048.0133.80854   1006036.0936310095.74 33.1189 10125.427.57705
 10142.129.4532410161.1433.3679310235.8160.5239710273.6676.3534110288.0983.43526
10337.49103.859110350.79111.283710372.84121.099410472.09162.500910500.97 177.112
#Mann= 3 , 0 , 0
9499.009    0.12       09499.009    0.12       010500.97    0.12       0
#XS Ineff= 2 , 0
       0                10075.71       0
Bank Sta=9499.009,10500.97
Exp/Cntr=0.3,0.1