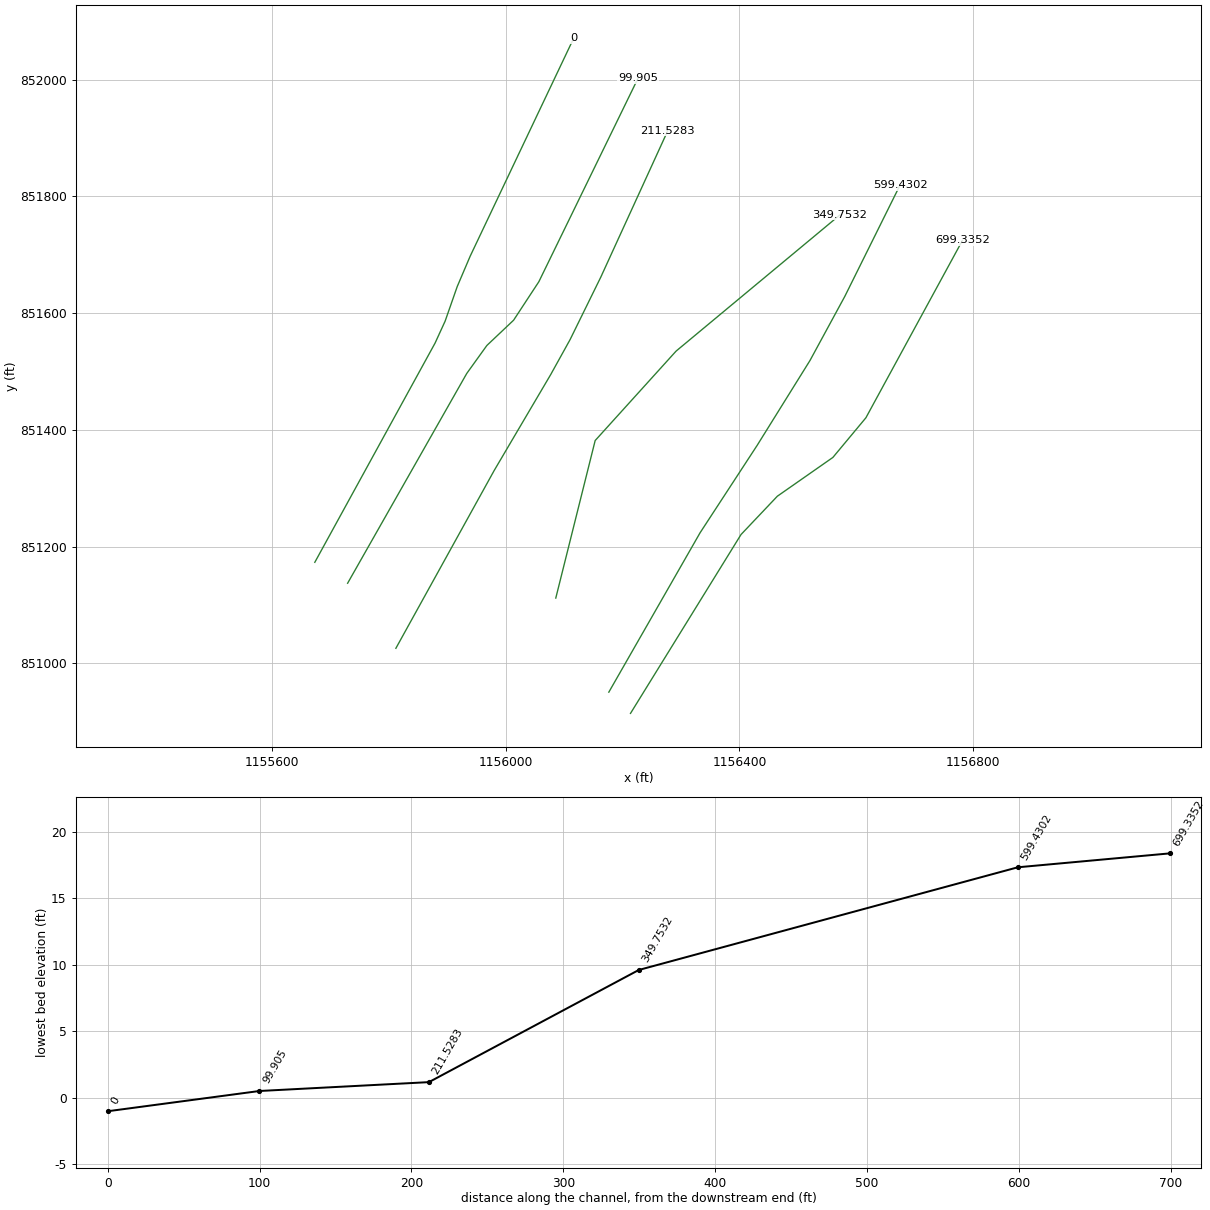
HEC-RAS study 177_ras.prj: 177

--- 177_ras.g01 (geometry) --- (continued)

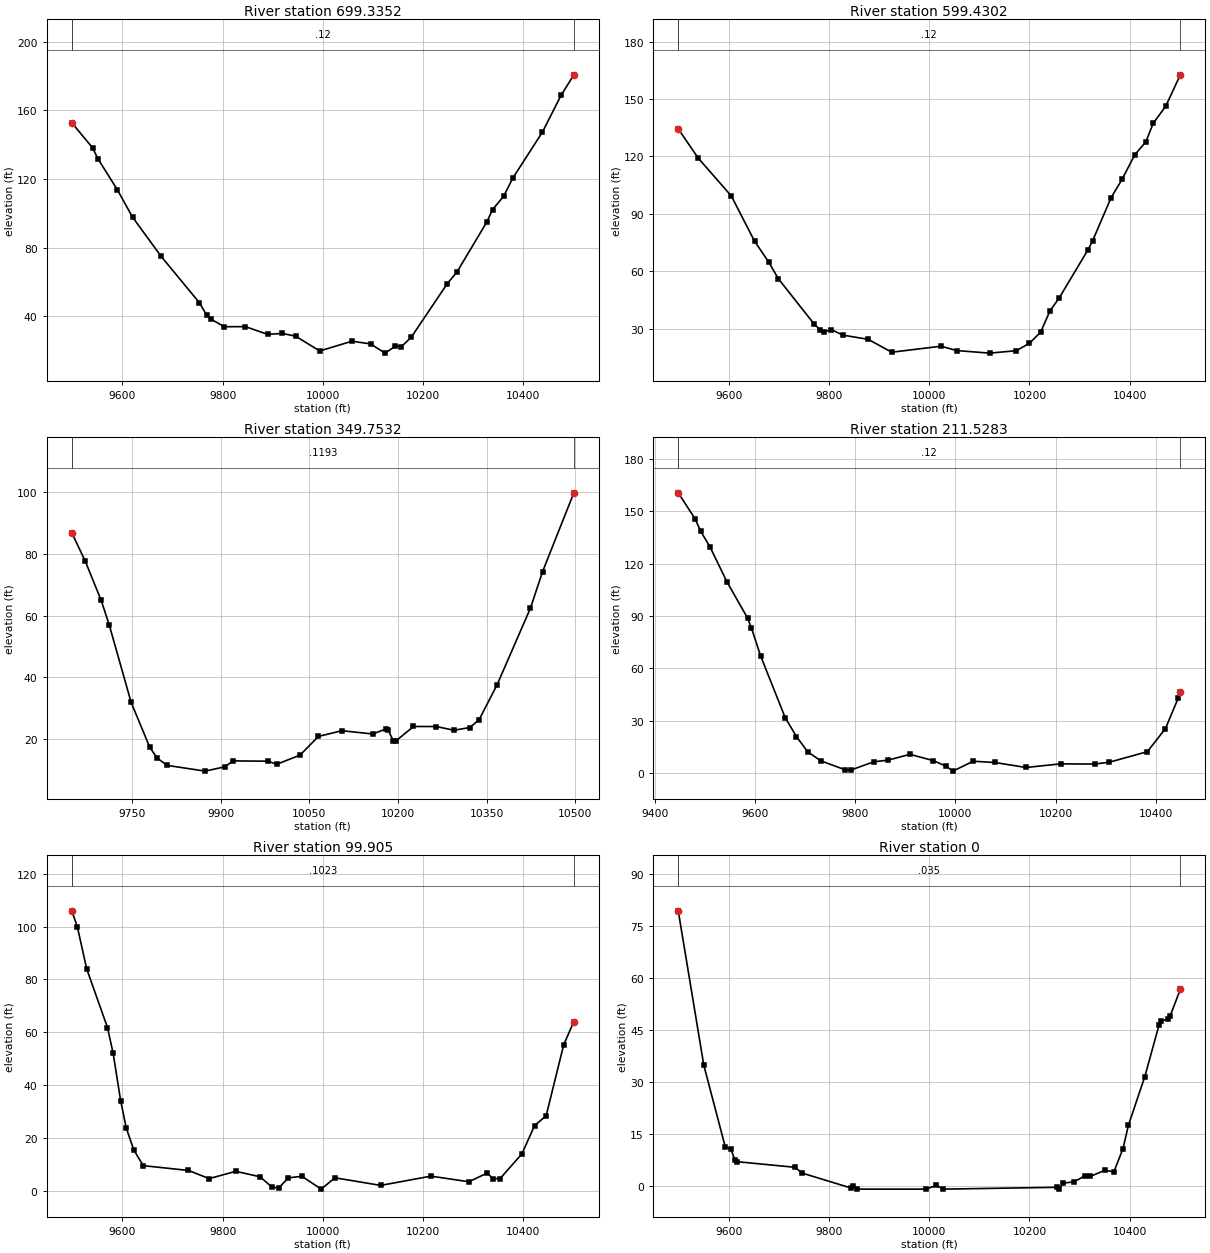
Type RM Length L Ch R = 1 ,699.3352,99.905000,99.905000,99.905000
XS GIS Cut Line= 6
 1156213.3963374850914.5473869861156402.70850456851220.904498992
1156464.91465189851286.4914834871156560.01238015851352.914960469
1156616.51509803851420.7559814791156781.96551629 851724.67641914
#Sta/Elev= 30
9499.089152.82319540.513 138.2229551.913131.49169589.912 113.7969620.31197.74761
 9677.3174.873389753.84547.769379768.00640.63561 9777.2438.106329803.81533.78667
 9845.3833.849869889.97129.334799919.26529.865959945.79428.272579993.84819.63792
10058.1425.3477710095.4523.7493910124.2518.38493 10144.822.4424210156.9922.24469
10176.3927.6261810248.0658.8001310268.1165.9241610327.5895.0706210338.64102.1598
10360.75109.882710379.17120.552810438.14147.323110475.24168.737610500.89 180.778
#Mann= 3 , 0 , 0
9499.089    0.12       09499.089    0.12       010500.89    0.12       0
#XS Ineff= 2 , 0
       0                10052.68       0
Bank Sta=9499.089,10500.89
Exp/Cntr=0.3,0.1

Type RM Length L Ch R = 1 ,599.4302,249.677000,249.677000,249.677000
XS GIS Cut Line= 6
1156176.27308831850950.9080706251156332.56233351 851223.87952975
1156430.31237185851373.5867163711156520.87147061851519.060336021
1156580.51275411851628.8750867651156674.88837186851819.012093017
#Sta/Elev= 30
9499.017134.38379538.995119.10669605.02599.350069651.24675.808159679.79664.78757
9698.69856.20753  9770.132.57024 9781.8729.642089789.90928.377879804.55329.59445
9827.56126.746119877.98824.545539925.05817.8144410023.4120.9492510054.5118.68312
 10120.3 17.341710173.6218.6081610199.75 22.441910222.1628.2450810240.8239.34882
10259.4946.2387310317.06 71.430710325.97 75.9878 10362.698.3566310384.58108.0214
10410.22120.903710432.19 127.65110446.84137.277110472.03146.308910500.98162.6125
#Mann= 3 , 0 , 0
9499.017    0.12       09499.017    0.12       010500.98    0.12       0
#XS Ineff= 2 , 0
       09829.791        10036.01       0
Bank Sta=9499.017,10500.98
Exp/Cntr=0.3,0.1

Type RM Length L Ch R = 1 ,349.7532,138.224900,138.224900,138.224900
XS GIS Cut Line= 4
1156085.41337922851112.0237686191156152.86540815851381.831884354
1156291.41552165851534.9662203491156572.16180429 851768.31377992
#Sta/Elev= 30
9648.12386.921219670.81677.77294 9697.8764.999859711.39857.114949748.59831.91003
9779.99617.401489792.56113.87595 9809.4711.486479873.7249.6206619907.54211.04105
 9921.0712.940529980.95112.837639994.692 11.821610034.5114.8188310065.4820.87738
 10105.322.7211610157.3721.67263 10179.523.2731410183.7622.84229 10192.3 19.4467
10196.5619.3934210226.4324.0955410265.1524.0839510294.6822.8817510321.6123.75071
10337.3526.2566910367.8137.5804310424.2762.43023 10444.874.2819210497.8199.87171
#Mann= 3 , 0 , 0
9648.123  0.1193       09648.123  0.1193       010497.81  0.1193       0
#XS Ineff= 2 , 0
       09926.121        10101.71       0
Bank Sta=9648.123,10497.81
Exp/Cntr=0.3,0.1

Type RM Length L Ch R = 1 ,211.5283,111.623300,111.623300,111.623300
XS GIS Cut Line= 6
1155811.56411511851026.0458450211155979.69600693 851330.15834123
1156076.81514264851495.0117363711156109.91656787851554.718325097
1156162.52595895851661.7513808131156277.15938831 851912.38855745
#Sta/Elev= 30
 9446.94160.59029480.367145.77849491.613138.64279510.358129.59439544.097109.6351
9585.33588.853559592.83283.366979611.15967.320569660.312 31.85619682.80521.00501
9705.29812.22218 9731.547.085643 9780.681.8884419791.5221.8196849837.115  6.5282
9865.616 7.47975 9909.3710.81356 9955.077.272871 9981.754.0217269995.0381.188975
10035.646.84663710078.446.15022910140.963.27173510209.93 5.3452410277.785.237771
10307.346.301811 10383.112.3374710419.18 25.529210444.4342.7893710448.9146.77971
#Mann= 3 , 0 , 0
 9446.94    0.12       0 9446.94    0.12       010448.91    0.12       0
#XS Ineff= 2 , 0
       09938.308        10093.97       0
Bank Sta=9446.94,10448.91
Exp/Cntr=0.3,0.1

Type RM Length L Ch R = 1 ,  99.905,99.905000,99.905000,99.905000
XS GIS Cut Line= 6
1155728.89841483851137.4775520131155932.89433594851496.687536034
1155967.42094246851544.6973702531156013.14856312851587.928655731
1156056.45839463851653.9232704291156226.20592055852002.149921205
#Sta/Elev= 30
9499.044105.9724 9510.1499.948289528.72284.039249570.28261.760889581.558 52.0494
9596.59334.03239 9607.87 23.61219622.90515.33201  9641.79.4201269731.9127.597246
9773.2594.5030979826.3097.2758859874.9595.1906059898.6921.240909 9912.160.974319
9931.2464.8088049958.1215.3902479996.8640.52297610024.13 4.8249310115.471.933834
10215.685.43905910291.433.32292110328.386.63156210339.264.47568910353.764.513796
10397.2613.8784210422.5424.5804510445.6828.3364610480.64 55.173910500.9464.03149
#Mann= 3 , 0 , 0
9499.044  0.1023       09499.044  0.1023       010500.94  0.1023       0
#XS Ineff= 2 , 0
       09939.912        10095.81       0
Bank Sta=9499.044,10500.94
Exp/Cntr=0.3,0.1

Type RM Length L Ch R = 1 ,       0,0.000000,0.000000,0.000000
XS GIS Cut Line= 6
1155672.69928186851173.2928738721155878.63710172851548.703104816
1155895.86219177851586.2808243421155916.63470768851645.628387143
1155938.76289246851697.5224146811156115.97925566852070.706968555
#Sta/Elev= 30
9499.02879.476659550.059 34.82319592.95311.168749604.17310.558049611.7117.558698
9615.4636.9506869731.7645.3172939746.7713.6197879843.915-0.675729847.635-0.15743
9855.077  -0.9999993.186  -0.99910014.320.078013 10028.2  -0.99910255.84 -0.4704
10259.54  -0.99910266.730.74651110288.521.08260310310.322.83444410321.212.678315
10350.274.43668610368.434.02131510386.5910.6995410397.48 17.505510430.1731.54563
 10458.446.3882410462.8647.5051710477.3948.3315110481.0249.1984210500.9856.75556
#Mann= 3 , 0 , 0
9499.028   0.035       09499.028   0.035       010500.98   0.035       0
#XS Ineff= 2 , 0
       09939.921         10093.6       0
Bank Sta=9499.028,10500.98
Exp/Cntr=0.3,0.1